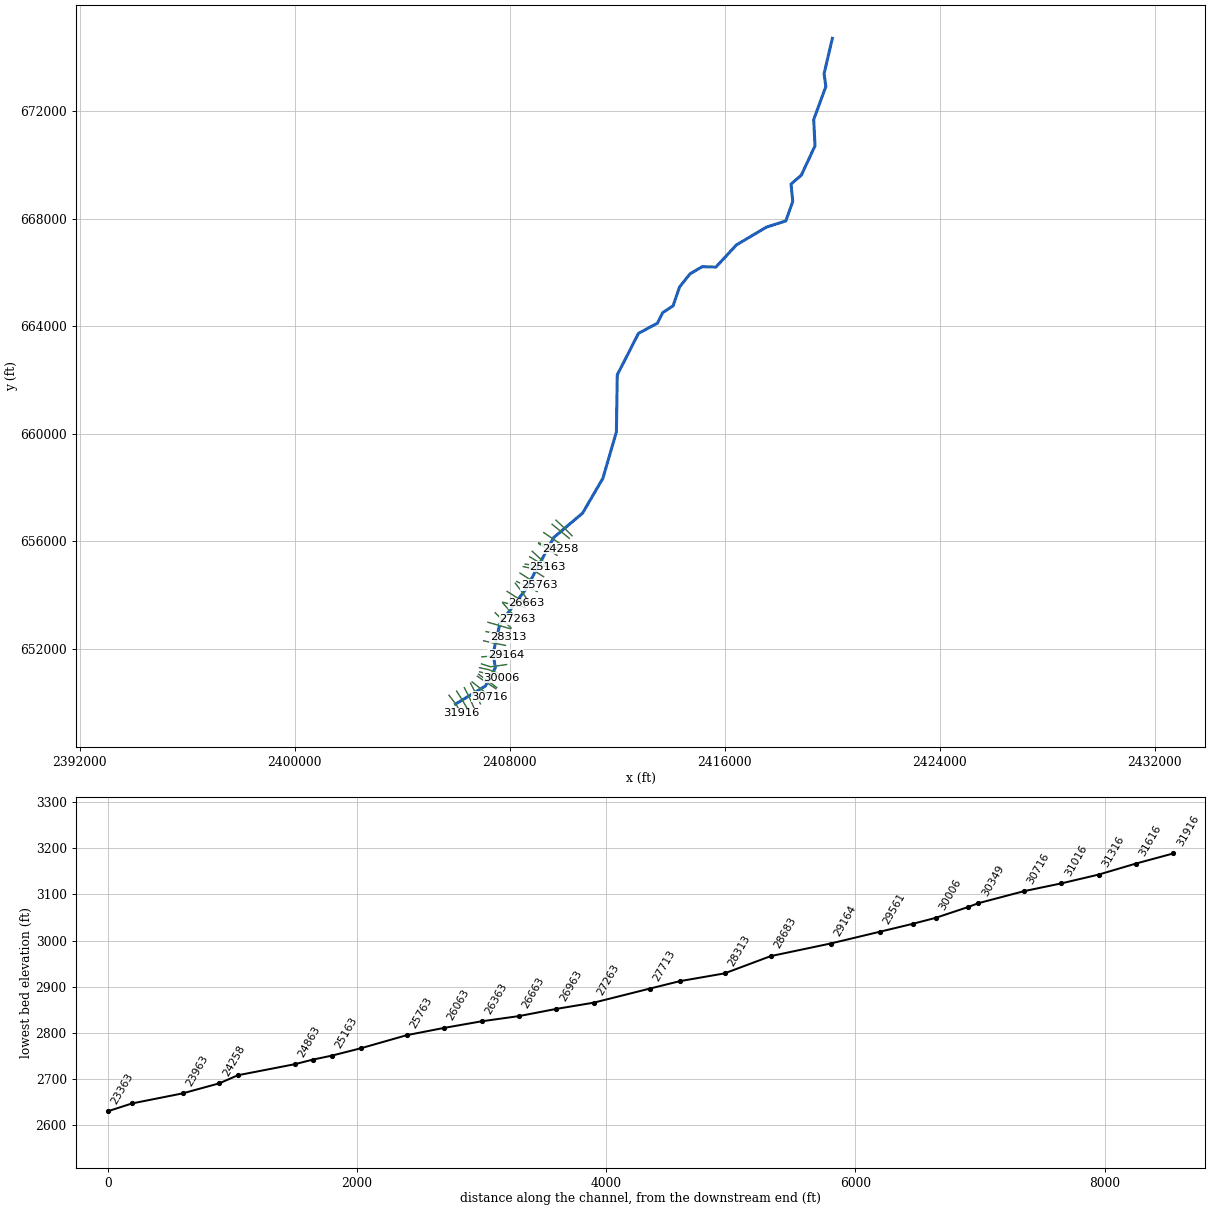
--- BRUSHRN.prj (project) ---

Proj Title=BRUSHRN
Current Plan=p01
Default Exp/Contr=0,0
English Units
Geom File=g01
Geom File=g02
Flow File=f01
Plan File=p01
BEGIN DESCRIPTION:
Stream Name: Brushy Run
Flood Zone: Approximate
Pendleton County, West Virginia
HEC-RAS Version: 5.0.7
Hydrology Method:
Regression equation
END DESCRIPTION:
DSS Export Rating Curves= 0
DSS Export Rating Curve Sorted= 0
DSS Export Volume Flow Curves= 0
DXF OffsetX= 0
DXF OffsetY= 0
DXF ScaleX= 0
DXF ScaleY= 0

--- BRUSHRN.p01 (plan) ---

Plan Title=Floodplain
Program Version=4.00
Geom File=g01
Flow File=f01
K Sum by GR=0
Std Step Tol=0.01
Critical Tol=0.01
Num of Std Step Trials=20
Max Error Tol=0.3
Flow Tol Ratio=0.001
Split Flow NTrial=30
Split Flow Tol=0.02
Split Flow Ratio=0.02
Log Output Level=0
Friction Slope Method=1
Unsteady Friction Slope Method=2
Unsteady Bridges Friction Slope Method=1
Global Log Level=0
CheckData=False
Run HTab=0
Run UNet=0
Run PostProcess=0
UNET Theta=0
UNET Theta Warmup=0
UNET ZTol=0
UNET ZSATol=0
UNET MxIter=0
UNET MaxInSteps=0
UNET DtIC=0
UNET DtMin=0
UNET MaxCRTS=0
UNET WFStab=0
UNET SFStab=0
UNET WFX=0
UNET SFX=0
UNET DSS MLevel=0
UNET DZMax Abort=0
UNET Convert EG Bridges=0
UNET Use Existing IB Tables=0
UNET Froude Limit=0
UNET Froude Power=0
Write IC File=0
Echo Input=False
Echo Output=False
Write Detailed=0

--- BRUSHRN.f01 (steady flow) ---

Flow Title=Flows
Program Version=5.07
Number of Profiles= 6
Profile Names=P100yr,P10yr,P25yr,P50yr,P500yr,P101yr
River Rch & RM=BRUSHRN,Main            ,31916
     561     263     371     464     823     683
River Rch & RM=BRUSHRN,Main            ,29561
     626     293     414     517     918     762
River Rch & RM=BRUSHRN,Main            ,27263
     822     382     542     678    1209    1000
River Rch & RM=BRUSHRN,Main            ,24406
    1007     467     662     829    1484    1225
River Rch & RM=BRUSHRN,Main            ,21164
    1179     546     775     971    1741    1435
River Rch & RM=BRUSHRN,Main            ,17663
    1314     607     863    1081    1942    1599
River Rch & RM=BRUSHRN,Main            ,15263
    1466     676     962    1206    2170    1784
River Rch & RM=BRUSHRN,Main            ,14325
    1657     763    1086    1363    2455    2016
River Rch & RM=BRUSHRN,Main            ,11363
    1846     848    1209    1518    2739    2246
River Rch & RM=BRUSHRN,Main            ,7390
    2187    1003    1430    1797    3252    2662
Boundary for River Rch & Prof#=BRUSHRN,Main            , 1
Up Type= 0
Dn Type= 3
Dn Slope=0.03023
Boundary for River Rch & Prof#=BRUSHRN,Main            , 2
Up Type= 0
Dn Type= 3
Dn Slope=0.03023
Boundary for River Rch & Prof#=BRUSHRN,Main            , 3
Up Type= 0
Dn Type= 3
Dn Slope=0.03023
Boundary for River Rch & Prof#=BRUSHRN,Main            , 4
Up Type= 0
Dn Type= 3
Dn Slope=0.03023
Boundary for River Rch & Prof#=BRUSHRN,Main            , 5
Up Type= 0
Dn Type= 3
Dn Slope=0.03023
Boundary for River Rch & Prof#=BRUSHRN,Main            , 6
Up Type= 0
Dn Type= 3
Dn Slope=0.03023
DSS Import GetInterval= 0
DSS Import GetPeak= 0
DSS Import FillOption= 0

--- BRUSHRN.g01 (geometry) ---

Geom Title=Geometry
Program Version=5.07

River Reach=BRUSHRN         ,Main
Reach XY= 30
2405984.54900001649948.3960000272407095.94300001650620.535999981
2407466.37800002651299.1939999982407384.51635092651835.402743381
2407635.23000002652936.7820000482408599.10700002654220.207000052
2409636.05100001656143.147000042     2410711.691657052.960000035
     2411465.433658344.444000049     2411971.065660076.133000043
2412003.32800001662199.9040000252412792.92200001663743.333999985
     2413500.397664121.9850000422413694.58100001664514.910999974
     2414078.373664765.1150000272414318.18800001665463.431000003
      2414709.55665956.7740000152415162.73700001666223.668000028
     2415673.508666208.624000049     2416435.357 667032.49200002
2417550.56000001667694.158000014     2418273.511667925.113000025
2418532.62700001668651.5799999892418467.53000001669295.547000029
     2418851.902669630.7780000222419360.40499999670718.944000046
2419310.75300002 671696.52300004     2419763.148672926.159000047
     2419697.244673405.1710000052420005.42400002674719.419000045

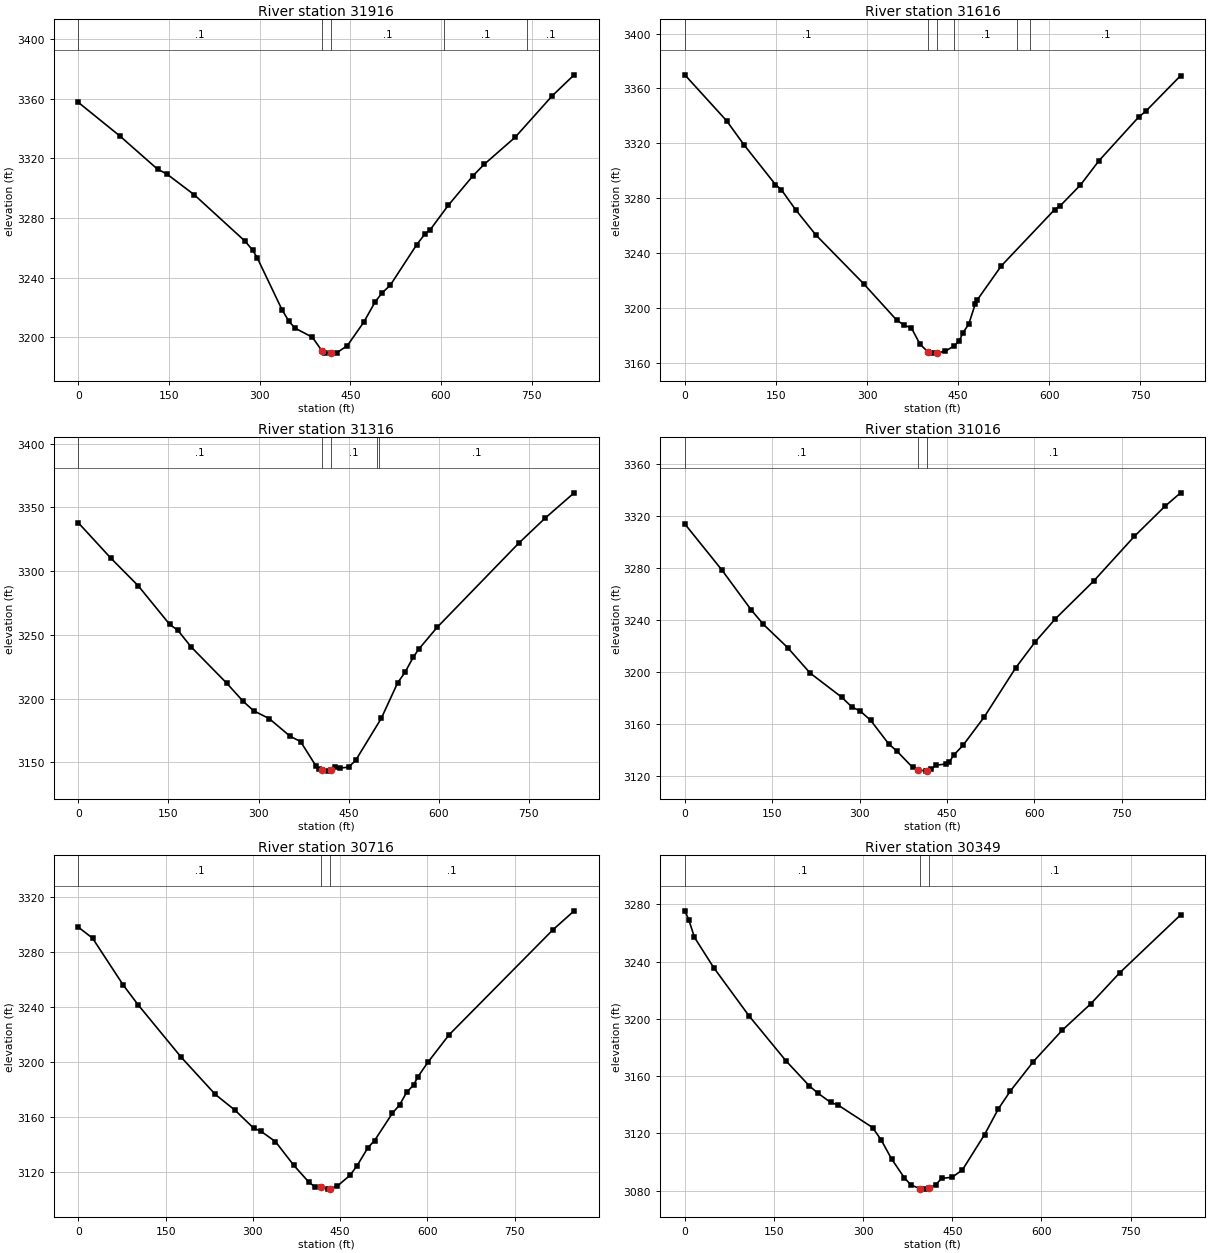
Type RM Length L Ch R = 1 ,31916   ,300.2,300,299.1
XS GIS Cut Line= 3
     2405741.817      650278.606     2405992.985       649953.76
     2406205.379      649603.412
#Sta/Elev= 30
       0 3357.66    68.9 3335.01   131.1 3312.74   146.3 3309.59   191.8 3295.58
   276.2 3264.26   288.5  3258.3   295.8 3253.38   336.9 3218.43   348.5 3210.51
   358.6 3205.98   387.3 3199.84   403.13190.675   408.2  3189.2   418.1 3189.42
     428 3189.59   444.9 3194.15   472.2 3209.98   491.2 3223.74   502.9 3229.82
   515.9 3234.71   559.6 3261.94     573 3269.03   582.4 3272.23     612 3288.49
   652.5 3308.14   671.2 3315.95   722.7 3334.23   783.8 3361.97   820.3 3376.17
#Mann= 5 ,-1 , 0
       0      .1       0   403.1    .045       0   418.1      .1       0
  604.23      .1       0  742.44      .1       0
Bank Sta=403.1,418.1
XS Rating Curve= 0 ,0
Exp/Cntr=0.3,0.1

Type RM Length L Ch R = 1 ,31616   ,299.7,300,298.3
XS GIS Cut Line= 3
     2406025.835      650432.847     2406244.957      650088.724
 2406449.3006501649735.289720775
#Sta/Elev= 30
       0 3369.91    68.7 3336.51    97.7 3318.79   149.3 3289.96   158.8 3286.31
   182.5 3271.63   215.7 3253.33   294.7 3217.62   348.5 3191.41   361.3 3187.49
   372.9 3185.67   387.4 3173.56   400.53168.078   407.7 3167.23   415.53167.493
   428.6 3168.55   443.5 3172.58   451.7 3176.06   457.5 3181.74   467.5 3188.43
     478 3202.87   480.9 3205.64     521 3230.77   608.8 3271.74     618 3274.53
   651.3 3289.68   681.9  3307.4   747.3 3339.25   758.6 3343.27   816.2 3369.32
#Mann= 6 ,-1 , 0
       0      .1       0   400.5    .045       0   415.5      .1       0
  443.46      .1       0  546.13      .1       0  568.74      .1       0
Bank Sta=400.5,415.5
XS Rating Curve= 0 ,0
Exp/Cntr=0.3,0.1

Type RM Length L Ch R = 1 ,31316   ,299.1,300,299.2
XS GIS Cut Line= 3
     2406312.952      650558.054      2406502.59      650190.976
     2406670.703      649814.639
#Sta/Elev= 30
       0 3337.89    54.1 3310.18    99.8 3288.45   152.1  3258.2   165.6 3253.63
   187.7 3240.61   246.7 3212.31   273.8 3198.21   291.6 3190.58   317.6 3184.43
   352.5 3170.57   369.9 3166.41   395.3 3147.44   399.8 3144.89   405.73144.114
   416.4 3143.23   420.73144.465   426.4 3146.69   435.2 3145.64   449.7  3146.3
   461.5  3151.6   504.2 3184.55   531.5 3212.45   543.6 3220.62   557.8 3232.74
   566.6 3238.83   597.3 3255.97   733.1 3321.93   776.7 3341.41   825.3 3361.38
#Mann= 5 ,-1 , 0
       0      .1       0   405.7    .045       0   420.7      .1       0
  497.38      .1       0  500.82      .1       0
Bank Sta=405.7,420.7
XS Rating Curve= 0 ,0
Exp/Cntr=0.3,0.1

Type RM Length L Ch R = 1 ,31016   ,296.1,300,302.4
XS GIS Cut Line= 3
     2406543.131      650725.508     2406732.101      650363.471
     2406911.253      649958.261
#Sta/Elev= 30
       0  3313.7    63.9 3278.22   114.3 3247.58   135.1  3236.6   176.6 3218.84
   215.1 3199.34   269.2 3180.89   287.2 3173.19   300.8 3170.32   318.9 3163.21
   350.4 3144.84   363.9 3139.62     391 3127.05   400.93125.221   413.4 3124.11
   415.93124.175     423 3125.48   430.9 3128.66   448.4 3129.55   454.5 3131.27
   461.5 3136.27   477.6 3143.81     514 3165.54   568.5 3203.52   601.9 3223.34
   636.4 3240.95     702 3269.83     772 3304.18   824.5 3327.23   851.4 3337.54
#Mann= 3 ,-1 , 0
       0      .1       0   400.9    .045       0   415.9      .1       0
Bank Sta=400.9,415.9
XS Rating Curve= 0 ,0
Exp/Cntr=0.3,0.1

Type RM Length L Ch R = 1 ,30716   ,364.8,366.5,366.3
XS GIS Cut Line= 3
     2406601.975         650774.     2406935.152      650510.628
     2407257.298      650229.531
#Sta/Elev= 30
       0 3297.88    24.4 3289.92    76.8    3256   102.4 3241.56   176.5 3203.37
   235.5 3176.11   269.5 3164.58   301.7 3151.43   313.2 3149.53   338.8 3141.77
   370.1 3124.65   395.7  3112.5   407.1 3108.65   417.23108.389   429.5  3107.2
   432.23107.594   445.4 3109.51   466.9 3117.25   479.1 3124.25   497.9  3137.5
   509.1 3142.53   539.9 3162.51   552.1 3168.46   564.2 3177.61   576.4 3183.12
   583.4 3188.84   600.7 3199.48   637.2 3219.53   815.5  3295.9   852.2 3309.79
#Mann= 3 ,-1 , 0
       0      .1       0   417.2    .045       0   432.2      .1       0
Bank Sta=417.2,432.2
XS Rating Curve= 0 ,0
Exp/Cntr=0.3,0.1

Type RM Length L Ch R = 1 ,30349   ,83.4,83.5,83
XS GIS Cut Line= 2
2406797.32092309650986.1758171072407487.72220885650517.982071061
#Sta/Elev= 30
       0 3275.54     6.6 3269.42    16.2 3257.03    48.6 3235.87     108 3202.15
   170.4 3170.63   209.5 3153.21     224  3148.1   245.3 3141.68   257.9  3139.8
   315.9 3124.11   330.4  3115.4   347.9 3102.15   369.1 3089.16   380.7 3083.89
   396.43081.282   403.7 3081.06   410.83081.855   422.2 3084.09   431.9 3088.55
   449.8 3089.35   467.1 3094.51   504.4 3119.21   527.5 3137.12   547.7 3149.62
   586.5  3170.2   634.8 3192.03   683.2 3210.64     732 3232.35   834.2 3272.72
#Mann= 3 , 0 , 0
       0      .1       0   396.4    .045       0   410.8      .1       0
Bank Sta=396.4,410.8
XS Rating Curve= 0 ,0
Exp/Cntr(USF)=0,0
Exp/Cntr=0.3,0.1

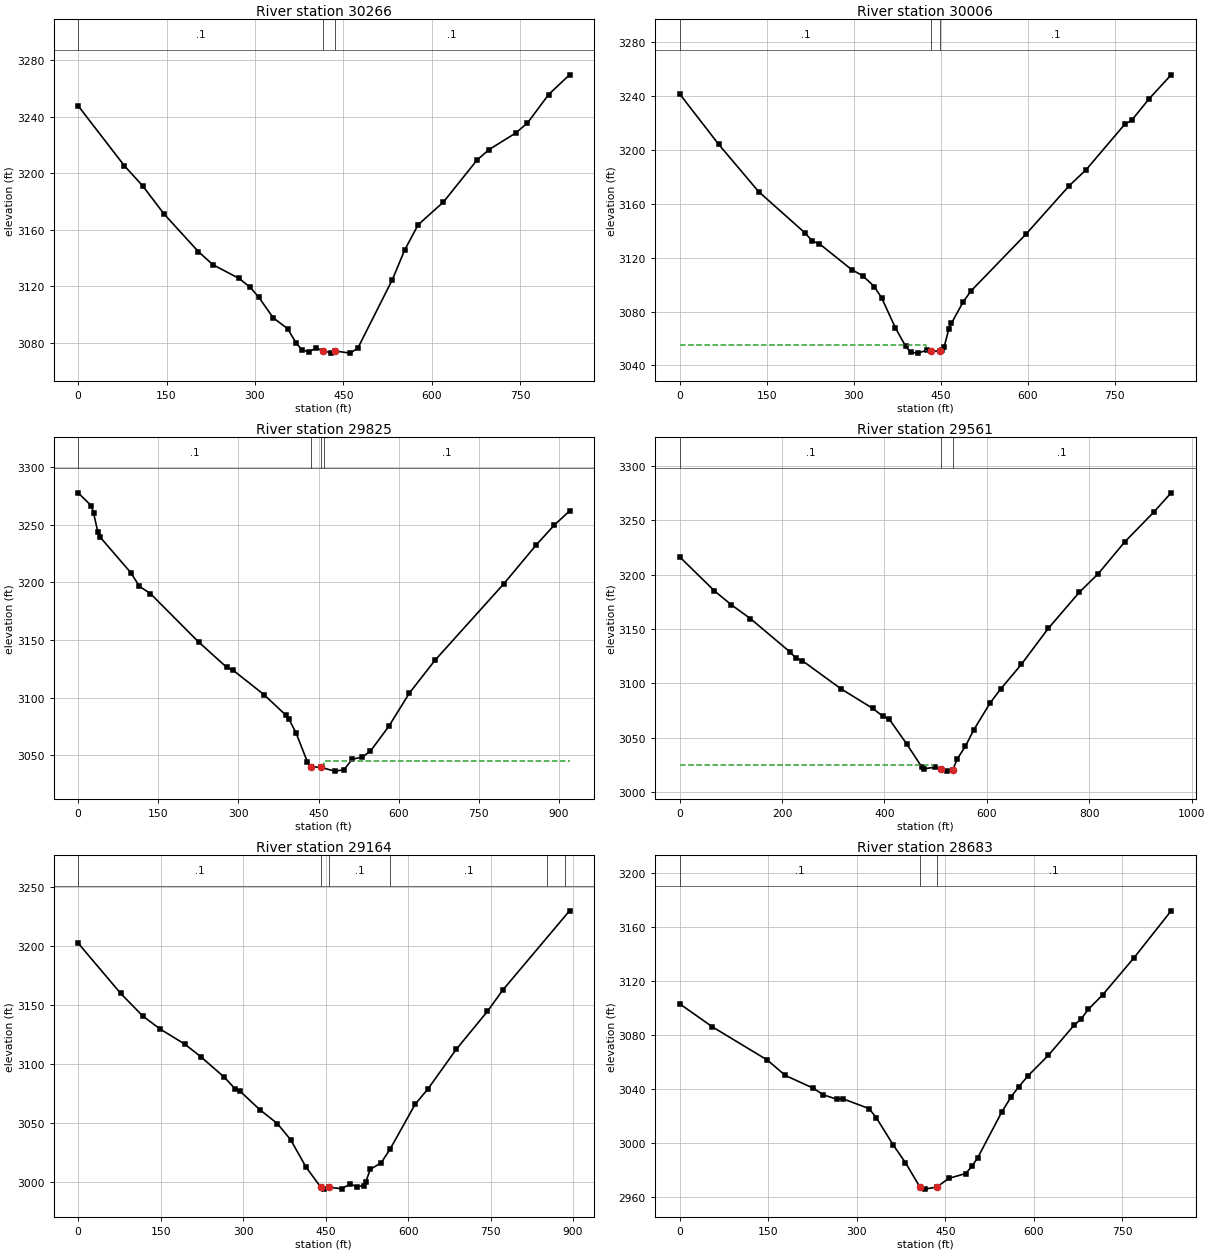
Type RM Length L Ch R = 1 ,30266   ,256.1,259.8,261.8
XS GIS Cut Line= 3
     2406847.193      651056.203     2407191.037      650816.667
     2407518.822      650562.949
#Sta/Elev= 30
       0 3247.83    78.2 3205.45   109.8 3190.92   145.7 3171.19   204.2 3144.38
   228.6 3135.24   272.5  3125.6   291.9 3119.24   306.6  3112.1     331 3097.57
   355.3 3089.92   369.9 3079.72   379.7 3074.93   391.4 3073.43   404.1 3076.27
   415.2 3074.11   428.8 3072.92     435 3074.18   461.2 3072.58   474.3 3075.97
     533 3124.57   554.1 3145.75   576.9 3163.56   619.7 3179.62   676.8 3209.38
   696.9 3216.71   742.2 3228.48   762.3 3235.62   798.1 3255.76   833.6 3269.73
#Mann= 3 , 0 , 0
       0      .1       0   415.2    .045       0     435      .1       0
Bank Sta=415.2,435
XS Rating Curve= 0 ,0
Exp/Cntr=0.3,0.1

Type RM Length L Ch R = 1 ,30006   ,157,180.8,152.8
XS GIS Cut Line= 3
2406885.83325563651147.908394713 2407314.4397605651035.585365469
     2407704.038      650928.131
#Sta/Elev= 30
       0  3241.6    67.1 3204.25   135.9 3169.15     216 3138.42   228.4 3132.48
   240.8 3130.38   296.8 3111.07   315.2 3106.77   335.4 3098.64   348.3 3090.06
   371.8 3067.95   389.6 3054.19   397.9 3049.83   410.3 3049.18   426.9 3051.41
   432.93050.861   447.93050.655   451.7  3051.2   455.8 3053.68   464.1  3067.4
   468.3 3071.29     489 3087.42   502.4 3095.44   596.8 3137.45   671.6 3173.55
   700.7 3185.39     767 3218.99   779.5 3222.26   809.2    3238   847.2 3255.84
#Mann= 3 ,-1 , 0
       0      .1       0   432.9    .045       0   447.9      .1       0
#XS Ineff= 2 , 0
          424.71 3055.08
Permanent Ineff=
       F       F
Bank Sta=432.9,447.9
XS Rating Curve= 0 ,0
Exp/Cntr=0.3,0.1

Type RM Length L Ch R = 1 ,29825   ,231.8,264.3,241.2
XS GIS Cut Line= 3
2406874.41030977 651303.733657612407213.86041162651231.587051177
2407749.33664874651028.870080218
#Sta/Elev= 30
       0 3277.72    24.9 3266.45      29 3260.12    37.1 3243.39    41.2 3239.32
    98.5 3208.54   114.8 3196.67   135.3 3190.37   225.3  3148.5   278.4 3126.29
   290.7 3123.69   348.3 3102.56   388.7 3084.99   394.8 3081.28   407.9  3069.5
   429.2 3044.25   435.2 3040.23   453.7 3039.73   480.6 3036.44   497.7 3037.65
   512.7  3046.7   531.9 3048.68     547 3053.76   581.4 3075.27   620.1 3104.21
   667.8 3132.53   797.1 3199.09   856.9 3232.34   891.2 3249.79   919.6 3261.96
#Mann= 4 ,-1 , 0
       0      .1       0   435.2    .045       0   453.7      .1       0
   460.8      .1       0
#XS Ineff= 2 , 0
                          459.68         3045.25
Permanent Ineff=
       F       F
Bank Sta=435.2,453.7
XS Rating Curve= 0 ,0
Exp/Cntr=0.3,0.1

Type RM Length L Ch R = 1 ,29561   ,401.2,397.1,399.8
XS GIS Cut Line= 4
2406950.69814299651444.2145847092407283.52793476 651337.90154762
2407458.48739471651357.9804436762407888.30104506651420.806210573
#Sta/Elev= 30
       0  3216.3    67.9 3185.02   100.8 3172.28   137.9 3159.62   214.7 3129.17
   226.8  3123.3   239.4 3120.87     315 3094.94   376.8 3077.02   396.9 3069.69
     409 3067.18   443.5 3044.13   473.4 3022.66   477.4 3021.37   497.7 3022.79
   511.1 3021.01   521.7 3019.23   533.6 3020.66   541.9 3030.23   557.9 3042.04
   574.3 3057.08   606.6 3082.16   626.8 3094.72   667.3 3117.44   719.8 3150.46
   780.4 3183.72   816.8 3200.49   869.4 3230.17     926 3257.54   959.9 3275.28
#Mann= 3 ,-1 , 0
       0      .1       0   511.1    .045       0   533.6      .1       0
#XS Ineff= 2 , 0
          495.71 3025.31
Permanent Ineff=
       F       F
Bank Sta=511.1,533.6
XS Rating Curve= 0 ,0
Exp/Cntr=0.3,0.1

Type RM Length L Ch R = 1 ,29164   ,480.7,481,473.3
XS GIS Cut Line= 3
 2406965.6992274651705.5806889012407459.24372268651749.175288648
2407855.47220097651786.671435907
#Sta/Elev= 30
       0 3202.33    77.3 3159.68   117.5 3140.45   149.6 3129.28   193.8 3116.62
   223.6 3105.72   266.1 3088.38     286 3078.45   294.8 3076.52   330.3    3061
   362.5 3049.09   386.5 3035.43   414.7 3012.01   441.2 2995.25   446.8 2993.56
     456 2994.99   478.9 2994.01     495 2997.76     507 2995.64   519.1 2996.63
   523.1  2999.7   531.1 3010.26   551.2 3016.01   567.3 3027.52   612.8 3065.59
   636.1 3078.58   687.4  3112.1   744.1 3144.33   772.2 3162.51   893.5 3229.72
#Mann= 6 ,-1 , 0
       0      .1       0   441.2    .045       0     456      .1       0
   567.3      .1       0  853.39      .1       0  885.08      .1       0
Bank Sta=441.2,456
XS Rating Curve= 0 ,0
Exp/Cntr=0.3,0.1

Type RM Length L Ch R = 1 ,28683   ,368.5,370.1,367.5
XS GIS Cut Line= 3
2407029.74590434 652303.668399622407429.05290434 652213.69139962
2407844.45252171652132.894365008
#Sta/Elev= 30
       0 3103.14      55 3086.22   148.5 3061.56   178.8 3050.22   226.5 3040.75
   242.9 3035.95   265.8 3032.66   275.9 3033.07   320.8 3025.66   332.8  3019.1
   361.8 2998.77   382.4 2985.72     407 2967.71   415.1 2966.17   435.5 2967.74
   455.9 2974.12   484.4 2977.69     495 2983.04   504.8 2989.34   545.5 3023.13
   561.8 3034.63     574 3041.65   590.3 3050.03   624.7 3065.18   667.8  3087.2
     680 3091.91   692.2 3099.07   716.8 3109.93   769.6 3137.17   832.5  3171.9
#Mann= 3 ,-1 , 0
       0      .1       0     407    .045       0   435.5      .1       0
Bank Sta=407,435.5
XS Rating Curve= 0 ,0
Exp/Cntr=0.3,0.1

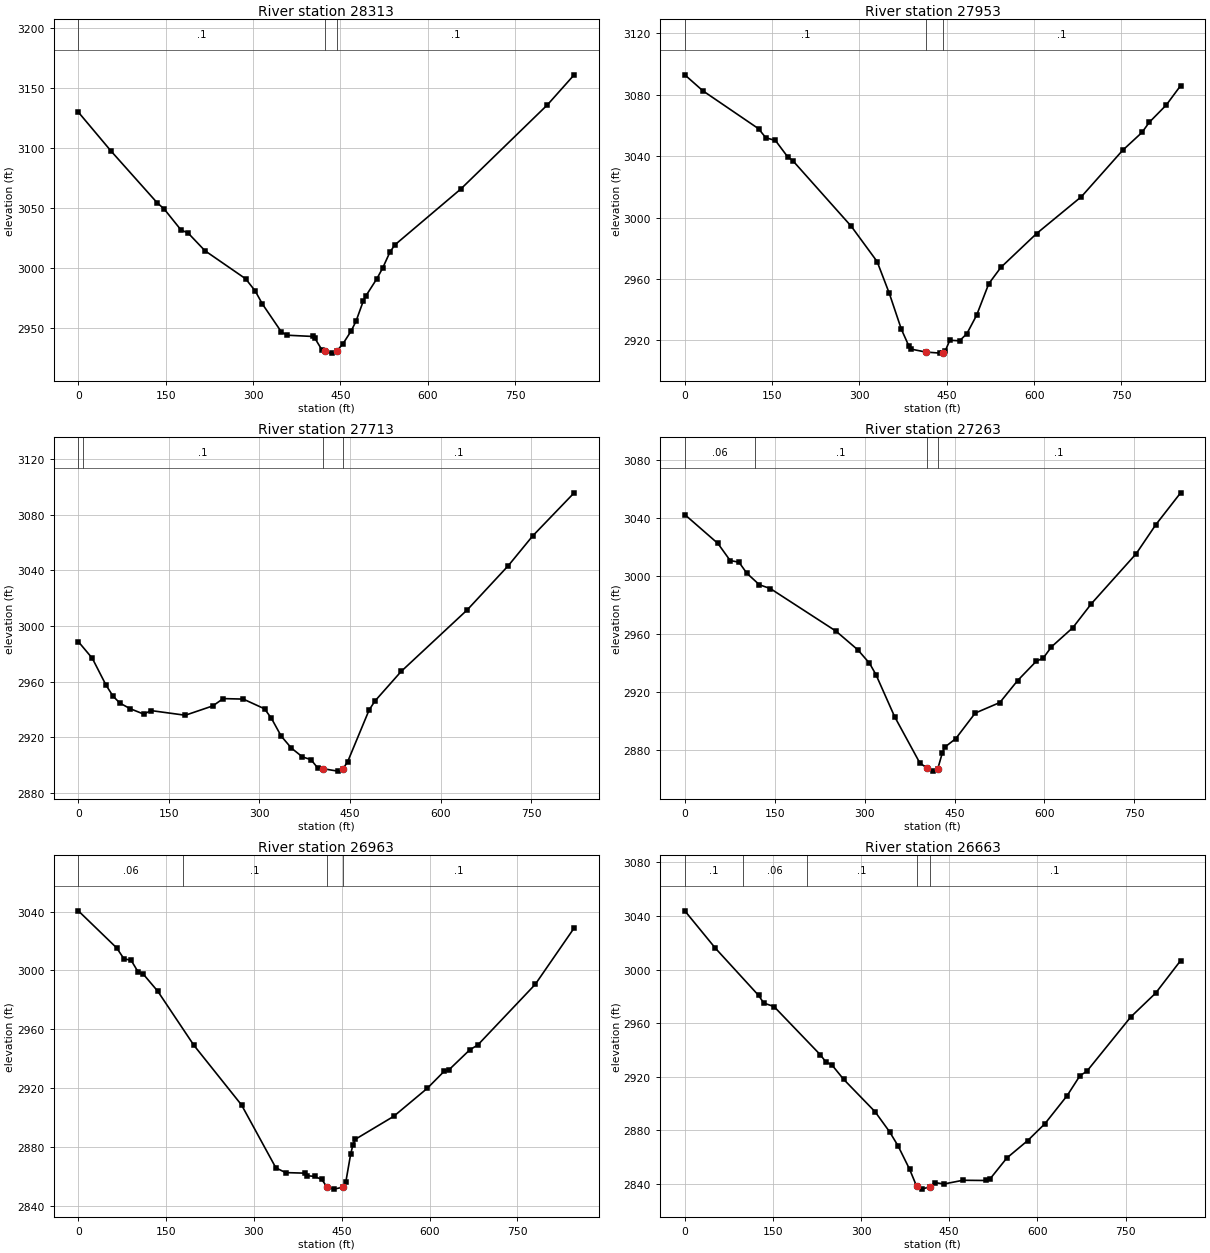
Type RM Length L Ch R = 1 ,28313   ,358.9,360.1,359.5
XS GIS Cut Line= 3
     2407123.185      652647.138     2407545.082      652547.343
2407946.97946199652432.359875742
#Sta/Elev= 30
       0 3129.99    56.3  3097.4   135.2 3054.37   147.5 3049.02   176.3 3031.58
   188.6 3028.96   217.4 3014.25   287.3  2990.8   303.7  2980.7     316 2969.81
   348.9 2946.29   358.8 2943.65   402.4 2942.62   406.5 2940.95   418.1 2931.63
   422.9  2930.2   435.2 2928.69   443.6 2930.23   454.7 2936.64   468.6 2947.21
   476.9  2955.3   489.4 2972.18   493.5 2976.19   512.9 2990.96   522.6 2999.63
   535.1 3012.98   543.4    3019   656.8 3065.73   805.6 3136.04   851.6 3161.14
#Mann= 3 ,-1 , 0
       0      .1       0   422.9    .045       0   443.6      .1       0
Bank Sta=422.9,443.6
XS Rating Curve= 0 ,0
Exp/Cntr=0.3,0.1

Type RM Length L Ch R = 1 ,27953   ,249.5,239.9,235.7
XS GIS Cut Line= 3
2407192.98055115652993.267850781 2407621.1223304652871.255312776
 2408010.3493304652754.397312776
#Sta/Elev= 30
       0  3092.9    30.9 3082.54   126.6 3057.83   139.1 3051.95   155.7 3050.15
   176.5 3039.59   185.3 3037.11     286 2994.26   330.3 2971.35   351.2 2950.68
     372 2927.22   384.5 2916.65   388.6 2914.35   413.92912.431   438.6 2911.73
   443.6  2911.9   446.9 2912.81   455.2 2920.12   471.9 2919.74   484.5 2924.41
   501.2 2936.39   522.1 2956.93   542.9 2967.55   604.2 2989.57   681.3 3013.62
   751.9 3043.72   785.2 3055.38   797.7 3061.97   826.9 3073.22   851.6 3085.85
#Mann= 3 ,-1 , 0
       0      .1       0   413.9    .045       0   443.6      .1       0
Bank Sta=413.9,443.6
XS Rating Curve= 0 ,0
Exp/Cntr=0.3,0.1

Type RM Length L Ch R = 1 ,27713   ,450.8,450,451.5
XS GIS Cut Line= 3
     2407459.794      653347.064      2407754.03      653058.045
      2408054.11      652780.164
#Sta/Elev= 30
       0 2988.78    23.1 2976.84    45.9 2957.51    57.3  2949.7    68.7 2944.63
    85.9 2940.56   108.7 2936.62   120.1 2939.23   177.2 2935.86   222.9  2942.6
     240 2947.83   273.3 2947.47   308.5 2940.48   319.9 2933.63     336 2920.91
   352.9 2912.26   371.3 2905.89   385.4 2903.95   396.6 2897.93   405.5  2897.4
   429.8 2895.68   437.8 2896.91   446.3 2902.57   481.8 2939.73   491.6 2946.19
   534.8 2967.35   644.4 3011.67   712.4 3043.46   752.6 3064.74   821.4 3095.78
#Mann= 4 ,-1 , 0
       0     .06       0    6.91      .1       0   405.5    .045       0
   437.8      .1       0
Bank Sta=405.5,437.8
XS Rating Curve= 0 ,0
Exp/Cntr=0.3,0.1

Type RM Length L Ch R = 1 ,27263   ,290.2,300,306.7
XS GIS Cut Line= 3
      2407736.95      653718.989     2408010.915       653405.06
     2408300.655      653114.287
#Sta/Elev= 30
       0 3042.07    55.2 3022.17    75.7 3010.37    90.4 3009.23   103.4 3001.66
   124.4 2993.66   142.6 2991.06   252.2 2961.68   288.7 2948.75   308.1 2939.54
   318.9 2931.64     350 2902.68   392.1 2870.71   403.6 2867.36   414.2  2865.1
   422.1 2866.89   429.4 2877.42   433.4 2881.53     452 2887.53   484.4 2905.13
   525.6 2912.44   555.2 2927.59   586.4 2940.94   597.8 2943.03   611.7 2950.86
   647.2 2964.03   678.3 2980.64   752.9 3015.06   785.8 3035.16   827.1 3057.09
#Mann= 4 ,-1 , 0
       0     .06       0  116.33      .1       0   403.6    .045       0
   422.1      .1       0
Bank Sta=403.6,422.1
XS Rating Curve= 0 ,0
Exp/Cntr=0.3,0.1

Type RM Length L Ch R = 1 ,26963   ,303.4,300,296.1
XS GIS Cut Line= 3
2407751.16973342653737.222124258     2408177.123      653631.343
     2408575.732      653543.408
#Sta/Elev= 30
       0 3040.49    65.5 3015.32    77.9 3007.94    90.2 3006.91   102.6  2998.7
   110.8 2997.59   135.6 2985.97   197.4 2949.24   278.9 2908.67   337.5 2866.03
     354  2862.8     387 2862.42   391.1 2860.69   403.5 2860.21   415.9 2858.14
   424.42853.248   436.5 2851.58   452.9 2852.95     457 2856.47   465.2 2875.18
   469.2 2881.83   473.3 2885.43   538.9 2901.02   596.2 2920.03   624.9 2931.52
   633.1 2932.53   668.9 2946.19   682.3 2949.36   780.6 2990.56   847.1 3028.86
#Mann= 4 ,-1 , 0
       0     .06       0  178.34      .1       0   424.4    .045       0
   452.9      .1       0
Bank Sta=424.4,452.9
XS Rating Curve= 0 ,0
Exp/Cntr=0.3,0.1

Type RM Length L Ch R = 1 ,26663   ,303.1,300,293.3
XS GIS Cut Line= 3
     2407905.247      654143.353     2408245.551      653922.121
2408619.12718609653693.645163563
#Sta/Elev= 30
       0 3043.89    52.2 3015.89   125.6 2980.68   134.4 2974.96   151.8 2972.37
   230.8 2936.26   240.3 2930.83   250.1 2928.88   270.3    2918   323.8 2893.78
   348.4 2878.86   362.8 2868.36   382.5 2850.87   394.6 2838.03   403.3 2835.95
   416.7 2837.64     426  2840.8   441.1  2839.8   473.4 2842.57   511.8  2842.4
   519.7  2843.7     548 2859.19   583.7 2872.28   612.8  2884.8   650.6 2905.76
   672.7 2920.85   683.9 2923.85     759 2964.61   801.2 2982.37   843.8 3006.71
#Mann= 5 ,-1 , 0
       0      .1       0   99.08     .06       0  207.64      .1       0
   394.6    .045       0   416.7      .1       0
Bank Sta=394.6,416.7
XS Rating Curve= 0 ,0
Exp/Cntr=0.3,0.1

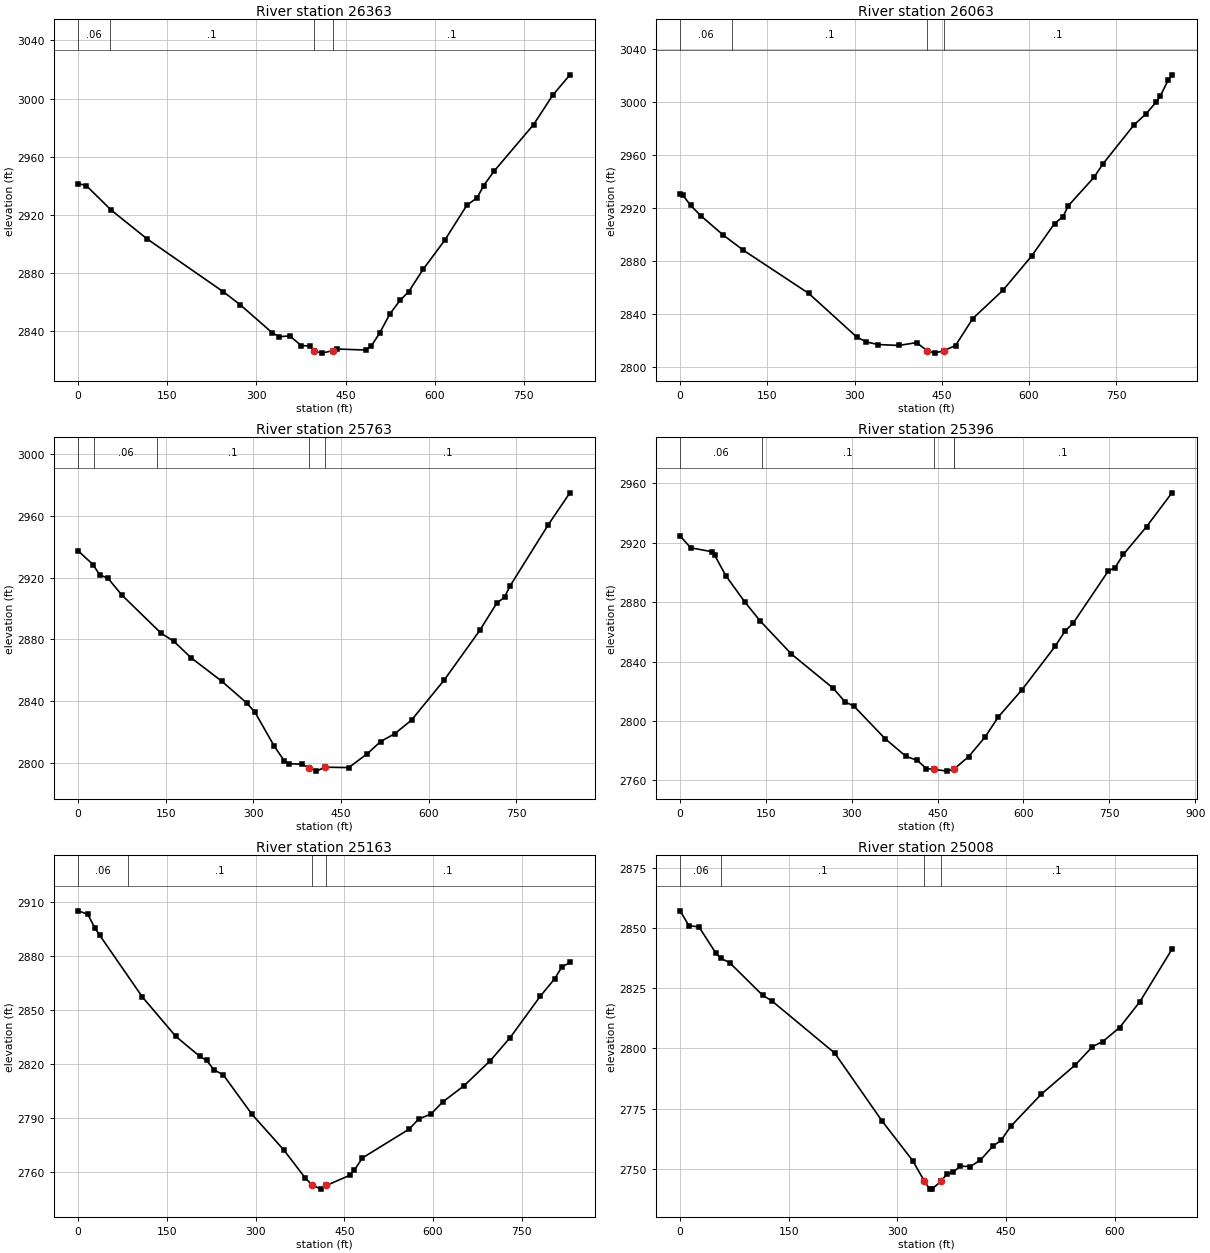
Type RM Length L Ch R = 1 ,26363   ,293.2,300,307.1
XS GIS Cut Line= 3
     2408207.567      654446.838     2408460.817      654122.323
2408695.81685211653779.032521712
#Sta/Elev= 30
       0 2941.42    13.6 2940.07    55.7 2923.14   115.7 2903.43   244.5 2866.86
     273  2857.9   327.1 2838.51   338.5 2835.98   356.3 2836.49   375.4 2829.89
   389.8 2829.52   397.2 2826.23   409.8 2824.64   429.2 2826.38   435.6 2827.48
   483.7 2826.77   493.4 2829.49   507.6 2838.59   524.8 2851.69   541.8    2861
   556.4 2866.99   580.6 2882.31   617.2  2902.5   654.3 2926.55   671.6 2931.65
   682.4 2939.97   700.4 2950.14   766.6 2982.09   798.7 3002.25   827.7 3016.33
#Mann= 4 ,-1 , 0
       0     .06       0   53.75      .1       0   397.2    .045       0
   429.2      .1       0
Bank Sta=397.2,429.2
XS Rating Curve= 0 ,0
Exp/Cntr=0.3,0.1

Type RM Length L Ch R = 1 ,26063   ,301.5,300,298.3
XS GIS Cut Line= 3
      2408262.18      654510.125      2408656.35      654326.612
2409020.67384055654136.385598243
#Sta/Elev= 30
       0 2930.77       5 2929.51    17.9 2922.03    35.9 2914.02      74 2899.61
   108.2 2888.27   221.2 2855.47   303.9 2822.47   320.4 2818.83   340.4 2816.86
   376.2 2816.18   406.6 2818.29   424.7 2812.29   437.5 2810.37   454.2 2812.35
   473.6 2816.13   503.3 2836.49   555.2 2857.88   604.5 2883.74   643.9 2908.25
   658.6 2913.55   667.6 2921.69   712.1 2943.37   726.9  2953.2   780.4 2982.67
     801 2991.07   818.8 3000.06   825.6 3004.42   839.1 3016.47   845.8 3020.61
#Mann= 4 ,-1 , 0
       0     .06       0   88.83      .1       0   424.7    .045       0
   454.2      .1       0
Bank Sta=424.7,454.2
XS Rating Curve= 0 ,0
Exp/Cntr=0.3,0.1

Type RM Length L Ch R = 1 ,25763   ,365.6,366.8,365.8
XS GIS Cut Line= 3
2408383.71958276654823.080699309     2408728.255      654603.394
     2409098.427      654378.785
#Sta/Elev= 30
       0 2937.49    25.5 2928.58    36.8 2921.96      51 2919.73    74.7 2908.87
   141.7 2884.15     164 2878.73   193.3 2868.12   245.7 2852.94   288.2 2838.92
   302.5 2832.84   335.7 2810.74   352.8 2801.23   361.5 2799.41   383.1 2799.03
   394.7  2796.8   407.9 2794.58   422.4 2797.13     463 2796.87   495.2 2805.94
   517.5 2813.74   541.8 2818.83   570.6 2827.72   626.8 2853.83   687.6 2886.03
   716.5 2903.61   729.7 2907.42     739  2914.6   804.5 2954.39   841.6 2975.13
#Mann= 5 ,-1 , 0
       0      .1       0   27.31     .06       0  135.45      .1       0
   394.7    .045       0   422.4      .1       0
Bank Sta=394.7,422.4
XS Rating Curve= 0 ,0
Exp/Cntr=0.3,0.1

Type RM Length L Ch R = 1 ,25396   ,224.8,233.2,237.7
XS GIS Cut Line= 4
2408504.74976891655064.4320246982408759.02968059655009.434843707
2408926.96305559654896.944724207 2409264.5059853654687.737575343
#Sta/Elev= 30
       0  2924.6    18.4 2916.61    55.2 2914.03    60.2 2911.73    79.8 2897.84
   112.5 2880.43   139.7 2867.43   194.4 2845.12   267.6 2822.01   288.7 2812.69
   303.1 2810.28   358.2 2788.11   394.6 2776.25   414.6 2773.48     430 2768.04
   443.4 2767.48   466.5 2766.29   478.62767.688   504.2 2776.08   532.6 2789.11
   556.2 2802.86   597.3 2821.03   655.4 2850.35   672.8 2860.67   686.4 2865.67
   748.3 2901.07     760 2903.27   774.5 2912.12   815.2 2930.93   859.4 2953.62
#Mann= 5 ,-1 , 0
       0     .06       0  143.07      .1       0   443.4    .045       0
   478.6      .1       0  478.64      .1       0
Bank Sta=443.4,478.6
XS Rating Curve= 0 ,0
Exp/Cntr=0.3,0.1

Type RM Length L Ch R = 1 ,25163   ,159.3,154.5,148.8
XS GIS Cut Line= 3
     2408578.689      655155.475      2408983.54      655109.559
2409404.37723474655057.267408432
#Sta/Elev= 30
       0 2905.14    16.2 2903.27    28.2 2895.68    36.3 2891.62   108.7 2857.16
   165.1 2835.25   205.4 2824.22   217.4 2821.84   229.5  2816.7   245.6 2813.77
   293.9 2791.88   347.7 2772.05   383.8 2756.51   395.6 2752.51   410.7 2750.23
   419.9 2752.29     459  2757.9   467.1 2760.89   480.8 2767.62   559.7 2783.63
   575.9 2789.24   596.8 2792.09   616.2 2798.69   652.5 2807.78   696.9 2821.74
   730.3 2834.51   781.5 2857.64   805.7 2867.32   817.8 2873.85   831.5 2876.41
#Mann= 4 ,-1 , 0
       0     .06       0   84.55      .1       0   395.6    .045       0
   419.9      .1       0
Bank Sta=395.6,419.9
XS Rating Curve= 0 ,0
Exp/Cntr=0.3,0.1

Type RM Length L Ch R = 1 ,25008   ,147.7,145.5,142.7
XS GIS Cut Line= 2
2408744.52875074655430.2841759032409324.46477579655077.050415192
#Sta/Elev= 30
       0 2857.28      12 2851.12      26 2850.59    49.4 2839.62    56.5 2837.46
    68.2 2835.75   114.2 2822.05   126.3 2819.89   213.4 2798.09   278.9 2769.77
   321.1 2753.31   337.2 2744.81   344.5 2741.53   347.5 2741.47   360.32744.756
   367.9 2747.69   377.3  2748.6   386.6 2751.02   400.7 2750.88   414.5 2753.55
     432  2759.4   442.9 2761.73   456.9 2767.75   498.6 2780.97   545.5 2793.13
   569.3 2800.76   583.4 2802.86   606.8 2808.72   634.9 2819.53     679 2841.28
#Mann= 4 ,-1 , 0
       0     .06       0    56.5      .1       0   337.2    .045       0
   360.3      .1       0
Bank Sta=337.2,360.3
XS Rating Curve= 0 ,0
Exp/Cntr(USF)=0,0
Exp/Cntr=0.3,0.1

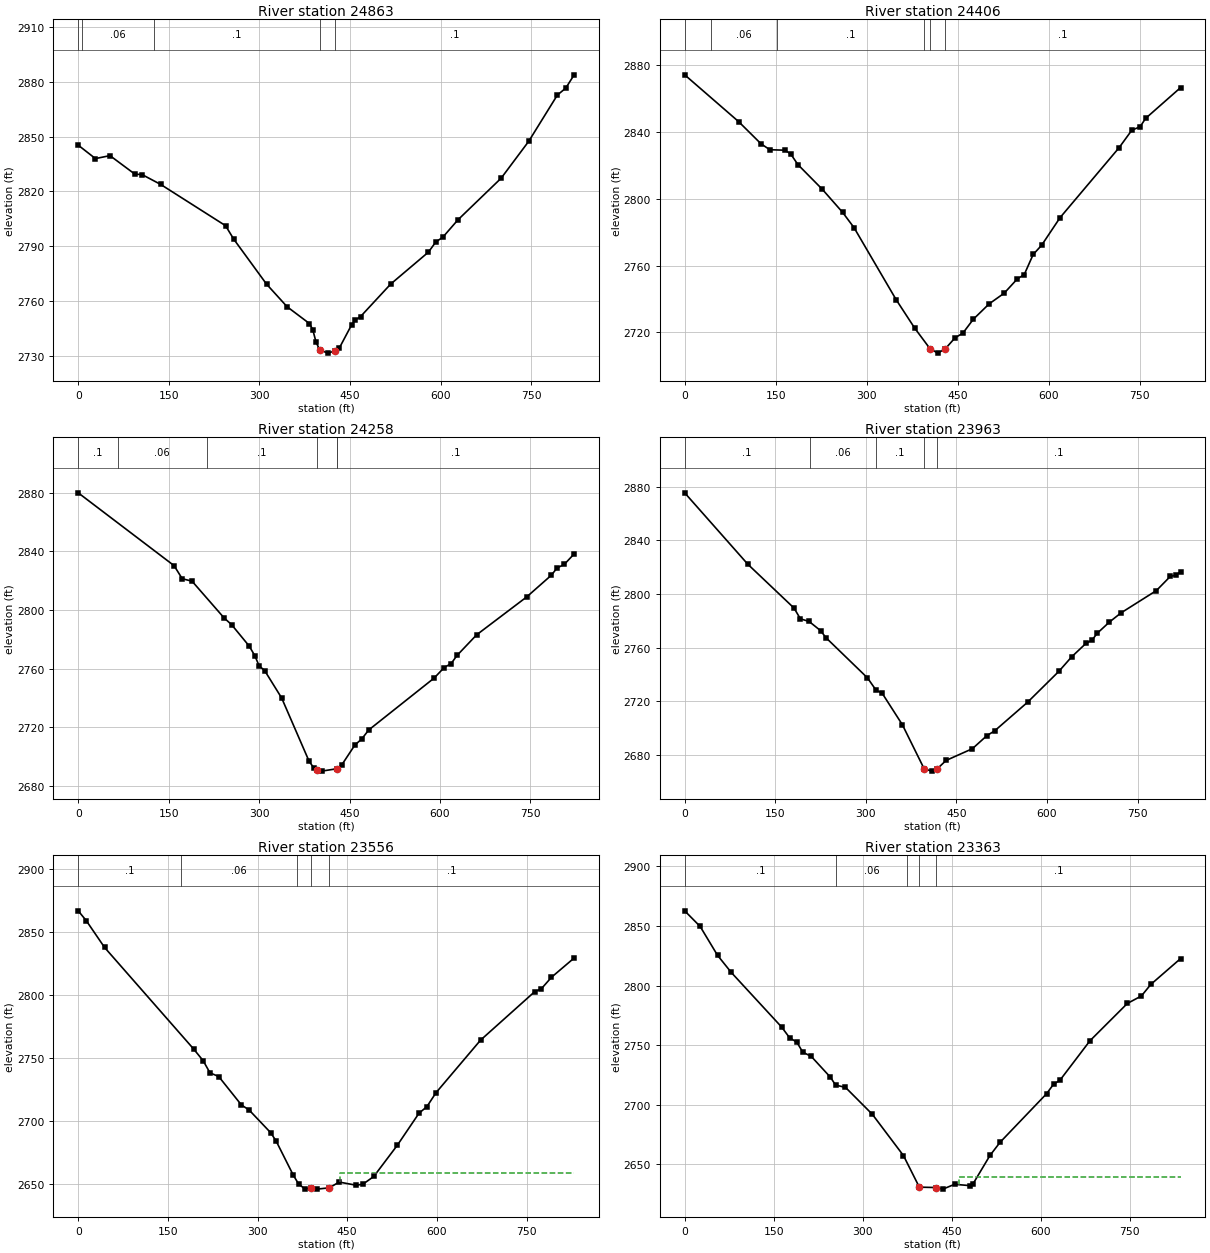
Type RM Length L Ch R = 1 ,24863   ,452.8,456.6,457.9
XS GIS Cut Line= 3
     2408837.828      655634.655     2409139.935      655354.937
     2409439.033      655075.623
#Sta/Elev= 30
       0 2845.33    28.5 2837.98    52.6  2839.6    93.9 2829.44   105.6 2829.24
   136.3 2823.88   243.9 2801.25   257.5 2793.85   311.8 2769.23   345.8 2756.87
   382.8 2747.66   388.3  2744.3   393.7  2737.5     400  2733.1   413.7 2731.47
   425.1 2732.76     432  2734.1   452.8 2747.09     459 2749.64   467.5 2751.52
   517.3 2769.29   579.8 2786.78     592 2792.35   603.4 2794.87   628.6 2804.44
   700.2 2827.27   745.8 2847.45   793.2 2872.76   807.1 2876.57     821 2883.84
#Mann= 5 ,-1 , 0
       0      .1       0     5.6     .06       0  124.82      .1       0
     400    .045       0   425.1      .1       0
Bank Sta=400,425.1
XS Rating Curve= 0 ,0
Exp/Cntr=0.3,0.1

Type RM Length L Ch R = 1 ,24406   ,144.1,148.4,154
XS GIS Cut Line= 2
2409076.08474245655926.1785703972409763.27915586655483.197595194
#Sta/Elev= 30
       0  2874.4    88.8 2846.38   125.8 2833.05   140.3  2829.5     165 2829.19
   174.5  2827.1   186.6 2820.59   227.1 2805.67   260.2 2791.99   279.2 2782.75
   348.7 2739.51   379.1 2722.55   404.22710.268   417.2  2707.5   429.7 2710.11
   445.8 2716.72   458.6 2719.48     476 2727.88     502 2737.06   526.7 2743.44
   548.3 2751.98   559.8 2754.61   574.5 2766.65   588.5 2772.22   618.8 2788.73
   716.2 2830.72     737 2841.12   750.9 2843.32   759.9 2848.28   817.6 2866.76
#Mann= 6 ,-1 , 0
       0      .1       0   42.97     .06       0  152.97      .1       0
   395.2      .1       0   404.2    .045       0   429.7      .1       0
Bank Sta=404.2,429.7
XS Rating Curve= 0 ,0
Exp/Cntr=0.3,0.1

Type RM Length L Ch R = 1 ,24258   ,298.8,295,289.5
XS GIS Cut Line= 2
     2409081.368      655945.494     2409874.643      655728.158
#Sta/Elev= 30
       0 2880.03     159 2830.31   172.5 2821.38   188.8  2819.7     242 2794.59
   254.4 2790.01   283.5 2775.43     293 2768.75     300 2761.93   309.3  2758.6
   337.4 2739.96     383 2696.67   390.6 2692.33   396.82690.709   403.7 2690.01
   429.22691.647   436.9 2694.13     459 2707.93   470.1 2711.89   481.8 2718.11
   590.4 2753.59   606.9 2760.72   618.5 2763.45   628.3 2769.02   660.8 2783.09
   743.8 2808.95   784.6 2823.75   794.3 2828.77     806 2831.11   822.5 2838.32
#Mann= 6 ,-1 , 0
       0      .1       0      66     .06       0  212.78      .1       0
   396.8    .045       0   429.2      .1       0   429.3      .1       0
Bank Sta=396.8,429.2
XS Rating Curve= 0 ,0
Exp/Cntr=0.3,0.1

Type RM Length L Ch R = 1 ,23963   ,407.5,406.7,406.9
XS GIS Cut Line= 3
     2409268.028       656329.01     2409606.824      656099.924
      2409948.49       655868.87
#Sta/Elev= 30
       0 2875.41   104.7 2822.16   181.2 2789.52   191.6 2781.57   206.1 2779.58
   225.2 2772.71   233.9 2767.55   302.7 2737.59   317.1 2728.32   326.8 2726.34
   360.6 2702.63   396.5 2669.96   408.9 2668.11   418.5 2669.94     433 2676.08
   476.5 2684.81   500.6 2694.57   513.4 2698.11   568.1  2719.5     620 2742.55
   640.7 2753.13   664.8 2763.34   674.5 2765.62   683.3 2770.79   703.4 2779.13
   722.8 2786.01   781.3 2802.61   804.3 2813.15   814.5 2814.21   821.4  2816.8
#Mann= 5 ,-1 , 0
       0      .1       0  206.89     .06       0  316.35      .1       0
   396.5    .045       0   418.5      .1       0
Bank Sta=396.5,418.5
XS Rating Curve= 0 ,0
Exp/Cntr=0.3,0.1

Type RM Length L Ch R = 1 ,23556   ,191.2,193.3,188.7
XS GIS Cut Line= 2
2409577.10981196656639.3598119582410220.15441529656115.141601385
#Sta/Elev= 30
       0 2866.58    13.4 2858.85    44.1 2837.58   193.1 2757.17     209 2747.93
   220.4 2738.32     235 2735.41     273 2712.89   285.8 2708.93   322.1 2690.86
   331.3 2684.13   359.7 2657.36   368.5 2650.48   378.8 2646.47   389.2 2647.07
   399.5 2646.25   420.1  2647.3   436.5 2651.85   464.9 2649.35   476.3 2650.18
   494.5  2656.3   533.7 2680.91   570.1 2706.38   583.2  2711.5   598.5 2722.57
     673 2764.19   763.4 2802.49   774.8 2804.91   791.7 2813.99   829.6 2829.23
#Mann= 5 ,-1 , 0
       0      .1       0  172.69     .06       0   365.7      .1       0
   389.2    .045       0   420.1      .1       0
#XS Ineff= 2 , 0
                          438.23         2658.63
Permanent Ineff=
       F       F
Bank Sta=389.2,420.1
XS Rating Curve= 0 ,0
Exp/Cntr=0.3,0.1

Type RM Length L Ch R = 1 ,23363   ,154.6,150,146.6
XS GIS Cut Line= 3
2409721.44384271656792.745685424     2410025.753      656507.812
     2410321.387      656210.556
#Sta/Elev= 30
       0 2862.58    26.1 2849.47    55.4 2825.29    78.6 2810.91   163.5 2765.15
   177.1 2756.06     189 2752.58   199.1 2744.13   213.4 2740.58   245.6 2723.19
   254.4 2716.55   271.1 2714.62   316.4 2692.04   368.9 2657.41   395.6    2631
   423.8 2630.69   435.3 2629.35     455 2633.39   480.2 2632.32   486.4    2634
   514.7 2657.57   531.7 2668.59     610 2709.24   621.9 2717.26   632.6 2720.56
   683.3 2753.71   746.3 2784.96     770 2791.25   785.9 2800.92   836.1 2822.59
#Mann= 5 ,-1 , 0
       0      .1       0  255.01     .06       0  374.68      .1       0
   395.6    .045       0   423.8      .1       0
#XS Ineff= 2 , 0
                          462.47         2639.28
Permanent Ineff=
       F       F
Bank Sta=395.6,423.8
XS Rating Curve= 0 ,0
Exp/Cntr=0.3,0.1