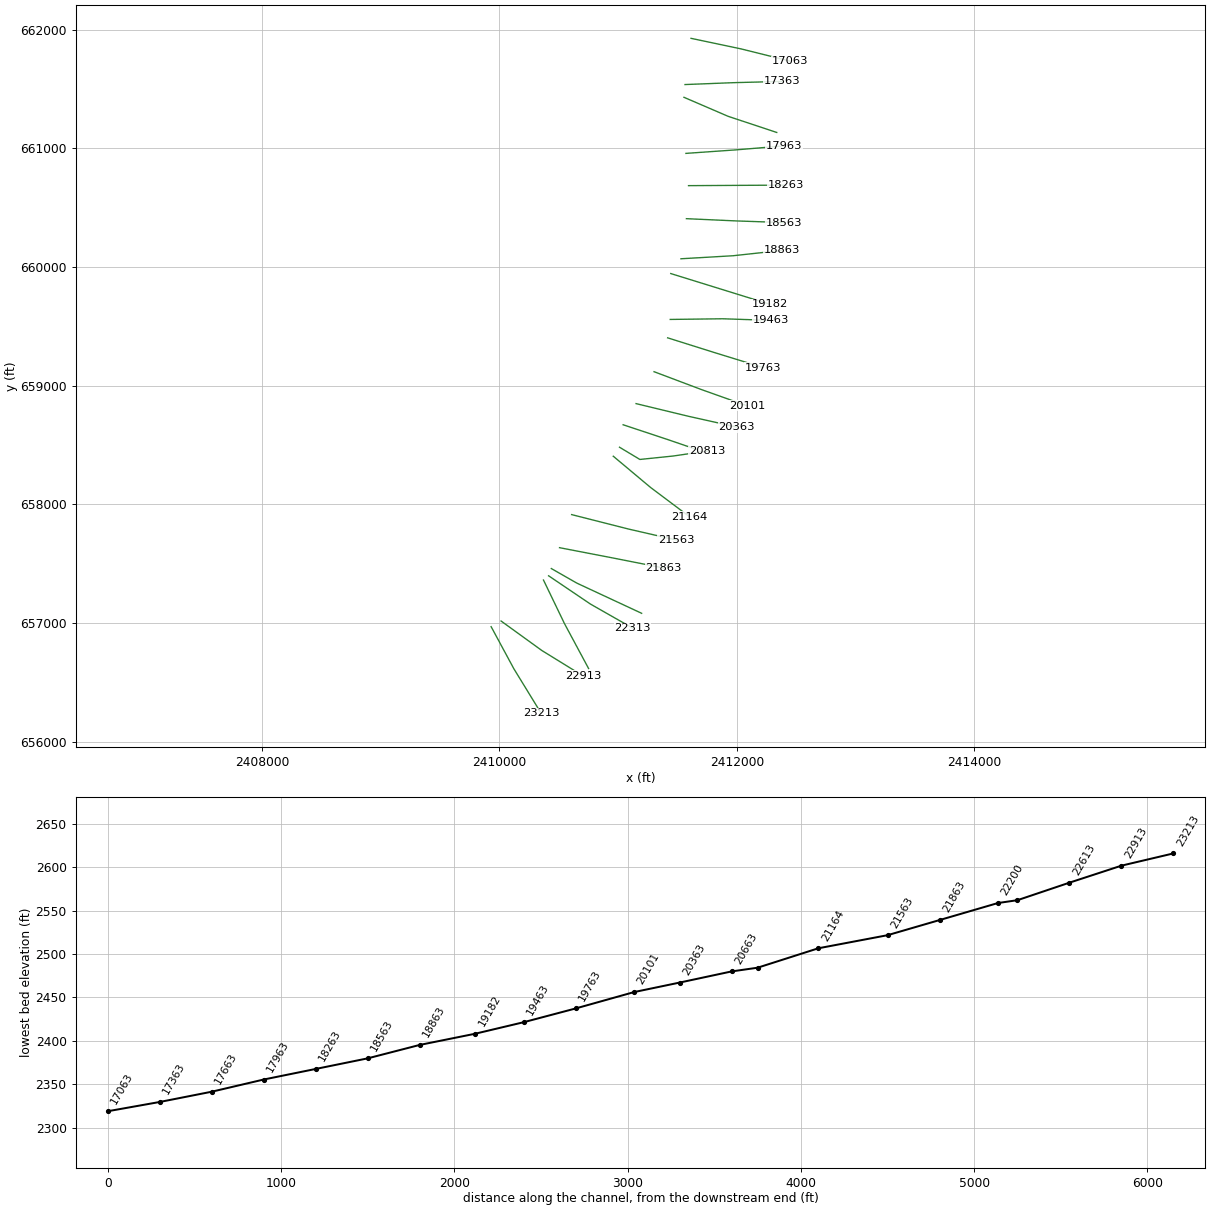
HEC-RAS study BRUSHRN.prj: BRUSHRN

--- BRUSHRN.g01 (geometry) --- (continued)

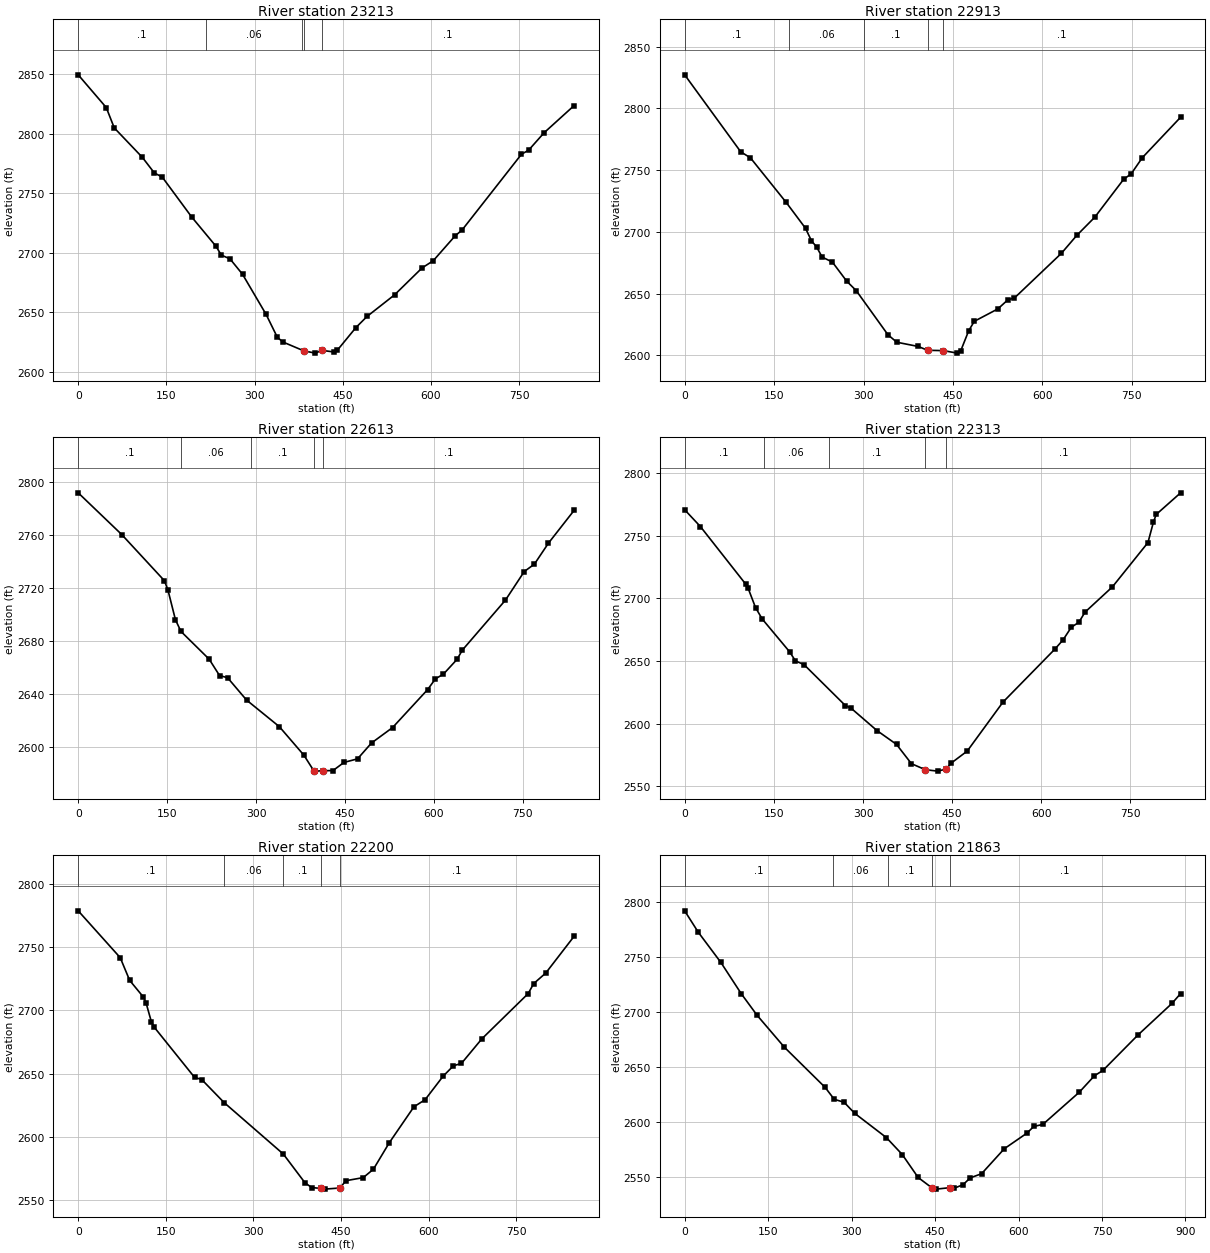
Type RM Length L Ch R = 1 ,23213   ,292.1,300,304
XS GIS Cut Line= 3
2409930.88656023656968.828094022     2410122.531      656613.787
      2410352.59      656238.408
#Sta/Elev= 30
       0 2849.56    47.7 2822.09    61.3 2805.01   109.2  2780.2   129.5 2767.16
     143 2763.65   193.1 2730.12   234.5  2705.5   243.4 2698.17   258.2 2694.99
   279.5 2682.08   319.7 2648.29   338.6 2629.27   347.7 2625.28     384 2617.69
   403.5 2615.82   414.5 2618.17   434.5 2616.81   440.6 2618.13   472.5 2637.33
   491.3  2646.6   538.2 2664.78   585.1 2687.43   603.9 2693.38   641.3 2714.35
     653 2719.21     754  2782.8   766.4 2786.36   792.6 2800.93   843.7 2823.77
#Mann= 5 ,-1 , 0
       0      .1       0  217.15     .06       0  380.04      .1       0
     384    .045       0   414.5      .1       0
Bank Sta=384,414.5
XS Rating Curve= 0 ,0
Exp/Cntr=0.3,0.1

Type RM Length L Ch R = 1 ,22913   ,303.6,300,295
XS GIS Cut Line= 3
2410014.56276885657016.681838389     2410357.576      656768.391
     2410705.237      656553.889
#Sta/Elev= 30
       0 2827.12      94 2764.79   110.3  2759.9   170.4 2723.72   202.7 2702.85
   212.6 2692.78   221.4 2687.65   230.6 2679.52   247.8 2675.46   271.8 2660.02
   287.9 2652.28   340.9 2616.67   355.8 2610.55   391.9 2607.11   407.62604.014
   434.1 2603.75   457.4 2601.72   463.2 2603.69   476.5 2619.88   485.9 2627.49
   525.3 2637.51   542.3 2644.94   553.3 2646.42     632 2682.56   657.9 2697.13
     688 2711.81   736.4 2742.49   749.1 2746.96   767.9  2760.1     832 2792.78
#Mann= 5 ,-1 , 0
       0      .1       0  175.47     .06       0  301.41      .1       0
   407.6    .045       0   434.1      .1       0
Bank Sta=407.6,434.1
XS Rating Curve= 0 ,0
Exp/Cntr=0.3,0.1

Type RM Length L Ch R = 1 ,22613   ,290.5,300,305.8
XS GIS Cut Line= 3
     2410371.585      657361.961     2410547.269      656997.042
 2410751.3349421656616.700985526
#Sta/Elev= 30
       0 2791.61    73.6 2760.13   145.5 2725.42   151.5 2718.24     164 2696.11
   173.3 2687.31   220.9  2666.4   238.4 2654.11     252 2652.44   283.9 2635.68
   339.3 2615.62   380.8 2594.11   397.52582.354   400.2 2582.16   412.52582.469
   429.8 2582.59   448.3 2588.71   471.2  2591.4   494.8 2603.34   530.3 2614.95
   589.4 2643.51   602.6 2651.64     616 2655.12     639 2666.25     648 2673.24
   720.7 2710.86   752.4 2732.36   769.6 2737.98   793.2 2753.71   836.6 2778.46
#Mann= 5 ,-1 , 0
       0      .1       0  173.62     .06       0  292.03      .1       0
   397.5    .045       0   412.5      .1       0
Bank Sta=397.5,412.5
XS Rating Curve= 0 ,0
Exp/Cntr=0.3,0.1

Type RM Length L Ch R = 1 ,22313   ,109.2,113.1,113.7
XS GIS Cut Line= 3
2410414.69492763657397.665932453     2410767.539      657159.156
     2411122.527      656956.954
#Sta/Elev= 30
       0  2770.9    26.4 2757.51   102.9 2711.32   106.3 2708.74   119.2 2692.72
   130.4 2683.63   176.4 2657.46   186.4  2650.1   200.8 2647.13   270.4 2614.39
   280.1 2612.25   323.5 2594.43   356.4 2583.37   381.5 2567.95   404.9 2563.15
   425.5    2562   440.2 2563.63     448 2568.27   475.4 2578.04   535.5 2617.15
   622.9 2659.54   636.6 2666.89   650.5    2677   663.1 2680.93   673.6 2689.09
   719.6 2709.25   779.4 2744.65   788.6 2760.92   793.3 2767.14   834.4 2784.44
#Mann= 5 ,-1 , 0
       0      .1       0  133.05     .06       0   242.5      .1       0
   404.9    .045       0   440.2      .1       0
Bank Sta=404.9,440.2
XS Rating Curve= 0 ,0
Exp/Cntr=0.3,0.1

Type RM Length L Ch R = 1 ,22200   ,331.7,336.9,339.4
XS GIS Cut Line= 3
 2410437.8410818657458.5625939432410652.91133869657335.766704695
2411198.03991061657081.657292265
#Sta/Elev= 30
       0 2778.52    71.9 2741.54    88.1 2723.59   111.6  2710.4   116.2 2705.71
   125.4 2690.65     130 2686.68   199.1 2647.02   211.5 2645.23   249.7 2627.09
   351.2 2586.38   388.2 2563.73   399.7 2559.96   416.12559.187   421.8 2558.69
   448.5  2559.6     458 2565.32     488 2567.79   505.4  2574.4   532.6 2595.34
   574.8 2623.74   593.9 2629.32   624.8 2647.93   642.5 2656.15   656.1 2657.98
     691 2677.36   770.4 2713.16   779.9 2721.08   800.5 2729.38   849.1 2758.46
#Mann= 5 ,-1 , 0
       0      .1       0   249.7     .06       0   351.2      .1       0
   416.1    .045       0   448.5      .1       0
Bank Sta=416.1,448.5
XS Rating Curve= 0 ,0
Exp/Cntr(USF)=0,0
Exp/Cntr=0.3,0.1

Type RM Length L Ch R = 1 ,21863   ,300,300,296.4
XS GIS Cut Line= 3
 2410506.8472335657634.527887171     2410956.776      657547.737
2411381.60891017657463.857432713
#Sta/Elev= 30
       0  2792.1    24.3 2772.73    65.1 2745.14   101.7 2716.73   130.3 2697.03
   179.1 2668.15   252.5 2631.55   268.8 2620.74   286.5 2618.07   305.4 2608.08
   362.5 2585.93     391 2570.57   419.6 2549.67   443.6 2540.54   452.1 2539.09
   476.5 2540.41   484.7 2539.98   500.3 2543.13   513.2 2549.32   533.6 2553.11
   574.4  2575.8   615.2 2590.03   627.3 2596.03   643.7 2597.93   709.2 2627.21
   736.4 2642.14   751.7 2647.02   814.9 2679.34   875.6 2707.86   891.3 2716.87
#Mann= 5 ,-1 , 0
       0      .1       0  266.43     .06       0  365.79      .1       0
   443.6    .045       0   476.5      .1       0
Bank Sta=443.6,476.5
XS Rating Curve= 0 ,0
Exp/Cntr=0.3,0.1

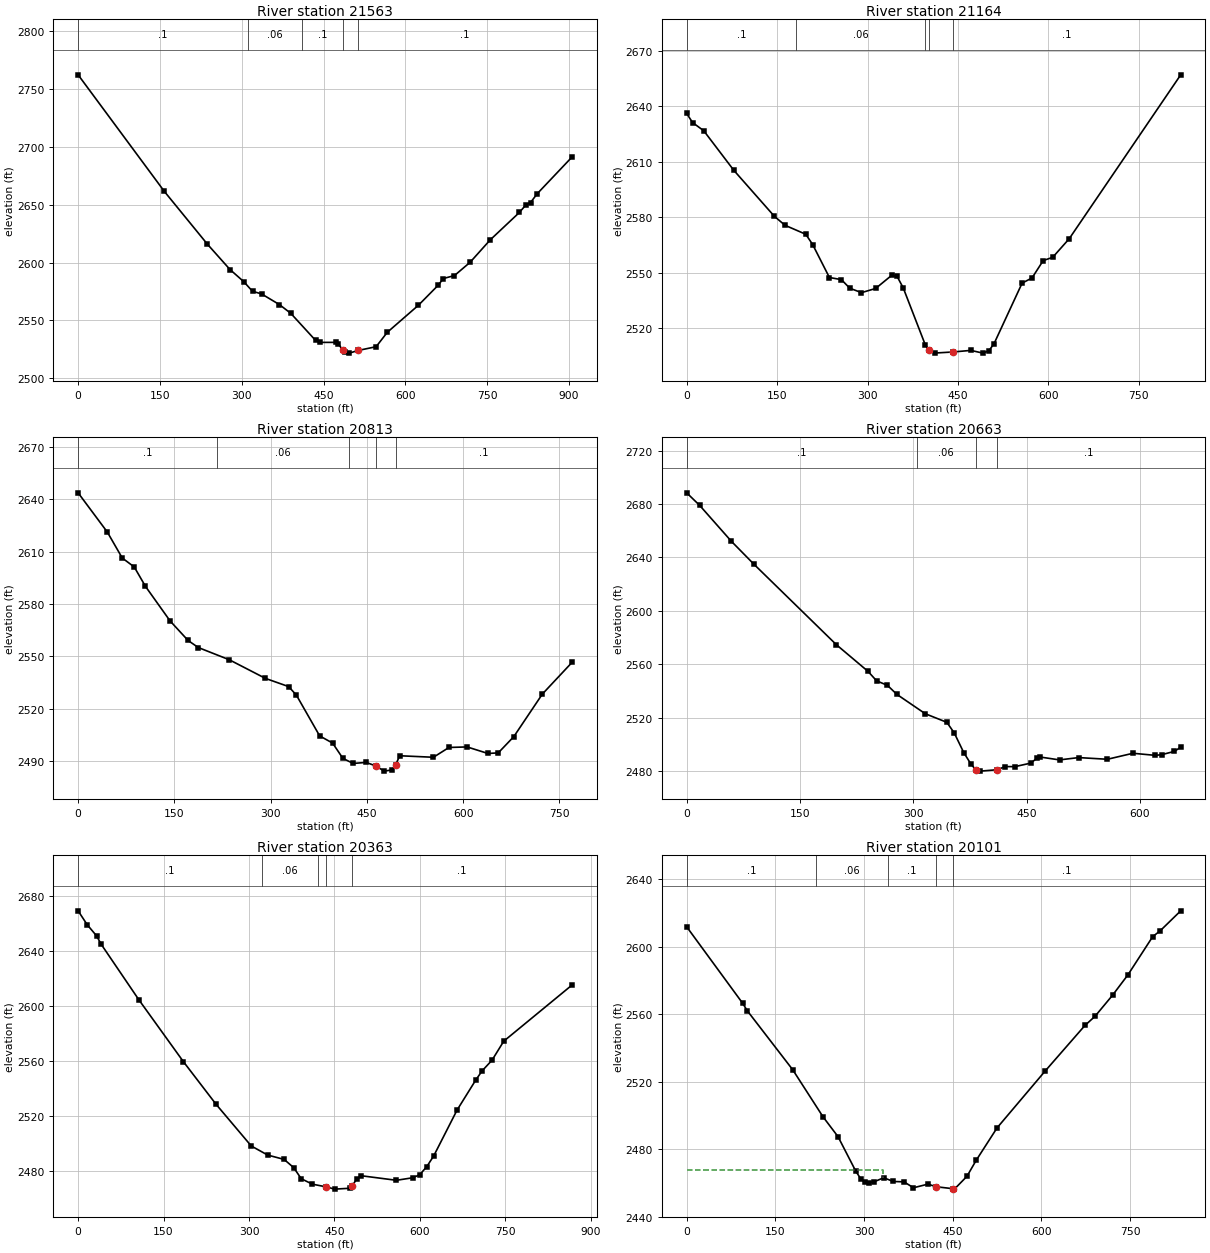
Type RM Length L Ch R = 1 ,21563   ,404.9,399.3,391.3
XS GIS Cut Line= 3
2410608.76760919657913.211787708     2411090.353      657790.925
      2411489.13      657699.375
#Sta/Elev= 30
       0 2762.29   158.2 2661.45   237.2 2615.81   278.5 2593.97   303.8 2583.46
   319.8 2575.15   336.3 2572.91   369.3 2563.61     390 2556.09   435.4 2532.73
   443.6 2530.98   472.5 2530.99   477.5 2529.56   484.9 2524.53     489 2522.51
   497.3 2521.69   513.3 2523.97   546.5 2527.24     567 2539.69   624.1  2563.1
   660.8 2580.62   669.6 2586.18   690.2 2588.75   718.9 2600.25   755.8 2619.63
   809.2  2643.3     821 2649.77   829.7 2651.91     842 2659.54     906 2691.37
#Mann= 5 ,-1 , 0
       0      .1       0  310.82     .06       0  410.52      .1       0
   484.9    .045       0   513.3      .1       0
Bank Sta=484.9,513.3
XS Rating Curve= 0 ,0
Exp/Cntr=0.3,0.1

Type RM Length L Ch R = 1 ,21164   ,337.7,350.7,357.2
XS GIS Cut Line= 3
2410959.32920747658405.1353039632411273.08720747658142.183303963
2411601.08420747657895.832303963
#Sta/Elev= 30
       0 2636.14     9.7 2631.24    28.4 2626.76    78.2 2605.41   145.4 2580.59
     163 2575.73   197.6 2570.85     209 2565.31   236.8 2547.49   256.7 2546.34
   270.6  2541.7     290 2539.31   313.5 2541.57   339.8 2548.58   348.9 2548.18
   359.3 2541.85   395.8 2511.15   401.9 2508.14   411.4 2506.67   441.4 2507.24
   471.5 2508.11   491.5 2506.63   501.5 2507.97     510 2511.79   556.5 2544.47
   572.9 2547.24   591.5 2556.65   607.2 2558.39   634.7 2568.47   819.6    2657
#Mann= 5 ,-1 , 0
       0      .1       0  181.11     .06       0  395.95      .1       0
   401.9    .045       0   441.4      .1       0
Bank Sta=401.9,441.4
XS Rating Curve= 0 ,0
Exp/Cntr=0.3,0.1

Type RM Length L Ch R = 1 ,20813   ,154.3,150,142.2
XS GIS Cut Line= 4
     2411011.769       658480.912411183.42894969658377.852560834
     2411461.894      658406.6062411748.71614576658448.416174409
#Sta/Elev= 30
       0 2643.71    45.5 2621.24    68.8 2606.36    87.5 2601.23   104.9 2590.15
   143.4 2570.29   171.4 2559.12   187.3 2555.08   235.7 2548.06     292 2537.39
   328.2 2532.69   340.3 2527.74   376.5 2504.44   396.6 2500.35   412.7 2491.57
   428.7 2488.67   448.9 2489.26   463.72487.282     477 2484.27   489.1 2484.95
     495 2487.94   501.2 2493.08   553.8 2492.21     578 2497.83   606.3 2498.13
   638.7 2494.39   654.8 2494.72   679.1 2504.05   723.6 2528.44     770 2546.64
#Mann= 5 ,-1 , 0
       0      .1       0  216.14     .06       0  421.88      .1       0
   463.7    .045       0     495      .1       0
Bank Sta=463.7,495
XS Rating Curve= 0 ,0
Exp/Cntr=0.3,0.1

Type RM Length L Ch R = 1 ,20663   ,298.2,300,306.6
XS GIS Cut Line= 3
     2411042.495      658670.098     2411418.577      658545.287
2411662.60250508658461.578264239
#Sta/Elev= 30
       0 2688.33    17.1 2678.98    59.3 2651.98    88.8 2635.02   198.3 2574.59
   240.1 2554.68   251.5 2547.58   265.8 2544.21   278.4 2537.42     316 2522.93
   344.5 2516.53   354.3 2508.59   366.9 2493.87   376.1 2485.54   382.5 2481.16
   388.8 2479.98   410.9 2481.01   421.8 2483.38   434.5 2483.33   455.6 2485.98
   464.1 2489.74   468.3 2490.51   493.7 2488.39   519.1 2490.12   557.1 2488.86
     591 2493.35   620.6 2491.78     629  2492.3   645.9 2494.77   654.2 2497.94
#Mann= 4 ,-1 , 0
       0      .1       0  304.45     .06       0   382.5    .045       0
   410.9      .1       0
Bank Sta=382.5,410.9
XS Rating Curve= 0 ,0
Exp/Cntr=0.3,0.1

Type RM Length L Ch R = 1 ,20363   ,263.5,262.2,256.2
XS GIS Cut Line= 3
2411151.30798361658848.320698868     2411589.015      658742.436
     2411995.897      658651.408
#Sta/Elev= 30
       0 2669.42    15.9 2659.34    32.3 2651.27    40.6 2645.05   106.4 2604.91
   184.6 2559.91   242.2 2528.79     304  2498.5   332.8 2491.91   361.6 2488.75
   378.5 2482.77   391.7 2474.72     411 2470.78   435.7 2468.77   450.3 2467.15
   476.7 2467.77   480.8 2469.17     489 2474.58   497.2 2476.87   558.8 2473.57
   587.4 2475.41   599.7 2477.61   612.2 2483.58   624.3 2491.31   665.2 2524.58
     698 2546.39   709.3 2553.14   726.7  2560.9   747.2 2574.67   867.3 2615.56
#Mann= 5 ,-1 , 0
       0      .1       0  321.95     .06       0  421.56      .1       0
   435.7    .045       0   480.8      .1       0
Bank Sta=435.7,480.8
XS Rating Curve= 0 ,0
Exp/Cntr=0.3,0.1

Type RM Length L Ch R = 1 ,20101   ,336.5,337.8,337.2
XS GIS Cut Line= 3
2411302.84978217659117.2492944122411703.31378217658966.175294412
2412087.43240759658829.453081981
#Sta/Elev= 30
       0 2611.87    94.9  2566.4   102.5 2562.07   179.4 2527.06   230.7 2499.11
     256 2487.38   286.3 2466.72   294.9 2462.17   301.3 2460.64   307.7 2460.15
   316.3 2460.49   333.4 2463.01   349.4 2460.77   367.6 2460.57   383.6 2457.05
   408.4 2459.22   421.4 2457.67   449.7 2456.53   452.9 2456.24   474.1 2463.84
   489.6 2473.26   525.1 2492.61   606.2 2526.22   673.7 2553.34   690.7 2558.75
   720.4 2571.27   746.4 2583.36   788.3 2606.03     801  2609.5   835.7 2621.34
#Mann= 5 ,-1 , 0
       0      .1       0  218.82     .06       0  340.15      .1       0
   421.4    .045       0   449.7      .1       0
#XS Ineff= 2 , 0
          332.05 2467.34
Permanent Ineff=
       F       F
Bank Sta=421.4,449.7
XS Rating Curve= 0 ,0
Exp/Cntr=0.3,0.1

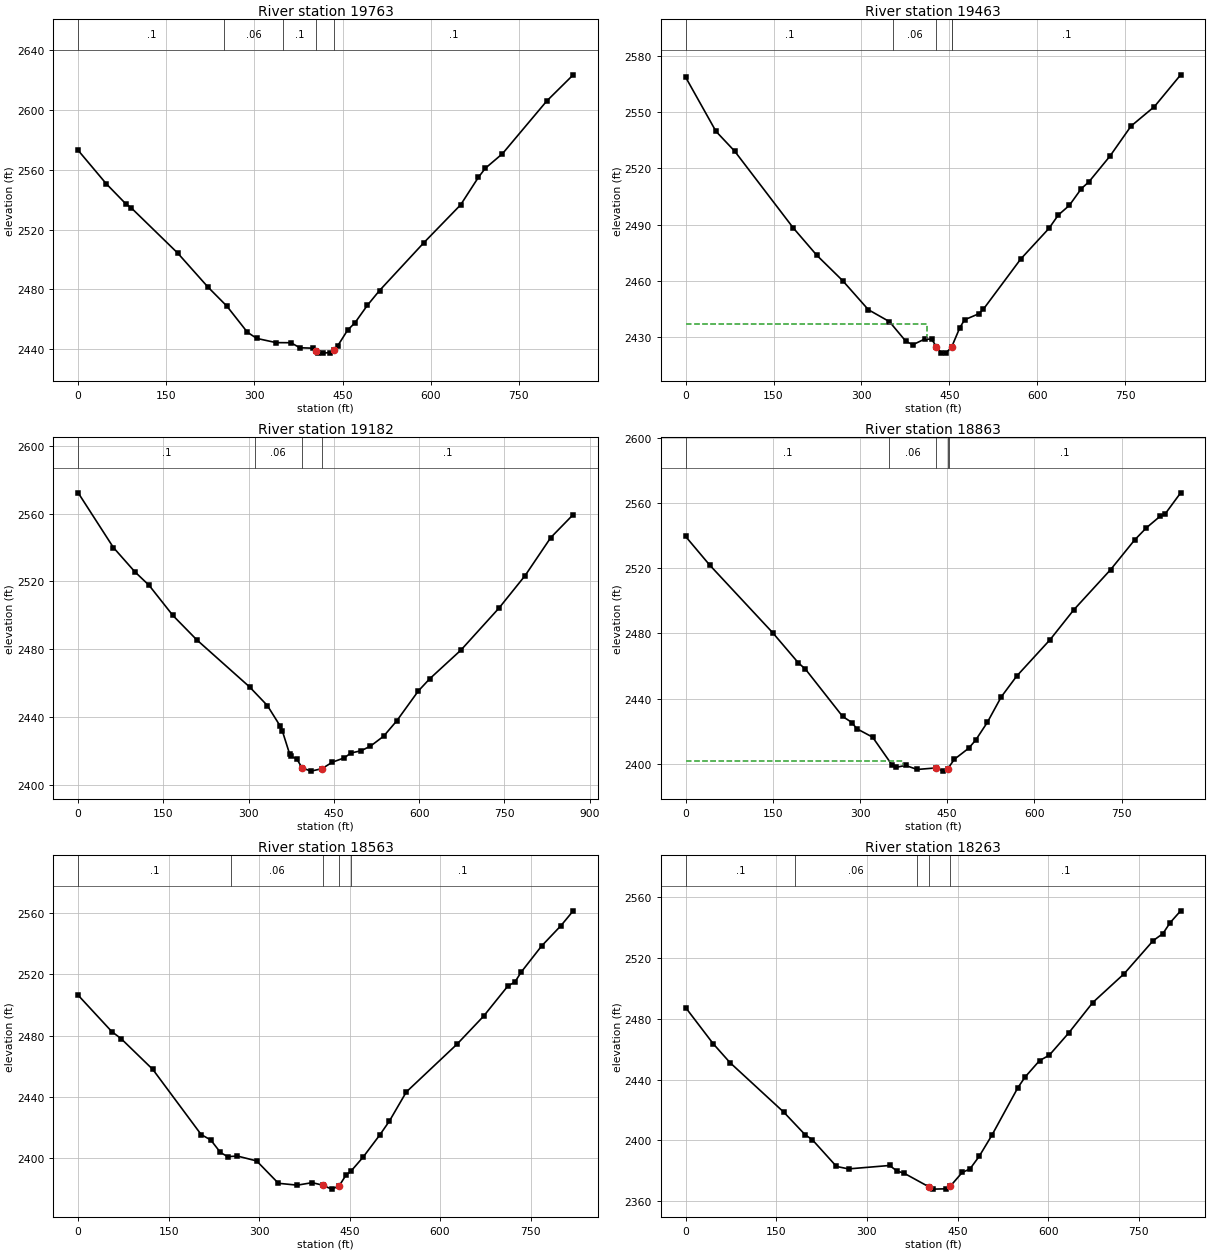
Type RM Length L Ch R = 1 ,19763   ,294.6,300,302.7
XS GIS Cut Line= 3
     2411417.281      659402.621     2411816.176      659276.983
2412221.86962586659152.038006279
#Sta/Elev= 30
       0 2573.07    47.7 2550.77    81.2 2537.22    90.3  2534.6   169.3 2504.37
     221 2481.54   253.2 2468.78     288 2451.37   303.9 2447.22     337 2444.39
   362.2 2444.32   377.3 2440.95   399.6 2440.67   404.1 2439.01   408.3 2437.73
   416.7 2437.36   429.3 2437.76   434.7 2439.12   441.8 2442.24   458.6 2452.72
   471.1 2457.63   492.3 2469.37     513 2479.26   588.3 2511.22   651.1 2536.64
   681.1 2554.92     693 2561.06   722.3 2570.86   797.6 2606.09   842.7 2623.63
#Mann= 5 ,-1 , 0
       0      .1       0  249.08     .06       0  349.45      .1       0
   404.1    .045       0   434.7      .1       0
Bank Sta=404.1,434.7
XS Rating Curve= 0 ,0
Exp/Cntr=0.3,0.1

Type RM Length L Ch R = 1 ,19463   ,285.6,281.1,273.2
XS GIS Cut Line= 3
     2411438.947       659557.64     2411880.347      659563.229
2412283.40532517  659549.9110339
#Sta/Elev= 30
       0 2568.55    51.8 2539.69    83.8 2529.09   183.8 2488.19   223.8 2473.68
   267.8  2460.2   311.8 2444.67   347.8  2438.3   375.8 2427.84   387.8 2426.01
   407.7 2428.99   419.8 2428.94     428 2424.94   435.8 2421.85   443.8 2421.53
   453.82424.695   467.8    2435   475.9 2439.28   499.9 2442.45   507.9 2444.85
   571.9  2471.7   619.9 2487.95   635.9 2495.09   654.7 2500.22   675.3 2509.18
   688.2  2512.8     724 2526.45     760 2542.47     800 2552.89   844.7 2569.79
#Mann= 5 ,-1 , 0
       0      .1       0  354.55     .06       0     428    .045       0
   453.8     .06       0  455.28      .1       0
#XS Ineff= 2 , 0
          412.73 2437.31
Permanent Ineff=
       F       F
Bank Sta=428,453.8
XS Rating Curve= 0 ,0
Exp/Cntr=0.3,0.1

Type RM Length L Ch R = 1 ,19182   ,316.7,318.9,321.5
XS GIS Cut Line= 2
2411443.50594162659944.1580734442412275.54667483659686.241131826
#Sta/Elev= 30
       0  2572.2      62 2539.96    99.7 2525.69   124.8 2517.69   166.7 2499.93
   208.6 2485.61   301.5 2457.87   332.9 2446.87   355.3 2434.86   359.4 2431.75
   371.9 2418.51   374.4  2416.9   384.5 2415.49     3942410.136   409.6 2408.22
   428.8 2409.64   447.3 2413.49   468.2 2416.03   479.9  2418.9   497.5 2420.18
   514.3 2422.93   537.5  2428.8   560.4 2437.77   598.7 2455.52     619 2462.77
   673.4  2479.5   740.4 2504.26   786.5 2523.46   831.6 2545.84   871.1 2559.39
#Mann= 4 ,-1 , 0
       0      .1       0  310.31     .06       0     394    .045       0
   428.8      .1       0
Bank Sta=394,428.8
XS Rating Curve= 0 ,0
Exp/Cntr=0.3,0.1

Type RM Length L Ch R = 1 ,18863   ,300.4,300,298.1
XS GIS Cut Line= 3
2411529.07533921 660068.80398301     2411967.229      660094.232
2412377.48453373660138.770780847
#Sta/Elev= 30
       0 2539.66    41.4 2522.08   149.9 2480.44     194 2461.92     206 2458.13
   270.1 2429.01   286.2 2425.24   294.2 2421.51   321.7 2416.26   355.7 2398.88
   362.3  2397.7   378.3  2398.9   398.3  2396.4   431.5 2397.38   442.4 2395.38
   451.1 2396.97   462.5 2402.71   486.7 2409.39   498.8 2414.35   518.9 2425.28
     543 2441.04   569.7 2453.87   627.2 2476.29   667.7 2494.53     731 2519.21
   772.4  2537.5   792.5 2544.93   816.5 2552.14   824.7 2553.41   851.6 2566.48
#Mann= 5 ,-1 , 0
       0      .1       0  350.42     .06       0   431.5    .045       0
   451.1     .06       0  452.33      .1       0
#XS Ineff= 2 , 0
          374.56 2401.39
Permanent Ineff=
       F       F
Bank Sta=431.5,451.1
XS Rating Curve= 0 ,0
Exp/Cntr=0.3,0.1

Type RM Length L Ch R = 1 ,18563   ,299.6,300,301.4
XS GIS Cut Line= 3
2411575.09928697660406.582826307     2411986.619      660387.965
     2412395.217      660373.806
#Sta/Elev= 30
       0 2506.34    55.7 2482.66    71.2 2478.03   123.8 2457.96   203.9 2415.53
   219.9 2411.96   235.9 2403.83   247.9 2401.11   263.9 2401.51   295.9 2398.33
     332 2383.74   363.3 2382.53     388 2384.16   405.4 2382.52   420.1 2379.94
   432.4 2381.89     444 2389.04   452.1 2391.56   472.1 2400.64   500.1 2415.26
   516.1 2424.37   544.1  2443.3   628.2 2474.47   672.2  2492.7   712.2 2512.25
   724.3 2515.06   734.2 2521.27   768.3 2538.42   800.3 2551.65   820.8 2561.38
#Mann= 5 ,-1 , 0
       0      .1       0  253.08     .06       0   405.4    .045       0
   432.4     .06       0   453.1      .1       0
Bank Sta=405.4,432.4
XS Rating Curve= 0 ,0
Exp/Cntr=0.3,0.1

Type RM Length L Ch R = 1 ,18263   ,299.3,300,301.7
XS GIS Cut Line= 3
     2411593.113      660684.963     2412002.607      660687.178
     2412412.101      660689.393
#Sta/Elev= 30
       0 2487.45    45.6 2463.62    73.6 2451.08   162.7 2418.37   197.6 2403.66
   209.6 2400.33   249.6  2382.7   269.6 2381.08   337.5 2383.34   349.6 2379.71
   361.7 2378.19     4022369.378   409.6 2367.75     430 2367.95   437.6 2369.55
   457.6 2378.74   470.3    2381   485.6 2389.31   506.5 2403.14   549.6 2434.56
   561.6 2441.63   585.6 2452.48   601.6 2456.01   633.6 2470.59   673.6 2490.75
   725.6 2509.78   773.6 2531.58   789.6 2536.16   801.6  2543.4     819  2551.2
#Mann= 5 ,-1 , 0
       0      .1       0  181.34     .06       0  382.75      .1       0
     402    .045       0   437.6      .1       0
Bank Sta=402,437.6
XS Rating Curve= 0 ,0
Exp/Cntr=0.3,0.1

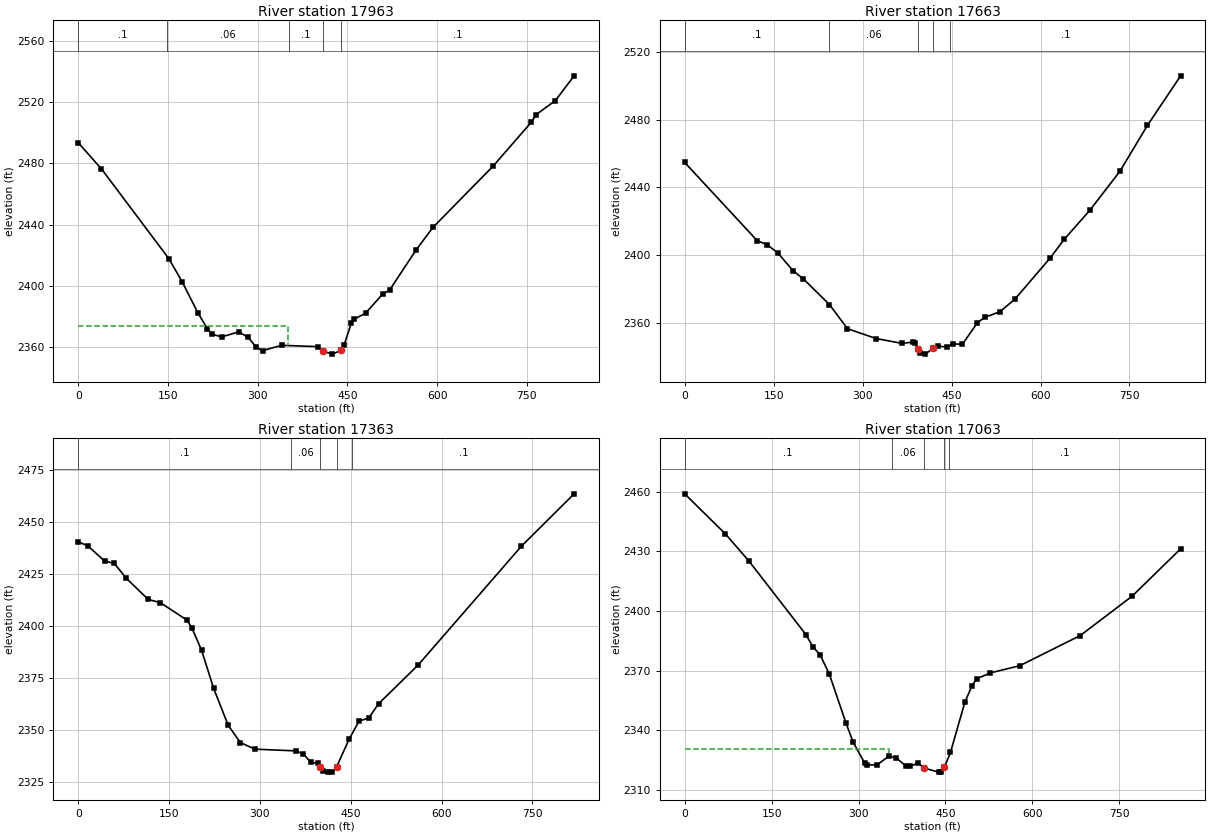
Type RM Length L Ch R = 1 ,17963   ,304.1,300,293.7
XS GIS Cut Line= 3
2411571.33786092660956.762695405     2411991.377      660986.241
     2412398.019      661020.221
#Sta/Elev= 30
       0 2493.41    38.9 2476.31   151.8 2417.68   173.9 2402.64   199.9 2382.61
   215.9  2372.1     224 2368.49     240 2366.82   268.1 2370.06   284.1 2366.58
   297.4 2360.14   308.2 2357.88   340.2 2361.31   400.4 2360.47   408.4 2357.59
   424.5 2355.58   439.6 2357.97   444.5 2361.53   456.6 2375.84   460.6 2378.19
   480.4 2382.29   508.7 2394.62   520.8 2397.46   564.9 2423.53     593 2438.18
   693.4 2478.06   757.6 2506.82   765.6 2511.71   797.7 2520.89   829.1 2537.01
#Mann= 5 ,-1 , 0
       0      .1       0  148.46     .06       0  352.51      .1       0
   408.4    .045       0   439.6      .1       0
#XS Ineff= 2 , 0
           350.1 2373.79
Permanent Ineff=
       F       F
Bank Sta=408.4,439.6
XS Rating Curve= 0 ,0
Exp/Cntr=0.3,0.1

Type RM Length L Ch R = 1 ,17663   ,294.8,300,304.5
XS GIS Cut Line= 3
     2411554.614      661429.271     2411926.216      661269.152
2412335.76920013661133.111887352
#Sta/Elev= 30
       0 2454.67   122.1 2408.57   139.5    2406   157.2 2401.21   183.1 2390.61
   199.8 2386.07   244.1  2370.8   274.5 2356.56   322.5 2350.77     366 2347.92
   385.4 2348.64   387.8  2348.4   393.7 2344.74   397.6 2342.43   405.2 2341.55
   419.5 2344.94   426.3 2346.17   443.1 2345.82   451.6 2347.57   468.4 2347.41
   493.7 2360.13   506.3  2363.3   531.6  2366.6   556.9 2374.03   615.7 2398.03
   640.2  2409.4   683.4 2426.53     734 2449.54   780.3 2476.57   836.2 2505.78
#Mann= 5 ,-1 , 0
       0      .1       0  244.01     .06       0   393.7    .045       0
   419.5     .06       0  448.04      .1       0
Bank Sta=393.7,419.5
XS Rating Curve= 0 ,0
Exp/Cntr=0.3,0.1

Type RM Length L Ch R = 1 ,17363   ,301.9,300,295.1
XS GIS Cut Line= 3
     2411563.233      661536.679     2411972.416      661552.599
     2412381.824      661563.101
#Sta/Elev= 30
       0 2440.45    15.5 2438.61    43.5 2431.26    59.6 2430.06    79.6 2422.88
   115.6 2412.75   135.6 2411.22   179.6 2402.82   187.7 2399.06   203.7 2388.38
   223.7 2369.97   247.7 2352.23   267.7 2343.98   291.7 2340.78   359.6 2339.95
   371.8 2338.49   383.8 2334.53   395.8 2333.95   399.8 2332.18   403.8 2330.47
   411.8 2329.74   419.8 2329.89   426.62332.247   447.8 2345.81   463.8 2354.29
   479.8 2355.75   495.9 2362.56   561.5 2381.28   731.9 2438.35     819 2463.53
#Mann= 5 ,-1 , 0
       0      .1       0  351.64     .06       0   399.8    .045       0
   426.6     .06       0  452.86      .1       0
Bank Sta=399.8,426.6
XS Rating Curve= 0 ,0
Exp/Cntr=0.3,0.1

Type RM Length L Ch R = 1 ,17063   ,297.5,300,302.6
XS GIS Cut Line= 3
     2411614.184      661926.107       2412035.6      661837.107
2412448.03388672661734.353112648
#Sta/Elev= 30
       0  2458.9    70.1  2438.8     111 2425.09   209.1 2388.22   221.3 2382.04
   233.6 2378.08   249.6 2368.35   278.6 2343.52   290.8 2334.11   310.3 2323.78
   315.4 2322.73   331.7 2322.69   352.2 2327.03   364.4 2326.38   381.2 2322.31
     389    2322   402.7 2323.63   413.5 2321.11   438.1 2319.08   442.2 2319.34
   448.3 2321.64   458.7 2328.99   483.4 2354.14   495.8  2362.5     504 2365.98
   527.5 2368.93   578.2 2372.54   682.6  2387.7     772 2407.45   855.8 2431.26
#Mann= 5 ,-1 , 0
       0      .1       0  357.09     .06       0   413.5    .045       0
   448.3     .06       0  456.58      .1       0
#XS Ineff= 2 , 0
          353.12 2330.51
Permanent Ineff=
       F       F
Bank Sta=413.5,448.3
XS Rating Curve= 0 ,0
Exp/Cntr=0.3,0.1