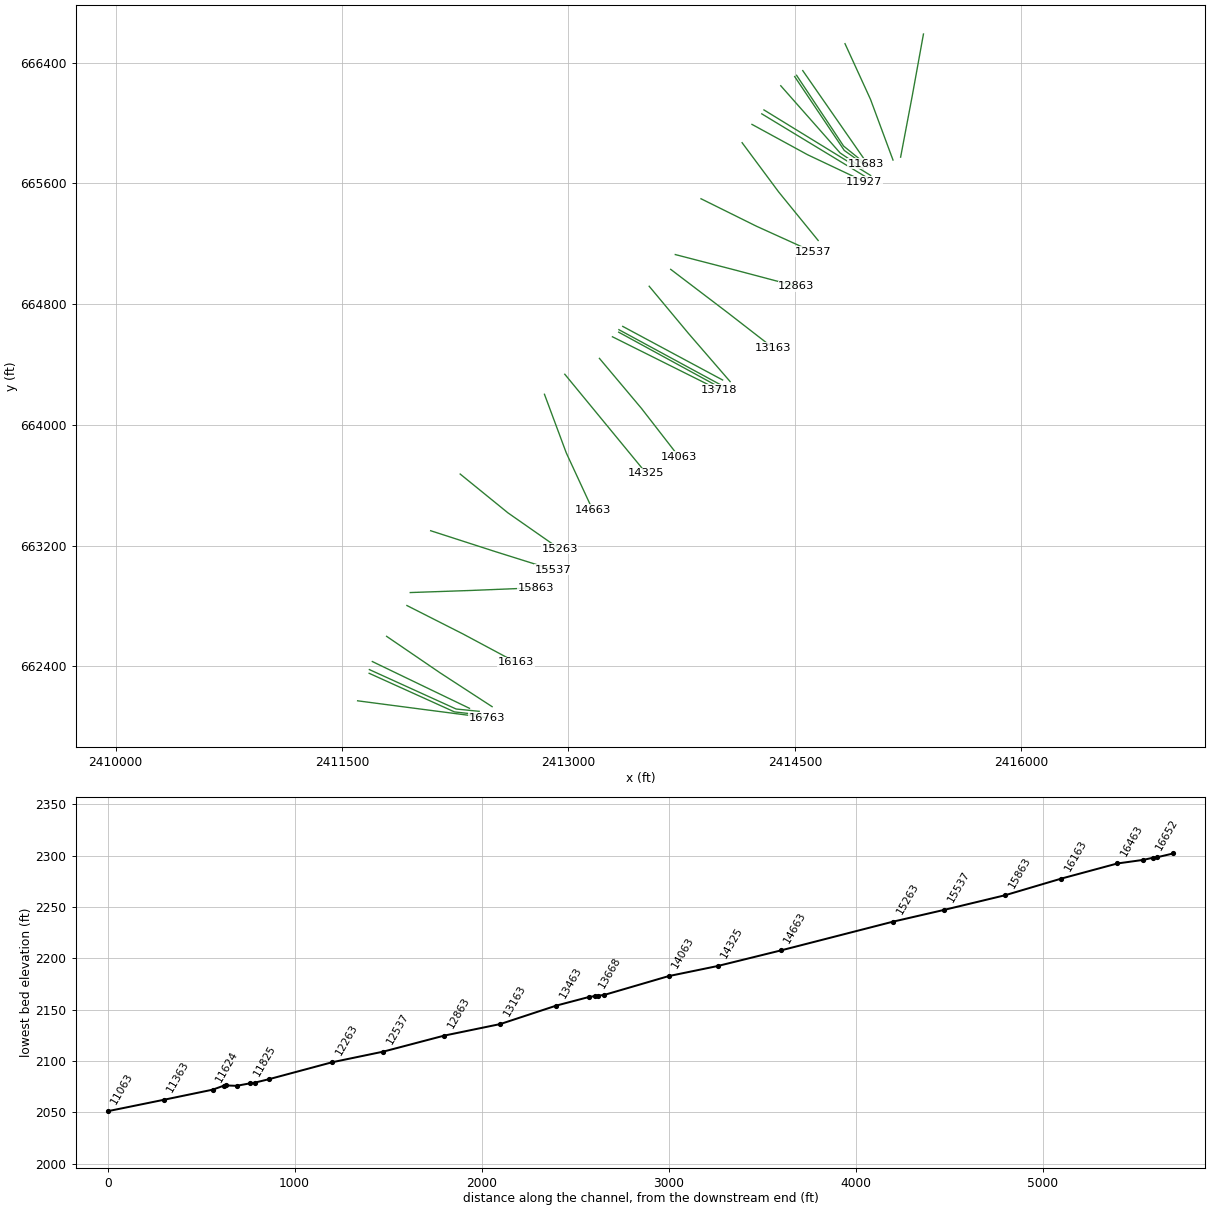
HEC-RAS study BRUSHRN.prj: BRUSHRN

--- BRUSHRN.g01 (geometry) --- (continued)

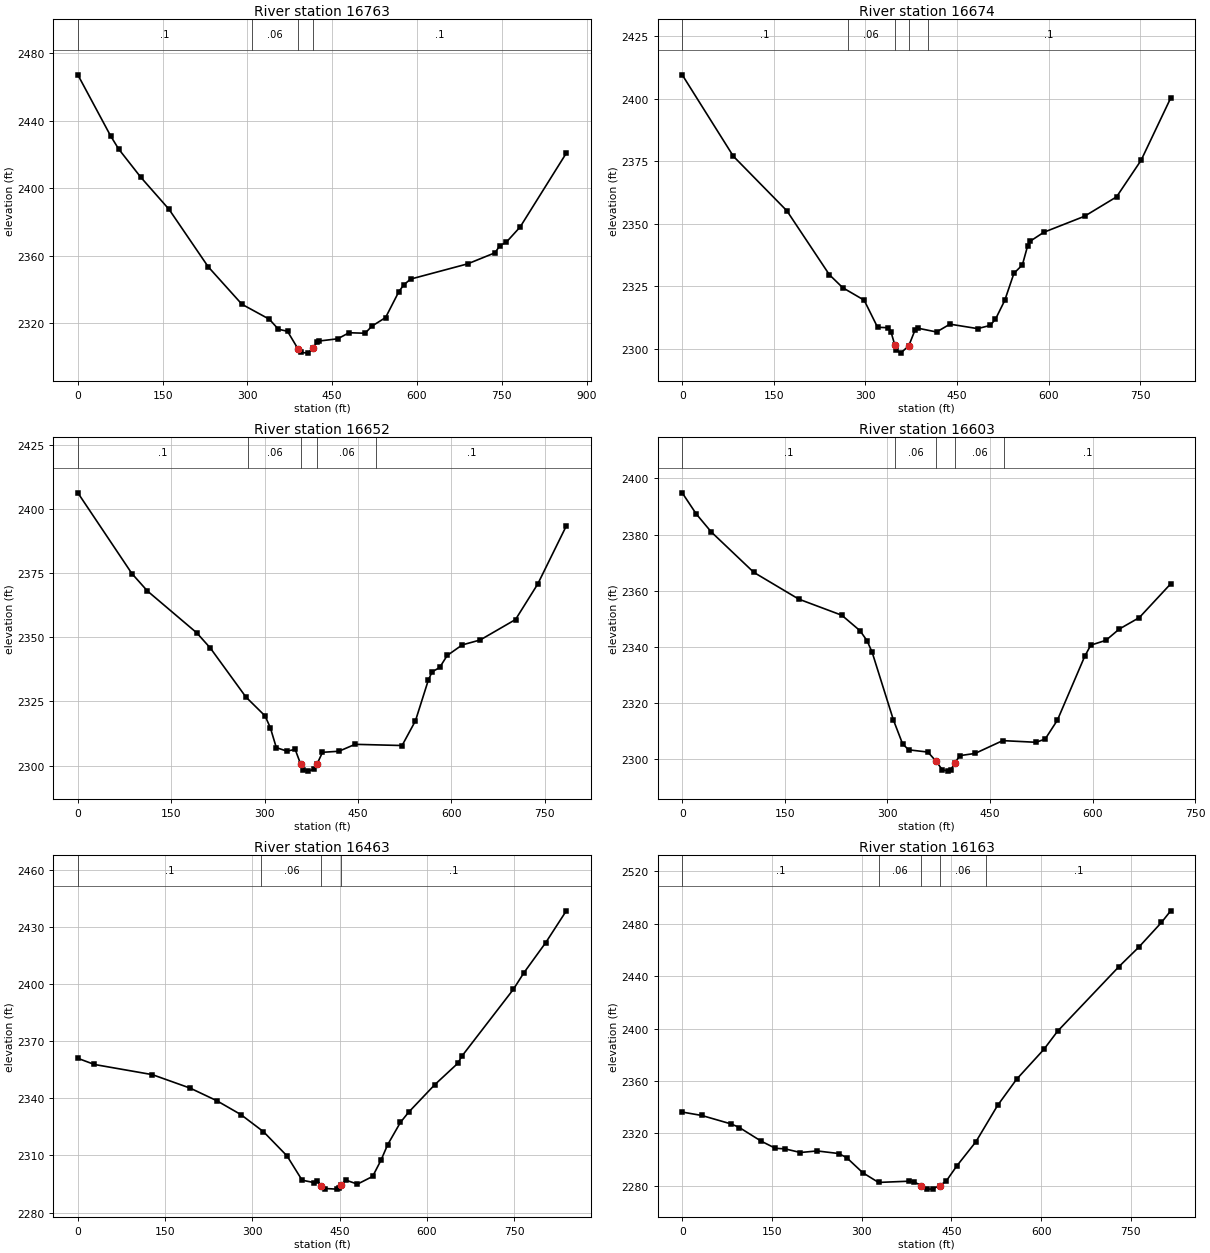
Type RM Length L Ch R = 1 ,16763   ,91,88.5,84.5
XS GIS Cut Line= 3
2411602.96547829 662171.99014726     2412003.674      662119.436
     2412459.849      662060.257
#Sta/Elev= 30
       0 2467.29    57.8 2431.16    72.1 2423.31   111.3 2406.53   161.3 2387.48
   230.6 2353.38   290.2 2331.15   338.7 2322.26   354.8 2316.32   370.9 2315.09
   389.5 2304.65   395.1 2302.57   407.1 2302.14   415.3 2304.94   423.4 2308.78
   427.4 2309.35   459.7 2310.64   479.8 2314.24   508.1 2313.94   520.2 2318.14
   544.4 2323.26     568 2338.71   576.6 2342.66   588.7 2346.08   689.6 2355.12
     738 2361.69   746.1 2365.74   758.2 2368.06   782.4 2376.98   864.1 2420.82
#Mann= 4 ,-1 , 0
       0      .1       0  307.94     .06       0   389.5    .045       0
   415.3      .1       0
Bank Sta=389.5,415.3
XS Rating Curve= 0 ,0
Exp/Cntr=0.3,0.1

Type RM Length L Ch R = 1 ,16674   ,22.4,22.6,22.8
XS GIS Cut Line= 3
2411679.31384945662354.2837836122412244.73137896662098.463080723
2412422.96081761662078.489091908
#Sta/Elev= 30
       0 2409.59    83.7 2377.06   171.4 2355.23   240.9 2329.71   262.8  2324.5
   297.9 2319.51   319.9 2308.68   337.7 2308.49   341.8 2306.91   347.9 2301.78
   350.6  2299.7   357.6 2298.34   370.9 2301.22   381.3 2307.58   385.7 2308.32
   416.5 2306.79   438.4 2309.92   483.7 2308.14   504.3 2309.41     513 2311.91
   528.1 2319.38   543.2 2330.25     557 2333.59   565.7 2341.28   570.1 2343.13
   592.1 2346.65   658.8 2353.05   711.2  2360.8   751.4 2375.41   799.9 2400.31
#Mann= 5 ,-1 , 0
       0      .1       0  271.01     .06       0   347.9    .045       0
   370.9     .06       0  402.07      .1       0
Bank Sta=347.9,370.9
XS Rating Curve= 0 ,0
Exp/Cntr(USF)=0,0
Exp/Cntr=0.5,0.3

Type RM Length L Ch R = 1 ,16652   ,49.2,49.2,48.8
XS GIS Cut Line= 3
2411680.85031013 662378.86715446 2412255.4866037662117.668839198
2412408.36444116662102.304232418
#Sta/Elev= 30
       0 2406.25    86.9 2374.79   111.9    2368     191 2351.74   212.9  2345.8
   270.1 2326.72   300.9 2319.36   309.3 2314.78   318.9 2307.03     336 2305.65
   349.2 2306.35     358 2300.61   362.4 2298.38   369.9 2297.87     379 2298.56
   384.3  2300.6   393.1  2305.2   419.5 2305.61   445.5 2308.31     521 2307.84
   542.5 2317.47   563.3 2333.41   569.3 2336.53   581.4 2338.23   593.5  2342.9
   617.6 2347.02   646.5 2348.94   703.3 2356.91     739 2370.74   784.9 2393.36
#Mann= 5 ,-1 , 0
       0      .1       0  273.65     .06       0     358    .045       0
   384.3     .06       0  479.51      .1       0
#XS Ineff= 2 , 0
           350.2    2302   393.1            2302
Permanent Ineff=
       F       F
Bank Sta=358,384.3
XS Rating Curve= 0 ,0
Exp/Cntr(USF)=0,0
Exp/Cntr=0.5,0.3

Type RM Length L Ch R = 1 ,16603   ,141.6,139.8,140.4
XS GIS Cut Line= 2
 2411700.4746669662432.1262068332412344.08097314662122.273303433
#Sta/Elev= 30
       0 2394.86    20.6 2387.32    42.5 2380.94   104.6 2366.58   170.4 2357.05
   233.4 2351.31     260 2345.81   270.3 2342.25   277.8 2338.09   308.8 2314.08
   322.2 2305.58     331 2303.44   359.2 2302.64   371.2  2299.4   380.2 2296.36
   388.7 2295.86   393.2  2296.4   398.2 2298.78   406.5 2301.39   428.2 2302.15
   468.7 2306.71   517.5 2306.12   530.8 2307.28   548.6 2313.98   588.5 2336.65
   597.4 2340.67   619.6 2342.39   639.1  2346.4   668.4 2350.47   714.3 2362.49
#Mann= 5 ,-1 , 0
       0      .1       0  310.58     .06       0   371.2    .045       0
   398.2     .06       0  471.22      .1       0
Bank Sta=371.2,398.2
XS Rating Curve= 0 ,0
Exp/Cntr(USF)=0,0
Exp/Cntr=0.5,0.3

Type RM Length L Ch R = 1 ,16463   ,298.2,300,301.7
XS GIS Cut Line= 3
2411795.11586973662599.093200126     2412151.642      662355.794
     2412493.954      662133.259
#Sta/Elev= 30
       0 2360.98    28.6 2357.74   128.1 2352.42   193.3 2345.32   238.8 2338.75
   280.4 2331.44   319.2 2322.47   359.7 2309.75   385.6 2297.02   405.7 2295.79
   411.9 2296.65   418.82294.119   425.7 2292.65   444.9 2292.33   449.6 2292.81
   452.8 2294.24   460.5 2297.08   480.8 2294.96   506.9    2299   521.4 2307.62
   532.8 2315.69   554.6 2327.32   568.9 2332.74   613.8 2347.17   653.5 2358.41
     660 2361.98   748.9  2397.2     767 2405.89   804.6 2421.74   839.9 2438.39
#Mann= 4 ,-1 , 0
       0      .1       0   315.6     .06       0   418.8    .045       0
   452.8      .1       0
Bank Sta=418.8,452.8
XS Rating Curve= 0 ,0
Exp/Cntr=0.3,0.1

Type RM Length L Ch R = 1 ,16163   ,293.4,300,308.5
XS GIS Cut Line= 3
     2411929.533      662803.292     2412298.776      662616.089
 2412653.8393304662426.152895531
#Sta/Elev= 30
       0 2336.34    32.8 2333.73    82.1 2327.24    95.5 2324.57   132.1 2314.14
   155.9 2308.69   171.8  2308.3   197.6 2305.51   225.6  2306.7   261.5 2304.74
     275 2301.58   301.8 2290.12   328.2  2282.7   379.1 2283.63   388.1 2282.99
     400 2280.21   409.5 2277.59   418.5 2277.66   430.5 2280.35   441.2 2283.59
   459.3  2295.4   491.1 2313.74   527.4 2341.49   559.1 2361.37   604.5 2384.04
   627.6 2397.98   730.3 2447.28   763.3 2462.02   801.2 2480.87   816.7 2489.76
#Mann= 5 ,-1 , 0
       0      .1       0     329     .06       0     400    .045       0
   430.5     .06       0   508.4      .1       0
Bank Sta=400,430.5
XS Rating Curve= 0 ,0
Exp/Cntr=0.3,0.1

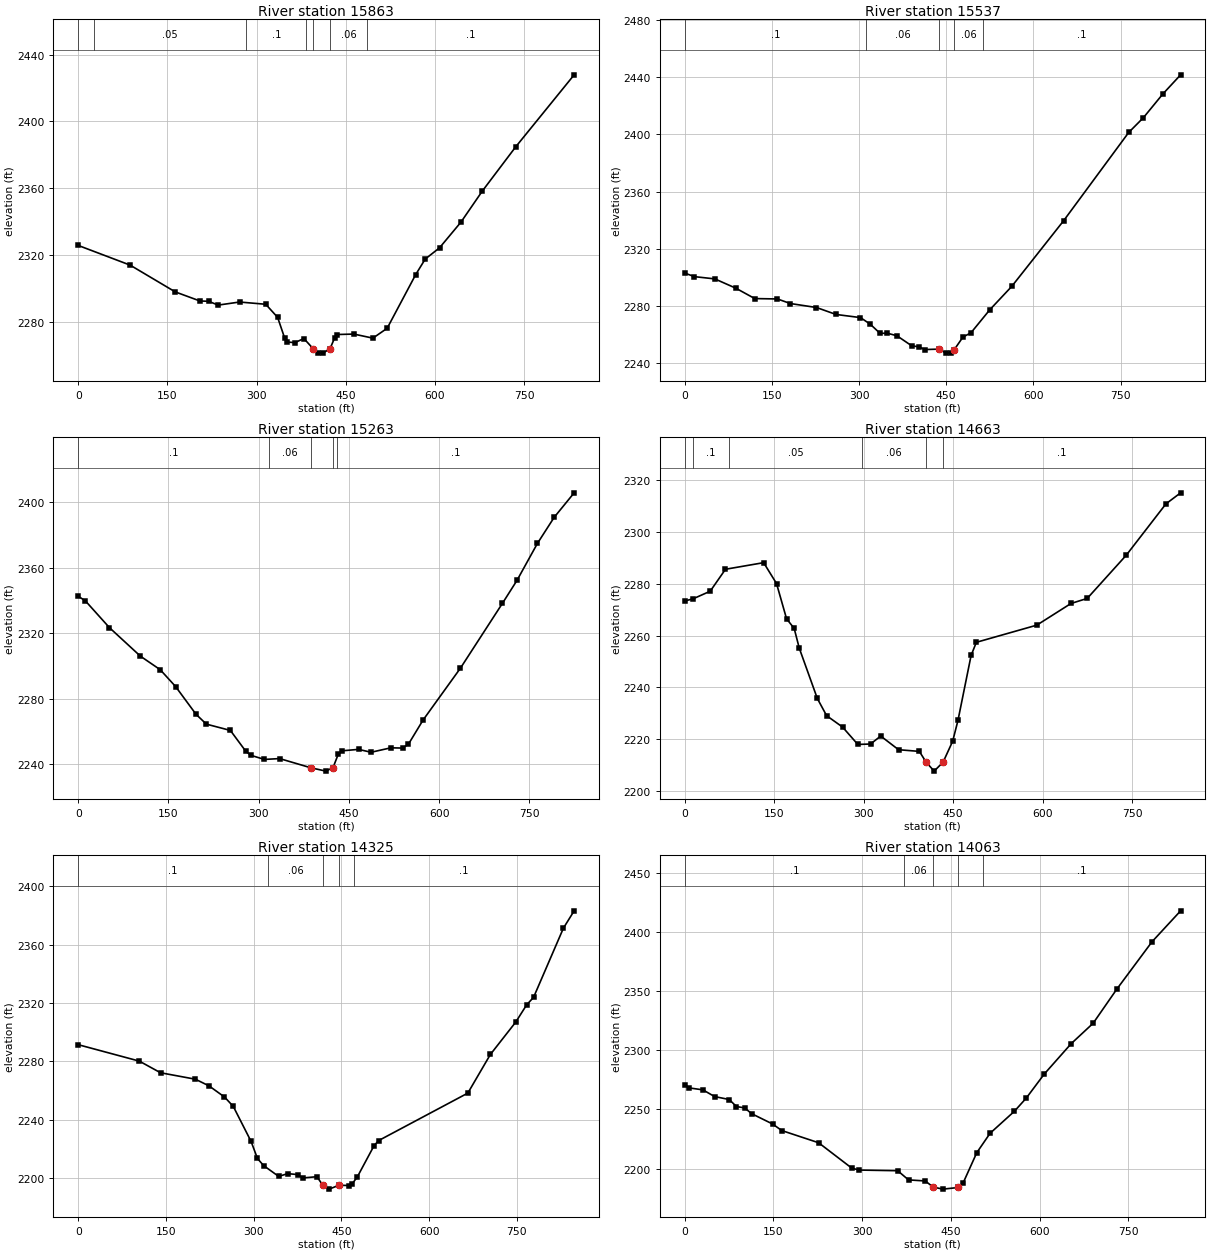
Type RM Length L Ch R = 1 ,15863   ,328.4,325.9,317.7
XS GIS Cut Line= 3
     2411951.617      662889.195     2412358.242      662903.277
2412784.93507119662920.663622037
#Sta/Elev= 30
       0 2325.82    87.2 2314.07   163.2 2298.03   204.6 2292.62   219.3 2292.41
   235.3 2290.14   271.3 2291.98   315.3 2290.64   335.3 2282.81   347.3 2270.23
   351.3 2268.06   364.4  2267.7   379.4 2270.15   395.4 2263.95   395.4 2263.94
   403.1 2261.63   411.4 2261.42   423.4 2264.04   431.4 2270.73   435.4 2272.55
   463.4 2272.82   495.5 2270.38   519.5 2276.29   567.5 2308.41   583.5 2317.69
   607.5 2324.38   643.6 2339.78   679.6  2358.4   735.6 2384.77   833.9 2427.85
#Mann= 7 ,-1 , 0
       0      .1       0   25.85     .05       0  282.44      .1       0
  383.68     .06       0   395.4    .045       0   423.4     .06       0
  485.02      .1       0
Bank Sta=395.4,423.4
XS Rating Curve= 0 ,0
Exp/Cntr=0.3,0.1

Type RM Length L Ch R = 1 ,15537   ,281.9,274.1,269
XS GIS Cut Line= 3
2412086.92153672663298.8347514112412513.96530339663160.915088701
2412899.91430339663039.738088701
#Sta/Elev= 30
       0 2303.14    16.6 2300.63    51.9 2299.04    88.1 2292.53   120.6 2285.29
   159.5 2285.02     182 2281.81   226.8 2279.04   260.4 2274.19   302.5 2271.99
   319.3 2267.38   336.1    2261   348.7 2261.08   365.2 2259.29   390.7 2252.26
   403.3 2251.57   412.9 2249.65     437 2249.96   449.6 2247.16     458  2247.5
   463.8 2249.61   478.9 2258.44   492.5 2261.32     525 2277.48   562.7 2293.78
     652  2339.7     764 2401.41   789.4 2411.78   822.7 2428.28   853.3 2441.67
#Mann= 5 ,-1 , 0
       0      .1       0  311.96     .06       0     437    .045       0
   463.8     .06       0  512.82      .1       0
Bank Sta=437,463.8
XS Rating Curve= 0 ,0
Exp/Cntr=0.3,0.1

Type RM Length L Ch R = 1 ,15263   ,603.3,600,588.6
XS GIS Cut Line= 3
     2412282.453       663674.43     2412599.562      663416.806
2412940.70876526663178.725147892
#Sta/Elev= 30
       0 2342.51      12 2339.63    51.9 2323.31   103.4 2305.89   136.4  2297.6
     162 2287.29   195.9 2270.37   213.1 2264.36     253 2260.52   278.5 2247.86
   287.1 2245.31   309.6 2242.81   334.9 2243.32   386.6 2237.72   411.9 2235.66
   423.7 2237.83   432.3  2245.9   438.1 2248.05   466.1 2248.95   486.9 2247.18
   519.8  2249.9   539.3 2249.75     549 2252.08   573.4 2266.87   635.6  2298.6
   705.3 2338.13   729.5 2352.14   763.6 2374.81   791.4  2390.7   824.6 2405.66
#Mann= 5 ,-1 , 0
       0      .1       0  316.93     .06       0   386.6    .045       0
   423.7     .06       0  430.61      .1       0
Bank Sta=386.6,423.7
XS Rating Curve= 0 ,0
Exp/Cntr=0.3,0.1

Type RM Length L Ch R = 1 ,14663   ,334,337.8,341.4
XS GIS Cut Line= 3
     2412840.752      664202.959     2412985.309      663814.641
     2413160.564      663436.043
#Sta/Elev= 30
       0 2273.34      14 2274.18    42.8 2277.12    68.4  2285.6   132.4 2288.15
     154 2280.09   170.8 2266.48   183.6 2262.75   192.1 2255.15   222.4 2235.69
     238 2229.05   264.7 2224.66   290.3 2217.95   311.6 2218.11   328.7 2221.19
   358.6 2215.91   393.5 2215.26   404.7 2211.13   418.3 2207.64   433.3 2211.13
   449.3 2219.18   458.2 2227.22   480.2  2252.3     489 2257.39   590.4 2264.02
   647.7 2272.39   674.9 2274.34   740.3 2291.01   806.9 2310.86   831.5 2315.12
#Mann= 6 ,-1 , 0
       0     .05       0      14      .1       0   73.76     .05       0
  297.34     .06       0   404.7    .045       0   433.3      .1       0
Bank Sta=404.7,433.3
XS Rating Curve= 0 ,0
Exp/Cntr=0.3,0.1

Type RM Length L Ch R = 1 ,14325   ,261.4,262.2,265.2
XS GIS Cut Line= 2
2412975.45113373664335.6161193092413514.21921345663680.677251135
#Sta/Elev= 30
       0 2291.41   104.5 2280.15   140.8 2272.18   200.4 2267.76   223.7 2263.19
   250.1 2255.59   265.1 2249.19   295.6 2225.15   306.5 2213.49   316.9 2208.64
   342.8 2201.19   358.3 2203.07   375.1 2202.46   384.2 2200.13   408.2 2200.98
   417.8 2195.45   429.1 2192.47   445.9 2195.14   463.2 2194.93   468.9 2196.28
   477.5 2200.98   505.9 2222.22   513.7 2225.72   666.3 2258.26   704.8  2284.7
   748.2 2306.89     767 2318.77   778.7 2323.84   829.8 2371.29   848.1  2383.1
#Mann= 5 ,-1 , 0
       0      .1       0  324.72     .06       0   417.8    .045       0
   445.9     .06       0  471.27      .1       0
Bank Sta=417.8,445.9
XS Rating Curve= 0 ,0
Exp/Cntr=0.3,0.1

Type RM Length L Ch R = 1 ,14063   ,339.8,345.2,357
XS GIS Cut Line= 3
     2413205.088      664440.566     2413483.713      664109.046
     2413732.129      663788.745
#Sta/Elev= 30
       0 2270.75       8 2268.12    30.8 2266.51    50.6 2260.83    75.3 2258.35
    87.5 2252.41   101.5 2251.24   113.1  2246.4   148.5 2237.69   164.2 2232.12
   226.4 2221.83   282.3 2200.45   294.8 2198.75   360.1 2198.19   378.4 2190.44
   406.7 2189.54   420.2 2184.33   436.8 2182.64   462.4 2184.02     471 2188.16
   493.8 2213.42   516.3 2229.83   557.3 2248.37   577.5 2259.57   607.8 2279.81
   653.4 2305.53   690.5 2322.76   730.4  2351.5   790.1 2391.65   838.4 2417.75
#Mann= 5 ,-1 , 0
       0      .1       0  371.17     .06       0   420.2    .045       0
   462.4     .06       0  504.74      .1       0
Bank Sta=420.2,462.4
XS Rating Curve= 0 ,0
Exp/Cntr=0.3,0.1

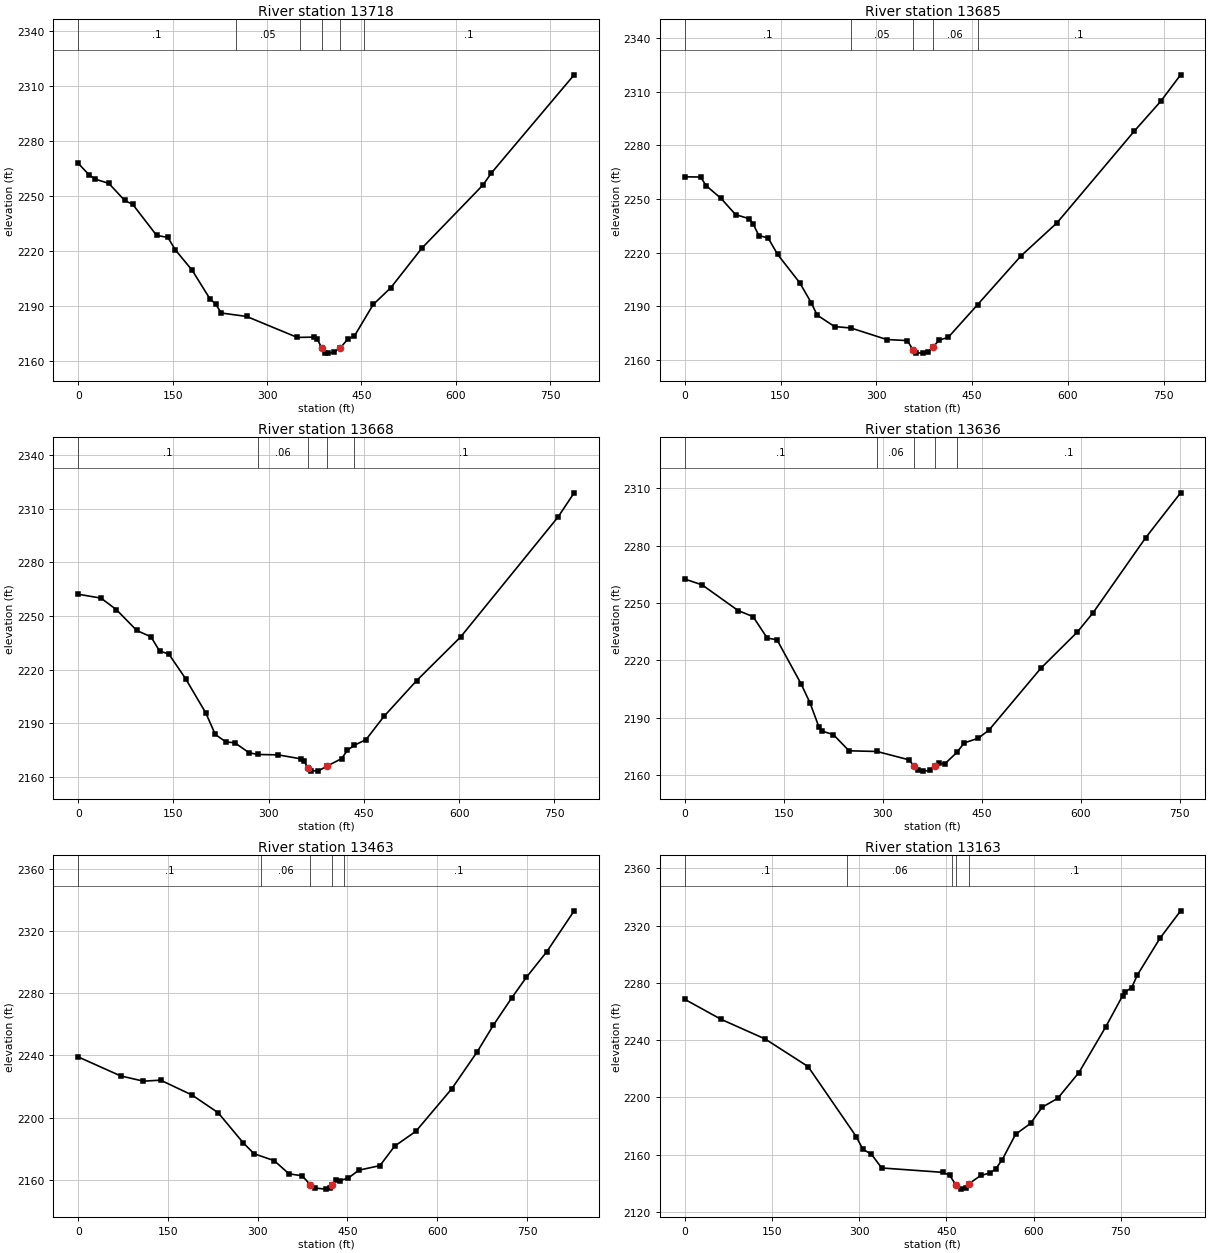
Type RM Length L Ch R = 1 ,13718   ,33.1,32.6,31.8
XS GIS Cut Line= 2
2413291.24272928664583.7786080482413996.40185961664231.925402012
#Sta/Elev= 30
       0 2267.69    17.3  2261.4    27.1 2259.05    48.6 2256.78    73.7 2247.51
    86.8 2245.26   124.6 2228.43   142.5 2227.31   154.3 2220.54   181.2 2209.37
     209 2194.03   218.5 2190.88   227.4 2186.13   267.7 2184.25   348.1 2172.83
   374.9    2173   379.4  2172.1   386.92167.271   392.8  2164.5   396.9 2164.27
   406.2 2164.74   416.6 2167.16   428.6 2171.99   438.7 2173.48   468.8 2190.77
   496.6 2199.85     546 2221.43   643.2 2255.87   656.4 2262.34   788.1 2315.91
#Mann= 6 ,-1 , 0
       0      .1       0  250.61     .05       0  352.28     .06       0
   386.9    .045       0   416.6     .06       0  453.86      .1       0
Bank Sta=386.9,416.6
XS Rating Curve= 0 ,0
Exp/Cntr=0.5,0.3

Type RM Length L Ch R = 1 ,13685   ,16.6,16.7,16.7
XS GIS Cut Line= 2
2413332.79984647664614.1479473272414014.19452863664242.132324786
#Sta/Elev= 30
       0 2262.43      25 2262.31    33.3 2257.56    56.9 2250.35    79.7 2241.25
   101.1 2238.95     107 2236.15   116.1 2229.52   130.6  2228.2   145.3 2219.04
     180 2203.14   198.2 2191.83   207.3 2184.99   234.6 2178.55   260.3 2177.74
   316.3 2171.29   348.6 2170.69   357.32165.569   362.2 2163.85   372.3 2163.67
   380.5 2164.22     3882166.874   398.7 2171.04   412.4 2172.46   458.4 2190.78
   526.3 2218.09   582.8 2236.66     704 2288.12   745.1  2304.7   776.3 2319.56
#Mann= 5 ,-1 , 0
       0      .1       0   260.3     .05       0   357.3    .045       0
     388     .06       0   458.4      .1       0
Bank Sta=357.3,388
XS Rating Curve= 0 ,0
Exp/Cntr(USF)=0,0
Exp/Cntr=0.5,0.3

Type RM Length L Ch R = 1 ,13668   ,32.8,32.7,32.8
XS GIS Cut Line= 2
2413334.01114323664630.8173681082414020.78299409664258.729448012
#Sta/Elev= 30
       0 2262.18    35.9    2260      60  2253.6    92.2 2241.91   114.6 2238.36
   128.2 2230.38   142.6 2228.78   169.2  2214.9     201 2195.72   215.9 2183.72
   232.9 2179.52   246.5 2179.13   269.2  2173.5   282.9 2172.54   314.7 2172.33
   351.1 2170.08   355.7 2168.86   361.52165.144   366.4 2163.55   377.7 2163.23
   392.22166.125   414.8  2170.2   423.9 2174.85   434.2 2177.57   453.3 2180.85
   481.4 2193.79   533.1 2213.89   602.4 2238.32   755.9 2305.45   781.1  2318.9
#Mann= 5 ,-1 , 0
       0      .1       0   282.9     .06       0   361.5    .045       0
   392.2     .06       0   434.2      .1       0
Bank Sta=361.5,392.2
XS Rating Curve= 0 ,0
Exp/Cntr(USF)=0,0
Exp/Cntr=0.5,0.3

Type RM Length L Ch R = 1 ,13636   ,179,172.8,166.2
XS GIS Cut Line= 2
2413359.43385487 664652.629608372414021.21143032664297.475642878
#Sta/Elev= 30
       0 2262.51    26.5 2259.45    80.9 2246.06   103.6 2242.89   124.9 2231.74
   139.9 2230.77   176.3 2207.79   189.9 2197.81   203.5 2185.12     208 2183.18
   225.3 2181.28   248.9 2172.87   291.3 2172.51   339.7 2168.16   346.8 2165.19
   353.3 2162.62   361.2 2162.26   371.5 2162.62   378.62164.697   384.8 2166.38
   393.7 2165.98   412.3 2172.04   423.2 2176.97   444.1 2179.35   460.5 2183.55
   539.4 2215.94   594.6 2234.82   618.2 2244.76   698.3 2284.14   751.1  2307.5
#Mann= 5 ,-1 , 0
       0      .1       0   291.3     .06       0   346.8    .045       0
   378.6     .06       0   412.3      .1       0
Bank Sta=346.8,378.6
XS Rating Curve= 0 ,0
Exp/Cntr(USF)=0,0
Exp/Cntr=0.3,0.1

Type RM Length L Ch R = 1 ,13463   ,300.5,300,300.6
XS GIS Cut Line= 3
     2413534.667      664918.644     2413795.343      664605.545
     2414071.072       664286.95
#Sta/Elev= 30
       0 2239.06    70.9 2226.84     109 2223.45   137.7  2224.1   190.2 2214.53
   233.9 2203.11   275.5 2183.87   293.9 2176.73   327.6 2172.28   352.1 2163.83
   374.4 2162.52   387.7 2156.83   395.2 2154.65   414.5 2153.96   420.2 2154.41
   424.8 2156.74   430.9 2159.92   437.1 2159.47   451.4  2161.1   469.1 2166.16
   504.3  2169.1   528.7 2181.59   564.3 2191.19   624.4 2218.62   666.9 2242.41
   693.8 2259.49   724.3 2276.96   748.8 2290.21   783.2 2306.86   828.8  2333.1
#Mann= 5 ,-1 , 0
       0      .1       0  306.16     .06       0   387.7    .045       0
   424.8     .06       0  443.79      .1       0
Bank Sta=387.7,424.8
XS Rating Curve= 0 ,0
Exp/Cntr=0.3,0.1

Type RM Length L Ch R = 1 ,13163   ,297.6,300,302.5
XS GIS Cut Line= 3
     2413677.121      665030.631     2414055.687      664742.833
2414353.65474242664511.738159659
#Sta/Elev= 30
       0 2268.62    62.3 2254.66   138.4 2240.86   212.2 2221.57     295 2172.65
   306.4 2163.72   320.7 2160.51   338.7 2150.75   444.2 2147.68   455.6  2145.6
   466.3 2138.88   474.8 2135.97   483.4 2136.88   488.5 2139.68     509  2145.5
     525 2147.25   534.7 2150.07   546.1 2156.65   568.9  2174.3   594.6 2181.86
   614.5 2193.17   641.4 2199.44   677.8 2217.44   723.5 2249.07   752.8 2271.03
   757.8 2273.86   768.5 2276.75   778.1 2285.45   816.9 2311.12   852.6  2330.4
#Mann= 5 ,-1 , 0
       0      .1       0  279.14     .06       0  460.28      .1       0
   466.3    .045       0   488.5      .1       0
Bank Sta=466.3,488.5
XS Rating Curve= 0 ,0
Exp/Cntr=0.3,0.1

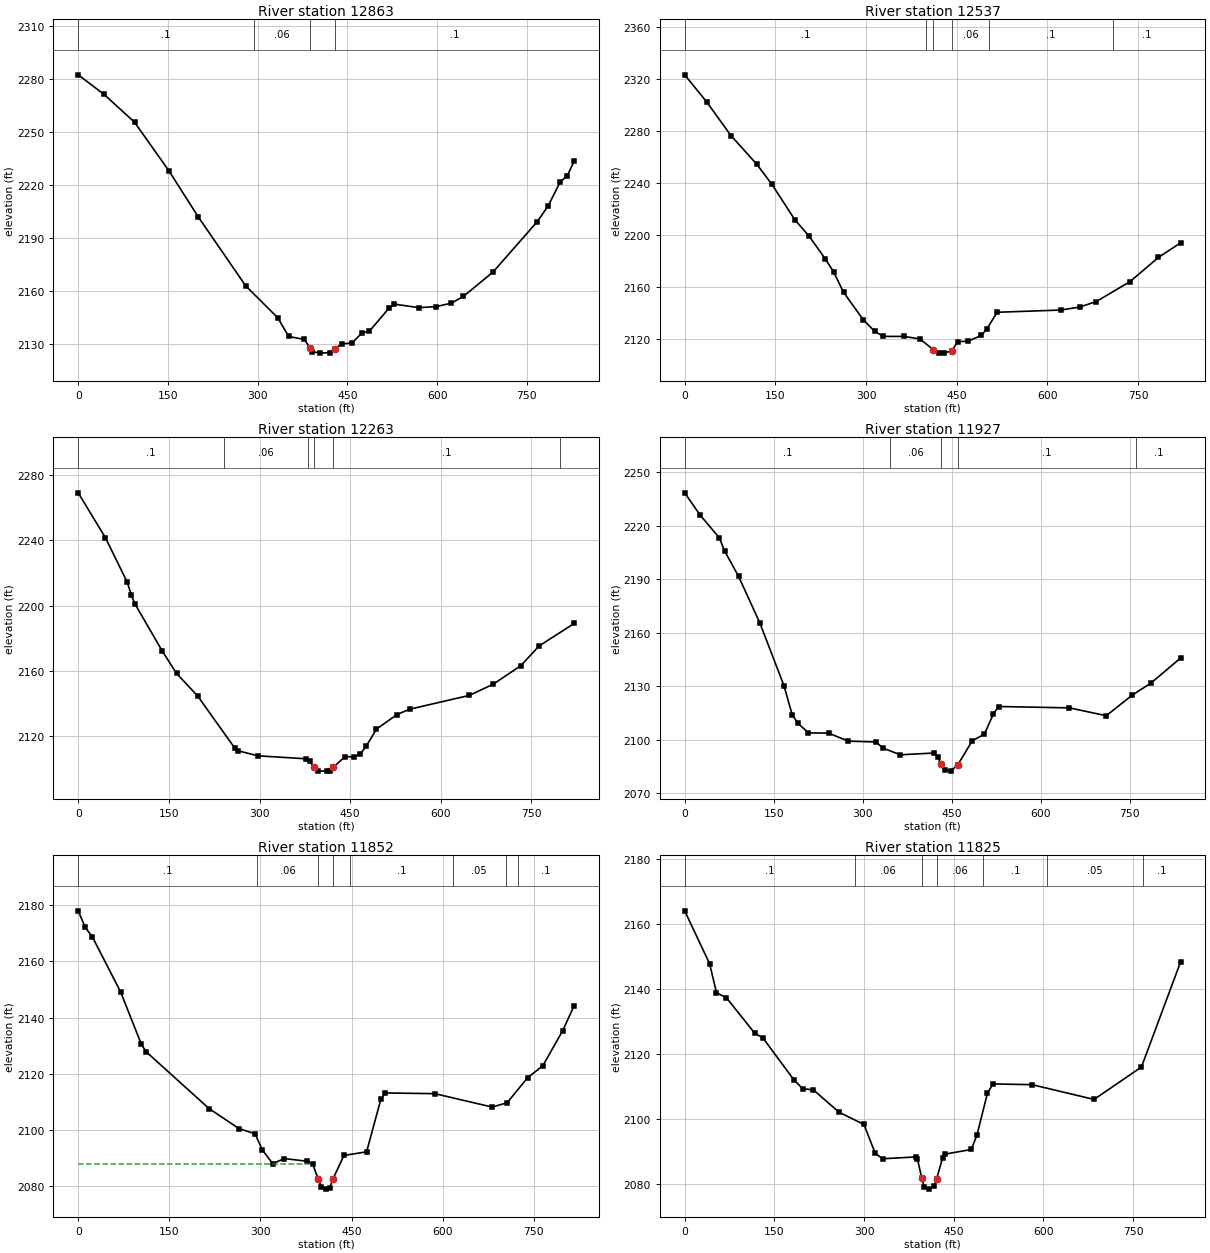
Type RM Length L Ch R = 1 ,12863   ,329.7,325.7,321.5
XS GIS Cut Line= 3
     2413707.667      665128.517      2414102.03      665026.557
     2414509.794      664918.675
#Sta/Elev= 30
       0 2282.44    43.3 2271.32    94.1  2255.6   151.9  2227.9   200.8 2201.85
     280 2162.85   333.7  2144.7   351.8 2134.17   378.1 2132.45   387.9 2127.47
   391.5 2125.61   403.9 2124.71   420.5 2124.99   428.8 2127.33   441.2 2129.94
   457.7 2130.48   474.3  2136.1   486.7  2137.1   519.8 2150.27   528.1 2152.51
   569.4 2150.48   598.4 2151.09   623.6 2153.01   643.9 2156.82   693.6 2170.72
   767.6 2199.29   785.8 2208.23   805.3 2221.49   817.7 2225.32   829.1 2233.53
#Mann= 4 ,-1 , 0
       0      .1       0  293.73     .06       0   387.9    .045       0
   428.8      .1       0
Bank Sta=387.9,428.8
XS Rating Curve= 0 ,0
Exp/Cntr=0.3,0.1

Type RM Length L Ch R = 1 ,12537   ,282.5,274.3,266.7
XS GIS Cut Line= 3
2413878.06119131665498.2756085582414246.53019131665315.764608558
2414619.17119131665146.922608558
#Sta/Elev= 30
       0 2322.91    36.5 2302.06    76.6  2276.2   119.5 2254.09   144.4 2238.72
   182.1 2211.63   205.9 2198.91   232.9 2181.29   246.3 2171.57   262.7 2155.89
   295.6 2134.64     314 2126.02   328.4 2121.97   362.3 2121.96   389.1 2120.07
   411.4  2111.7   420.2 2109.32     429 2109.12   442.4 2111.05   451.3 2117.94
   468.5 2118.22   490.5 2122.71   499.3  2127.3   516.8 2140.51   622.2 2142.22
   653.8 2144.56     681 2148.78   736.4    2164   783.7 2182.69   820.3 2193.85
#Mann= 6 ,-1 , 0
       0      .1       0  399.85     .06       0   411.4    .045       0
   442.4     .06       0  502.86      .1       0  708.66      .1       0
Bank Sta=411.4,442.4
XS Rating Curve= 0 ,0
Exp/Cntr=0.3,0.1

Type RM Length L Ch R = 1 ,12263   ,328.6,336.3,342.4
XS GIS Cut Line= 3
     2414150.331      665869.548     2414393.187      665542.434
 2414654.2088842665221.999937277
#Sta/Elev= 30
       0 2268.92    45.1 2241.42    81.2 2214.21      88 2206.36    93.7 2201.11
   139.4 2171.97   162.7 2158.49   197.6 2144.71   259.5  2112.6   265.2 2111.14
   297.2  2108.1   376.5  2106.3   383.2 2104.64   389.9 2101.15   396.8 2098.93
     412 2098.74   417.1 2098.97   422.4 2101.17   441.5 2107.63   456.5 2107.45
   466.9 2109.27   476.9 2114.17   493.5 2124.39   527.6 2133.36   549.2 2136.67
     647 2145.02   686.8 2151.89   732.3 2163.21   762.8 2175.31   820.7 2189.02
#Mann= 6 ,-1 , 0
       0      .1       0  240.96     .06       0   379.5      .1       0
   389.9    .045       0   422.4      .1       0  797.18      .1       0
Bank Sta=389.9,422.4
XS Rating Curve= 0 ,0
Exp/Cntr=0.3,0.1

Type RM Length L Ch R = 1 ,11927   ,75.1,74.2,73.3
XS GIS Cut Line= 3
2414215.71624231665990.9233283132414585.13424231665789.416328313
2414960.04021819665612.189202868
#Sta/Elev= 30
       0 2238.47    26.2 2225.91    58.3 2213.25    67.2  2205.9    90.7 2191.64
   126.5 2165.57   167.4 2130.15   181.1 2113.97   190.3 2109.33   208.5 2103.79
   242.3 2103.65   275.7 2099.14   322.4 2098.66   334.2 2095.22   363.4  2091.5
   420.8 2092.48   426.9 2090.18   431.4 2086.28   438.9 2082.92   447.9 2082.32
     460 2085.78   484.5 2099.37     505 2103.06     520 2114.35   528.8 2118.58
   648.2 2117.81   710.2 2113.41   754.4 2125.05   785.4 2131.68   835.5 2145.79
#Mann= 5 ,-1 , 0
       0      .1       0  345.91     .06       0   431.4    .045       0
     460      .1       0  760.75      .1       0
Bank Sta=431.4,460
XS Rating Curve= 0 ,0
Exp/Cntr=0.5,0.3

Type RM Length L Ch R = 1 ,11852   ,27.4,27.3,27.2
XS GIS Cut Line= 2
2414280.66403734 666060.789266972414978.84713403665637.647996245
#Sta/Elev= 30
       0 2177.99    11.6 2172.11    23.3 2168.72    69.9 2149.11     104 2130.49
   111.7  2127.9   215.5 2107.65   264.4 2100.58   291.2  2098.7   302.9 2093.04
   320.1 2088.08   339.2 2089.88   376.6 2088.95     386 2087.92   395.3 2082.48
     400 2079.89   407.7 2079.02     414 2079.51   419.4 2082.64   437.4 2090.99
   474.7 2092.29   498.2 2110.95   505.3 2113.22   587.1 2112.97   681.5  2108.2
     706 2109.73   739.7 2118.62   764.8 2122.88   797.6  2135.4   816.4 2144.25
#Mann= 8 ,-1 , 0
       0      .1       0  294.82     .06       0   395.3    .045       0
   419.4     .06       0  447.76      .1       0  616.19     .05       0
  703.87      .1       0  723.32      .1       0
#XS Ineff= 2 , 0
             386    2088     431            2088
Permanent Ineff=
       F       F
Bank Sta=395.3,419.4
XS Rating Curve= 0 ,0
Exp/Cntr(USF)=0,0
Exp/Cntr=0.5,0.3

Type RM Length L Ch R = 1 ,11825   ,76.7,72.5,68.1
XS GIS Cut Line= 2
 2414295.1580663666086.733332873 2415002.0760663665652.620332873
#Sta/Elev= 30
       0 2164.13    41.8 2147.77    53.2  2138.9    69.9  2137.3   116.9 2126.43
   130.9 2124.91   182.8 2111.96   197.3 2109.27   215.4 2108.88   258.4 2101.97
   299.9 2098.23   318.7 2089.32   331.1 2087.64   386.4  2088.2   389.3 2087.62
   396.52081.741   400.6 2079.08   407.9 2078.27   417.3 2079.16   421.3 2081.37
   431.4 2087.87   435.8 2089.08   479.4  2090.5   488.9 2094.92   506.5 2107.91
   515.9 2110.73   581.2 2110.49   684.8 2105.94   764.1 2115.95   829.6 2148.39
#Mann= 7 ,-1 , 0
       0      .1       0  284.55     .06       0   396.5    .045       0
   421.3     .06       0  499.31      .1       0  606.69     .05       0
  766.16      .1       0
Bank Sta=396.5,421.3
XS Rating Curve= 0 ,0
Exp/Cntr=0.5,0.3

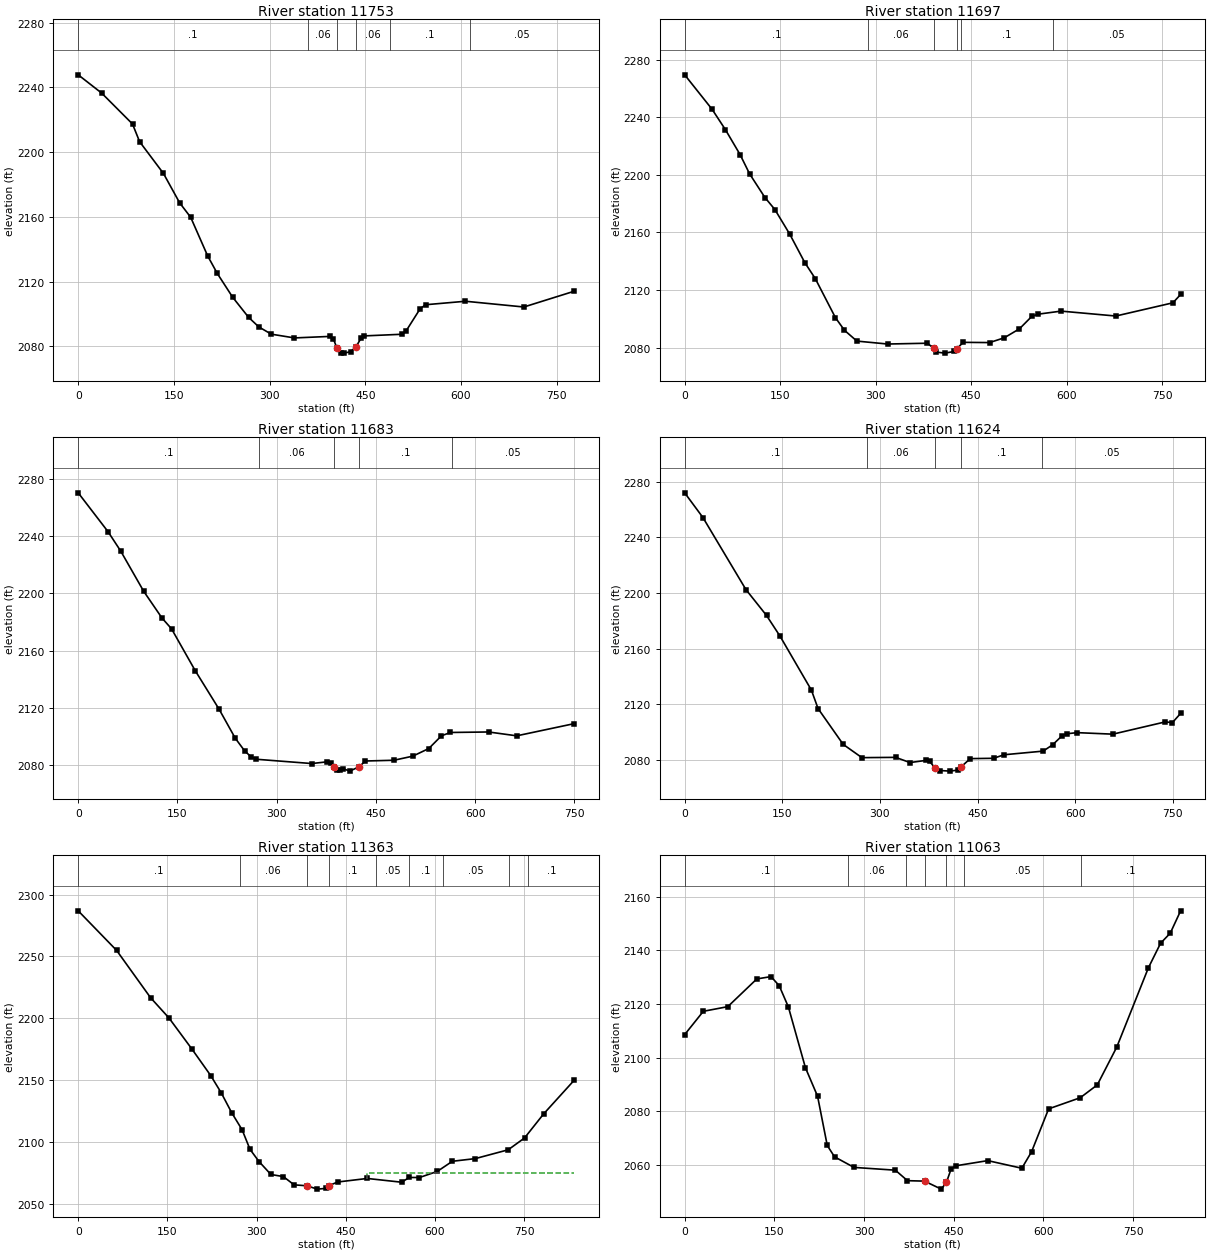
Type RM Length L Ch R = 1 ,11753   ,58,55.8,53.4
XS GIS Cut Line= 3
2414406.41910533666247.0175819512414799.32256243665802.073931862
2414951.54012693665699.294550702
#Sta/Elev= 30
       0 2247.76    36.8 2236.46    85.1 2217.38    96.2 2206.47   133.6 2186.82
     159 2168.66   176.3 2159.72   202.9 2135.87     218 2125.02   242.2 2110.28
     267 2097.94     283 2092.03   302.6 2087.53   338.9  2085.2   395.1 2086.15
   399.9 2084.59   405.4 2079.08   411.2 2075.99   416.9 2075.81   427.1 2076.73
   435.6 2079.86   443.1 2084.92   447.7 2086.44   507.6 2087.47   514.2  2089.7
   535.9 2103.22   544.4 2105.71     607 2107.86   698.5 2104.31   777.3 2114.04
#Mann= 6 ,-1 , 0
       0      .1       0   359.9     .06       0   405.4    .045       0
   435.6     .06       0  488.32      .1       0  613.32     .05       0
Bank Sta=405.4,435.6
XS Rating Curve= 0 ,0
Exp/Cntr(USF)=0,0
Exp/Cntr=0.5,0.3

Type RM Length L Ch R = 1 ,11697   ,14.2,13.5,13.7
XS GIS Cut Line= 3
2414498.70904024666307.5604390462414827.36936046665818.264103375
2414981.73623698665707.838105387
#Sta/Elev= 30
       0 2269.42    43.1 2245.47    63.9 2231.42      87 2214.08     102 2200.67
   126.1 2184.23   141.7 2175.91   165.1 2158.77   188.7 2139.07   205.2 2127.94
   236.9 2100.78   251.1 2092.02   270.6 2084.54   318.8 2082.51   381.5 2083.07
   391.1 2079.54   395.4 2076.89     409 2076.19   423.3 2077.35   427.1 2079.09
   437.7 2083.68     479 2083.51   502.1 2086.83     526 2093.08   545.3 2101.66
   554.9 2103.21   591.4 2105.36   677.4 2101.95   767.1 2111.13   779.2  2116.9
#Mann= 6 ,-1 , 0
       0      .1       0   288.2     .06       0   391.1    .045       0
   427.1     .06       0  433.56      .1       0  578.91     .05       0
#XS Ineff= 2 , 0
          380.54 2082.14   435.8          2081.5
Permanent Ineff=
       F       F
Bank Sta=391.1,427.1
XS Rating Curve= 0 ,0
Exp/Cntr(USF)=0,0
Exp/Cntr=0.5,0.3

Type RM Length L Ch R = 1 ,11683   ,59.1,59.3,59.8
XS GIS Cut Line= 4
2414511.04116681666316.3457269542414738.28040912665975.021834298
2414822.39508554665847.6191785282414967.70121577665729.819947922
#Sta/Elev= 30
       0 2270.09      45 2243.03    64.2  2229.5    98.9 2201.47   126.7 2182.72
   141.1  2175.2   176.8 2146.09   213.2 2118.94   237.4  2098.9   251.6 2090.04
   261.2 2085.96   269.1  2084.2   353.1  2081.2   376.6 2082.42     382 2081.63
   387.4 2078.57     391 2076.88   395.8 2076.48   400.6 2077.61   410.5 2075.91
   424.6 2078.94   434.2 2082.97   477.3  2083.5   505.8 2086.35     530 2091.67
   549.2 2100.57   562.7 2102.88   620.4 2103.23     663 2100.54   749.8 2109.04
#Mann= 5 ,-1 , 0
       0      .1       0  273.65     .06       0   387.4    .045       0
   424.6      .1       0  565.51     .05       0
Bank Sta=387.4,424.6
XS Rating Curve= 0 ,0
Exp/Cntr=0.5,0.3

Type RM Length L Ch R = 1 ,11624   ,264.9,261.1,256.9
XS GIS Cut Line= 2
2414552.13164571666347.194953462 2414986.6672572665721.411632724
#Sta/Elev= 30
       0 2271.91      28 2254.19    94.1 2202.43   125.7 2183.85   146.5 2168.96
   194.7 2130.19   204.9 2116.97   243.5 2091.25   272.3 2081.72     324 2081.93
   346.1  2078.2   370.5 2079.73   376.3 2079.08   384.3 2074.44     393 2072.47
   407.3 2072.04   419.2 2072.75     424 2074.83   438.7 2081.02   474.5 2081.26
   490.7  2083.8   550.7 2086.41   565.3 2090.96   579.9 2097.48   586.7 2098.85
   602.8 2099.68   657.8 2098.59   737.9 2107.35   749.4 2106.96   761.9 2113.49
#Mann= 5 ,-1 , 0
       0      .1       0  279.82     .06       0   384.3    .045       0
     424      .1       0  549.23     .05       0
Bank Sta=384.3,424
XS Rating Curve= 0 ,0
Exp/Cntr(USF)=0,0
Exp/Cntr=0.3,0.1

Type RM Length L Ch R = 1 ,11363   ,310.9,300,289.8
XS GIS Cut Line= 3
2414832.02499805666525.622719886     2415001.071      666156.666
     2415150.029      665754.836
#Sta/Elev= 30
       0 2286.84    64.6 2254.89   121.8 2216.68   152.6 2200.42   191.2 2175.34
     223 2153.83   240.6 2139.95   258.2  2123.9   275.8 2110.05     289 2094.33
   304.2 2084.47   324.2 2074.01   345.1 2072.33   363.2 2065.66   384.3 2064.92
   402.4  2062.2   416.3 2062.77   422.2  2065.1   436.5 2067.95   486.3 2070.81
   544.2 2067.77     557 2071.61   574.1 2071.57     604 2076.46   629.5 2084.68
     668 2086.83   723.4 2093.95   750.9 2103.48   783.1 2122.94   834.4 2150.07
#Mann= 9 ,-1 , 0
       0      .1       0  271.85     .06       0   384.3    .045       0
   422.2      .1       0  501.21     .05       0  556.18      .1       0
  612.92     .05       0  724.62      .1       0  757.57      .1       0
#XS Ineff= 2 , 0
                          485.64          2075.3
Permanent Ineff=
       F       F
Bank Sta=384.3,422.2
XS Rating Curve= 0 ,0
Exp/Cntr=0.3,0.1

Type RM Length L Ch R = 1 ,11063   ,431.5,450,468
XS GIS Cut Line= 3
     2415351.834      666589.604     2415276.805       666176.02
 2415200.4548842665773.924033774
#Sta/Elev= 30
       0 2108.64    31.2 2117.32    72.1 2119.05   120.7 2129.38   144.4 2130.24
   158.1 2126.87   173.5 2118.92     202 2096.29   222.3 2085.68   238.5 2067.33
   250.7  2063.1   283.3 2059.16   352.4 2058.13   372.7 2054.22   401.2 2054.05
   429.2 2051.07   437.8 2053.58   445.9 2058.69   454.3 2059.79     507 2061.69
     564 2058.85   580.3    2065   608.8 2080.97   661.7 2085.12   690.2  2089.9
   722.8 2103.99   775.7 2133.53   796.1 2142.68   812.3 2146.44   829.6 2154.75
#Mann= 7 ,-1 , 0
       0      .1       0  272.41     .06       0  369.98      .1       0
   401.2    .045       0   437.8      .1       0  467.56     .05       0
  662.74      .1       0
Bank Sta=401.2,437.8
XS Rating Curve= 0 ,0
Exp/Cntr=0.3,0.1