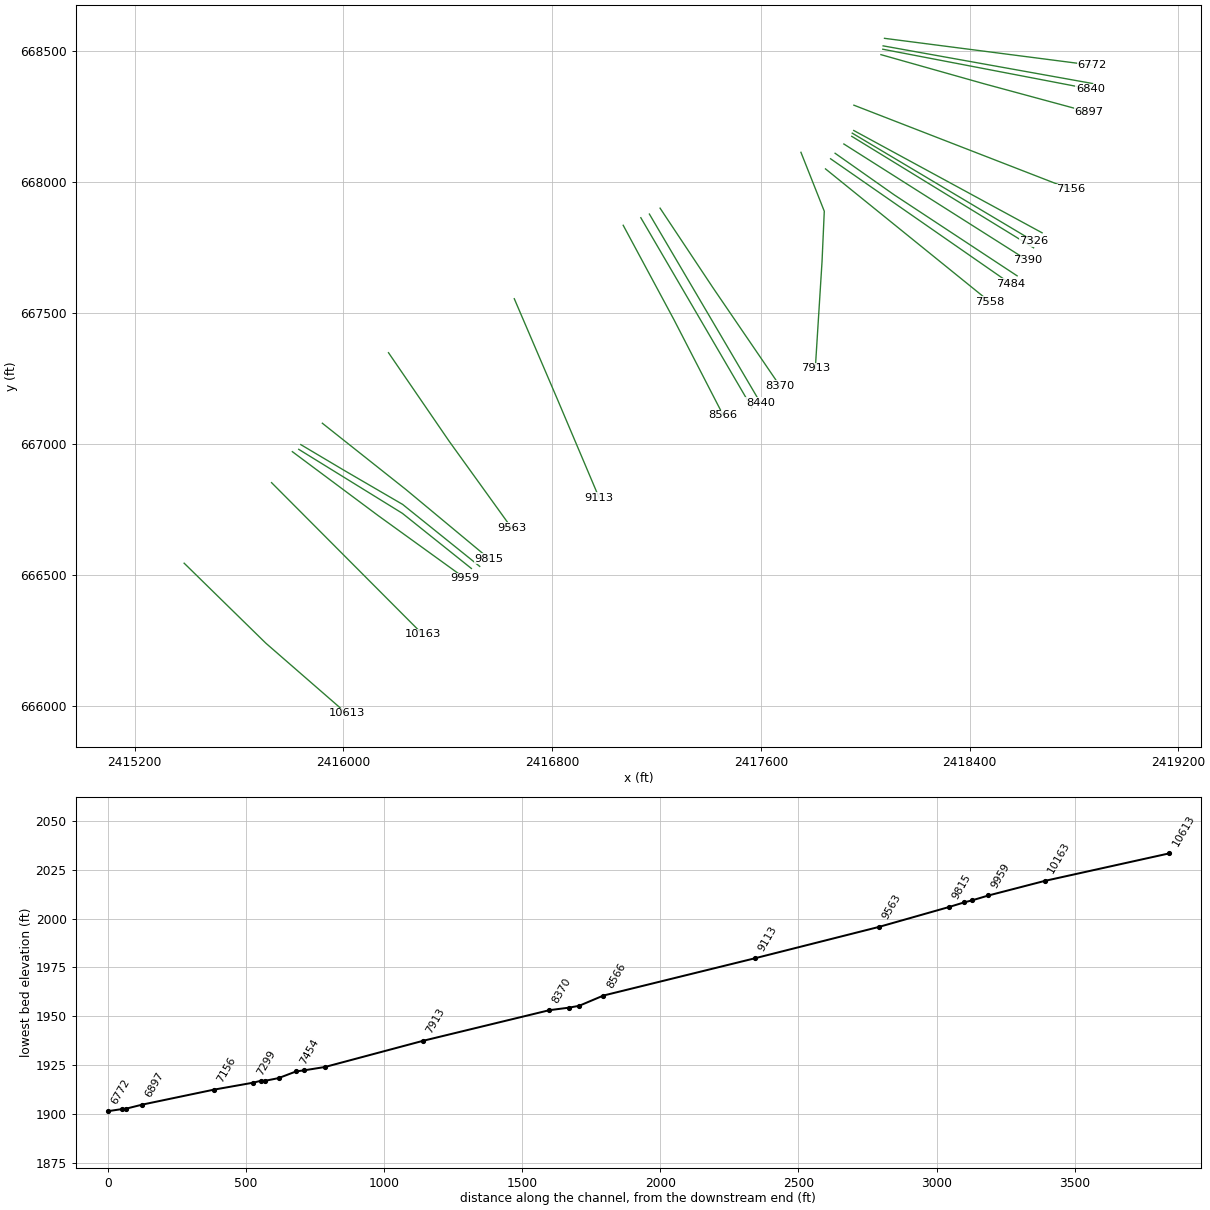
HEC-RAS study BRUSHRN.prj: BRUSHRN

--- BRUSHRN.g01 (geometry) --- (continued)

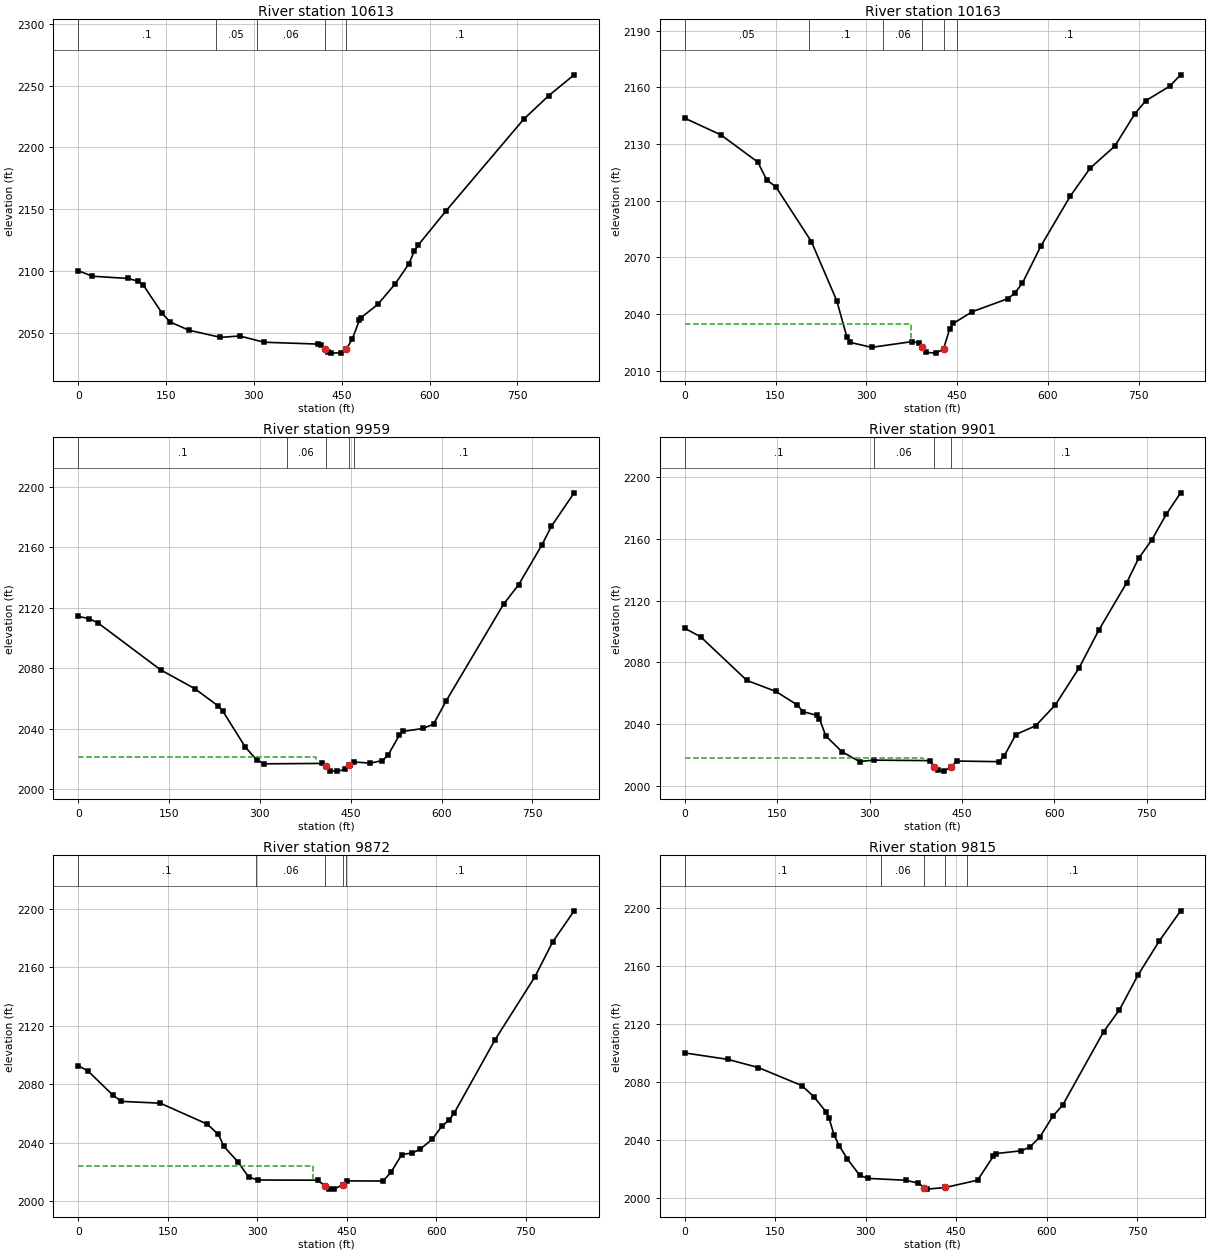
Type RM Length L Ch R = 1 ,10613   ,450.2,450,448.6
XS GIS Cut Line= 3
2415389.44274135666544.579960506     2415702.598      666238.945
2416011.80687817665970.846073585
#Sta/Elev= 30
       0 2100.13    24.2  2095.6    85.7 2093.77   102.4 2091.51   111.2 2088.39
   143.5 2065.46     157 2058.53   188.8 2051.92   242.9 2046.09   275.7 2047.21
   317.4 2042.13   409.8 2040.64   414.8  2039.9     421 2036.55   426.6 2033.86
   432.1 2033.32   449.1 2033.66   457.6 2036.29   468.2 2045.05   480.1 2060.01
   483.1 2062.17   511.5 2072.77   541.5 2089.57   564.8 2105.82   573.8 2115.87
   580.7 2120.88   627.7 2148.35   760.7 2222.78   803.5 2241.89   846.8 2258.71
#Mann= 5 ,-1 , 0
       0      .1       0   234.5     .05       0  304.87     .06       0
     421    .045       0   457.6      .1       0
Bank Sta=421,457.6
XS Rating Curve= 0 ,0
Exp/Cntr=0.3,0.1

Type RM Length L Ch R = 1 ,10163   ,201,203.9,207
XS GIS Cut Line= 3
     2415724.407       666852.36     2416013.938      666562.771
      2416303.47      666273.182
#Sta/Elev= 30
       0 2143.66    59.9 2134.77   120.9 2120.35   135.6 2110.84   150.4 2107.39
   209.2 2078.32     251 2047.11   267.9 2027.75   273.6 2024.91   308.8 2022.31
   375.4 2025.35   387.4 2024.61   392.4 2022.24   398.7 2019.64   415.6 2019.25
   427.6 2021.57   437.6 2032.08   443.9 2035.05     475 2041.19   534.4 2048.16
   545.8 2051.28   557.7  2056.3   588.2 2075.91   636.9 2102.43   669.5 2117.12
   710.5 2128.91   743.7 2146.09   761.4 2152.84     801 2160.57     819 2166.58
#Mann= 6 ,-1 , 0
       0     .05       0  205.51      .1       0  327.96     .06       0
   392.4    .045       0   427.6     .06       0   450.4      .1       0
#XS Ineff= 2 , 0
          373.72  2034.8
Permanent Ineff=
       F       F
Bank Sta=392.4,427.6
XS Rating Curve= 0 ,0
Exp/Cntr=0.3,0.1

Type RM Length L Ch R = 1 ,9959    ,57.8,57.6,58.9
XS GIS Cut Line= 3
2415804.16004287666970.6328071192416132.98604287666726.480807119
2416465.40004287666487.351807119
#Sta/Elev= 30
       0 2114.17    18.2 2112.75    33.1 2109.75     136 2078.85   192.5 2066.38
   230.4 2055.15     239 2051.36   276.1 2027.62   294.8 2019.23   307.6 2016.62
   402.2 2016.89   408.9  2015.4   416.3 2012.01   427.7 2011.79   441.3 2012.93
   447.8 2015.63   456.1 2017.82   482.2 2017.09   502.2 2018.75   511.6 2022.33
     530 2035.38   536.6 2038.09   569.4 2040.01   586.9 2042.96   607.5 2058.19
   702.4 2122.28   727.1 2135.04   765.9 2161.63   781.3 2173.79     819 2196.02
#Mann= 5 ,-1 , 0
       0      .1       0  344.08     .06       0   408.9    .045       0
   447.8     .06       0  455.58      .1       0
#XS Ineff= 2 , 0
          392.58 2021.14
Permanent Ineff=
       F       F
Bank Sta=408.9,447.8
XS Rating Curve= 0 ,0
Exp/Cntr=0.5,0.3

Type RM Length L Ch R = 1 ,9901    ,28.8,29.3,30.2
XS GIS Cut Line= 3
 2415828.5929645666979.5858244262416225.88080785666735.100997746
2416490.38809879666524.338216125
#Sta/Elev= 30
       0 2102.02      26 2096.44   100.9 2068.18   148.1 2061.01   182.3 2052.38
   192.1 2047.91   214.3 2045.56   218.6 2043.47   228.9 2032.22     255 2021.99
   283.7 2015.57   306.6  2016.5   397.5 2016.16   405.3 2012.27   411.1 2009.83
   420.5 2009.36   432.4 2011.94   441.1  2015.9   509.9 2015.49   518.2 2019.01
   537.4 2033.11   569.5 2038.77   601.6 2052.37   640.1 2076.43   672.2 2100.95
   717.2 2131.55   736.4 2147.26   757.6 2159.04   781.3 2175.82   804.7 2189.82
#Mann= 4 ,-1 , 0
       0      .1       0   306.6     .06       0   405.3    .045       0
   432.4      .1       0
#XS Ineff= 3 ,-1
       0     386    2018     386   398.2    2014     444     560    2014
Permanent Ineff=
       F       F       F
Bank Sta=405.3,432.4
XS Rating Curve= 0 ,0
Exp/Cntr(USF)=0,0
Exp/Cntr=0.5,0.3

Type RM Length L Ch R = 1 ,9872    ,58.2,56.9,53.8
XS GIS Cut Line= 4
2415836.45207339 666997.589073392416002.81804852666899.133731863
 2416227.0274956 666769.008790492416522.23862365666532.417218751
#Sta/Elev= 30
       0 2092.84    16.6 2089.03    58.4  2072.5    72.4 2068.33   137.5 2067.11
   216.4 2052.72   234.9 2045.68   244.1 2037.49   267.2 2027.12   285.7 2016.47
   301.7 2014.53   401.2  2014.4   412.9 2010.69   419.8 2008.36   429.1 2008.29
     443 2011.34     451 2013.94   510.8 2013.81     524 2019.83   542.1 2031.93
   559.8 2033.03   573.4  2035.8   593.3 2042.48   609.4 2051.48   621.7 2055.63
   630.3 2060.63   698.2 2110.41   764.9 2153.44   794.9 2177.45   830.9 2198.75
#Mann= 5 ,-1 , 0
       0      .1       0  298.22     .06       0   412.9    .045       0
     443     .06       0  449.17      .1       0
#XS Ineff= 2 , 0
          393.22 2023.79
Permanent Ineff=
       F       F
Bank Sta=412.9,443
XS Rating Curve= 0 ,0
Exp/Cntr=0.5,0.3

Type RM Length L Ch R = 1 ,9815    ,256.5,252.4,247.8
XS GIS Cut Line= 3
2415919.12689625667079.2287190732416239.90889625666825.659719073
2416557.87089625666562.235719073
#Sta/Elev= 30
       0 2099.86    71.5 2095.41   121.9 2089.78   194.1 2077.32   213.7 2069.78
   234.1 2059.27   239.2 2054.83   247.7 2043.04   256.3 2035.65   269.7 2026.63
   290.1 2015.36   303.7 2013.26   366.6 2011.95   387.3  2009.9   397.2 2006.88
   402.3 2005.84     432 2006.99   485.3    2012   511.3 2028.43   516.5 2030.41
   557.8 2032.31     572 2034.92   588.8 2041.91     610 2056.18   626.4 2063.83
   694.1 2114.46   720.5 2129.65   750.9 2153.42   786.6 2177.22   821.8 2197.95
#Mann= 5 ,-1 , 0
       0      .1       0  326.01     .06       0   397.2    .045       0
     432     .06       0  467.84      .1       0
Bank Sta=397.2,432
XS Rating Curve= 0 ,0
Exp/Cntr=0.3,0.1

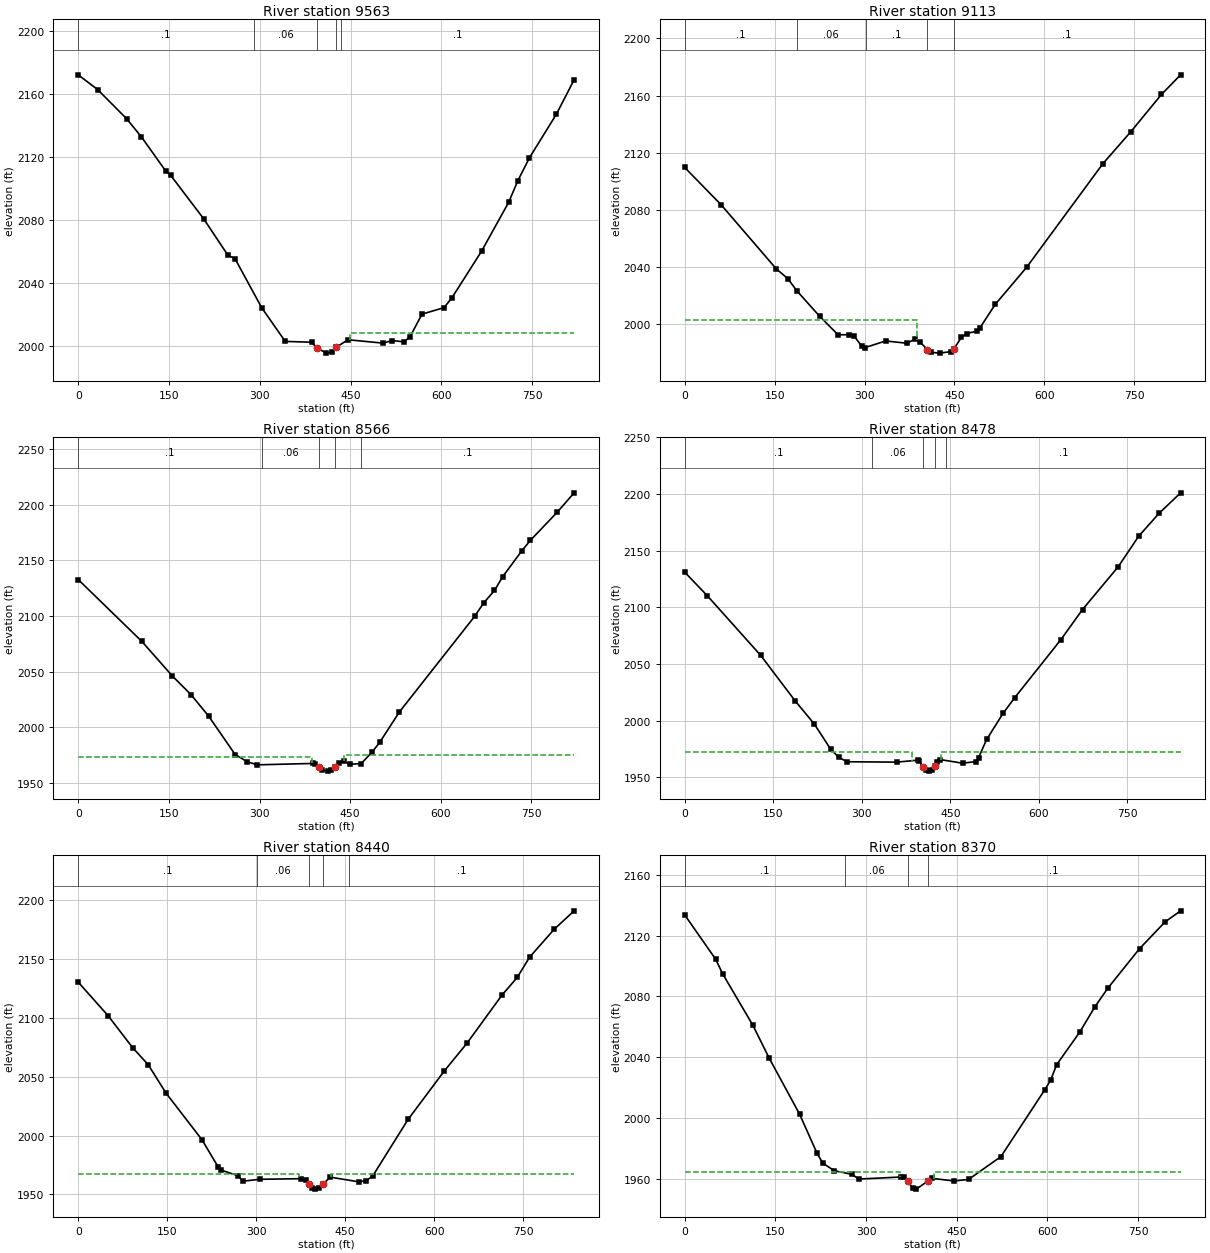
Type RM Length L Ch R = 1 ,9563    ,452.8,450,446.9
XS GIS Cut Line= 3
     2416172.645      667348.736     2416404.575      667011.332
     2416644.635      666679.083
#Sta/Elev= 30
       0 2172.14      32 2162.82    79.9 2144.34   104.2  2132.9   144.9 2110.98
   152.7 2108.45   207.1 2080.96   247.3 2057.76   258.9 2055.69   303.2 2024.45
     342 2003.14   385.7 2002.62     394 1999.04     410 1995.71     420 1996.47
   425.6 1999.31   445.7 2004.19   503.7 2002.05   518.5 2003.67   538.3 2002.89
   548.2 2006.08   567.9 2020.42   604.4 2024.56   617.6 2030.93   666.3 2060.31
     711 2091.24   726.4 2105.12   745.5 2119.58     790 2147.22   819.3 2169.04
#Mann= 5 ,-1 , 0
       0      .1       0  290.77     .06       0     394    .045       0
   425.6     .06       0  433.89      .1       0
#XS Ineff= 2 , 0
                          448.96         2008.66
Permanent Ineff=
       F       F
Bank Sta=394,425.6
XS Rating Curve= 0 ,0
Exp/Cntr=0.3,0.1

Type RM Length L Ch R = 1 ,9113    ,545.1,546.9,551.5
XS GIS Cut Line= 3
      2416654.76       667554.94     2416820.516      667169.583
     2416980.061      666794.357
#Sta/Elev= 30
       0 2109.64    60.9 2083.45   152.9 2038.57   172.1 2031.78   187.3 2023.15
   225.3 2005.35   255.8 1992.48   274.4 1992.51   283.2  1991.3   295.4 1984.37
   300.5 1983.47   335.3 1988.15   370.2 1986.57   383.7 1989.23   391.9 1987.69
     405 1982.01   411.1 1980.19   425.2 1979.63   444.2 1980.71   448.5 1982.23
   461.5 1990.63   470.2 1993.32   487.6 1995.02     492 1997.02     518 2013.76
   570.2 2039.64   697.7 2112.36   744.1 2134.61   795.3 2160.77   827.2 2174.49
#Mann= 5 ,-1 , 0
       0      .1       0  186.88     .06       0  302.03      .1       0
     405    .045       0   448.5      .1       0
#XS Ineff= 2 , 0
          387.06 2003.07
Permanent Ineff=
       F       F
Bank Sta=405,448.5
XS Rating Curve= 0 ,0
Exp/Cntr=0.3,0.1

Type RM Length L Ch R = 1 ,8566    ,88.4,88.3,88.7
XS GIS Cut Line= 3
2417072.21551223667835.4827914552417266.44451223667475.428791455
2417455.39251223667109.914791455
#Sta/Elev= 30
       0 2132.84   105.2 2077.28   155.8 2046.11     187 2029.17     216 2009.91
   259.7 1975.51   279.8 1969.02   296.1 1966.26   389.1 1967.53     392 1967.28
   397.9 1964.21   403.8 1961.27   412.7 1960.61   418.7 1961.19   424.6 1964.26
   432.2 1968.07   439.4 1969.41   450.2 1966.82   468.2 1967.36   486.3 1977.75
   498.8 1986.38   531.4 2013.79   656.1 2099.86   670.9 2111.83   688.8 2123.01
   702.4 2135.48   733.9 2158.58   748.1 2168.05   792.4 2193.28   820.6 2210.81
#Mann= 5 ,-1 , 0
       0      .1       0  304.17     .06       0   397.9    .045       0
   424.6     .06       0  468.49      .1       0
#XS Ineff= 2 , 0
          386.14 1972.98  439.36         1974.75
Permanent Ineff=
       F       F
Bank Sta=397.9,424.6
XS Rating Curve= 0 ,0
Exp/Cntr=0.5,0.3

Type RM Length L Ch R = 1 ,8478    ,37.9,37.4,37.3
XS GIS Cut Line= 2
2417139.79164695667864.3030813782417564.82992322667139.513293467
#Sta/Elev= 30
       0 2131.07    38.3 2110.24   128.9 2057.47   187.1 2017.44   219.6 1996.92
   247.4 1974.66   261.3 1967.46     275 1963.62   359.8 1963.29   394.9 1965.02
   397.8 1963.98   403.6  1959.2   409.1 1956.24   414.3 1955.34     419 1956.35
   423.6 1959.52   428.2 1963.82   432.9 1965.53   470.9 1962.34   493.2 1963.78
   497.8 1967.22   511.7  1983.4   539.5 2006.45   559.3 2020.31   637.5 2071.53
     674 2098.06   734.3  2135.7   769.3  2162.9   803.8 2183.05   840.2  2201.1
#Mann= 5 ,-1 , 0
       0      .1       0  317.36     .06       0   403.6    .045       0
   423.6     .06       0  443.26      .1       0
#XS Ineff= 2 , 0
          385.06 1971.94  434.92         1972.39
Permanent Ineff=
       F       F
Bank Sta=403.6,423.6
XS Rating Curve= 0 ,0
Exp/Cntr(USF)=0,0
Exp/Cntr=0.5,0.3

Type RM Length L Ch R = 1 ,8440    ,70.1,70.3,70
XS GIS Cut Line= 2
2417172.57696853667878.353933486 2417597.6152448667158.247762945
#Sta/Elev= 30
       0 2130.42    50.5 2101.79    91.7 2074.73     118 2060.23     148  2036.1
   208.6 1996.44   236.3 1972.97   240.9 1970.56   268.8 1965.93   278.1 1961.17
   305.9 1962.77   375.1 1963.26   383.8 1962.09   389.9 1958.35   394.2  1955.3
   398.8  1954.4   405.6 1955.21   412.8 1958.59   424.7 1964.61   473.1 1960.61
     486  1961.7   496.4 1965.46   556.1 2013.61   617.1 2054.77   655.5 2078.48
   714.7 2119.51   740.2 2134.38   761.1 2151.66   802.9 2175.56   836.2 2191.05
#Mann= 5 ,-1 , 0
       0      .1       0  300.99     .06       0   389.9    .045       0
   412.8     .06       0  456.27      .1       0
#XS Ineff= 2 , 0
          372.55 1966.96  426.36          1967.5
Permanent Ineff=
       F       F
Bank Sta=389.9,412.8
XS Rating Curve= 0 ,0
Exp/Cntr(USF)=0,0
Exp/Cntr=0.5,0.3

Type RM Length L Ch R = 1 ,8370    ,469,457.1,444.9
XS GIS Cut Line= 3
2417213.50868156667900.9455947152417416.42057145667596.628206498
2417673.08584561667221.582782883
#Sta/Elev= 30
       0 2133.66    51.4 2104.35    62.9 2094.79     113 2060.83   139.2 2039.76
     190 2002.48   218.8 1976.82   228.4 1970.21   247.5  1965.2   276.5  1962.9
   287.9 1959.75   358.2 1961.09   362.9 1960.92   368.7 1958.44     377 1953.81
   383.1 1953.11   401.8 1958.35     409 1960.22   445.4 1958.47   469.4 1959.47
     523 1974.51   595.7  2018.6   605.4 2024.98   615.1 2034.98   653.6 2056.62
   678.1 2072.94   699.6  2085.3   752.3 2111.42   794.4 2128.99   820.2 2136.32
#Mann= 4 ,-1 , 0
       0      .1       0  265.76     .06       0   368.7    .045       0
   401.8      .1       0
#XS Ineff= 2 , 0
          355.92 1964.09  411.98         1964.48
Permanent Ineff=
       F       F
Bank Sta=368.7,401.8
XS Rating Curve= 0 ,0
Exp/Cntr=0.3,0.1

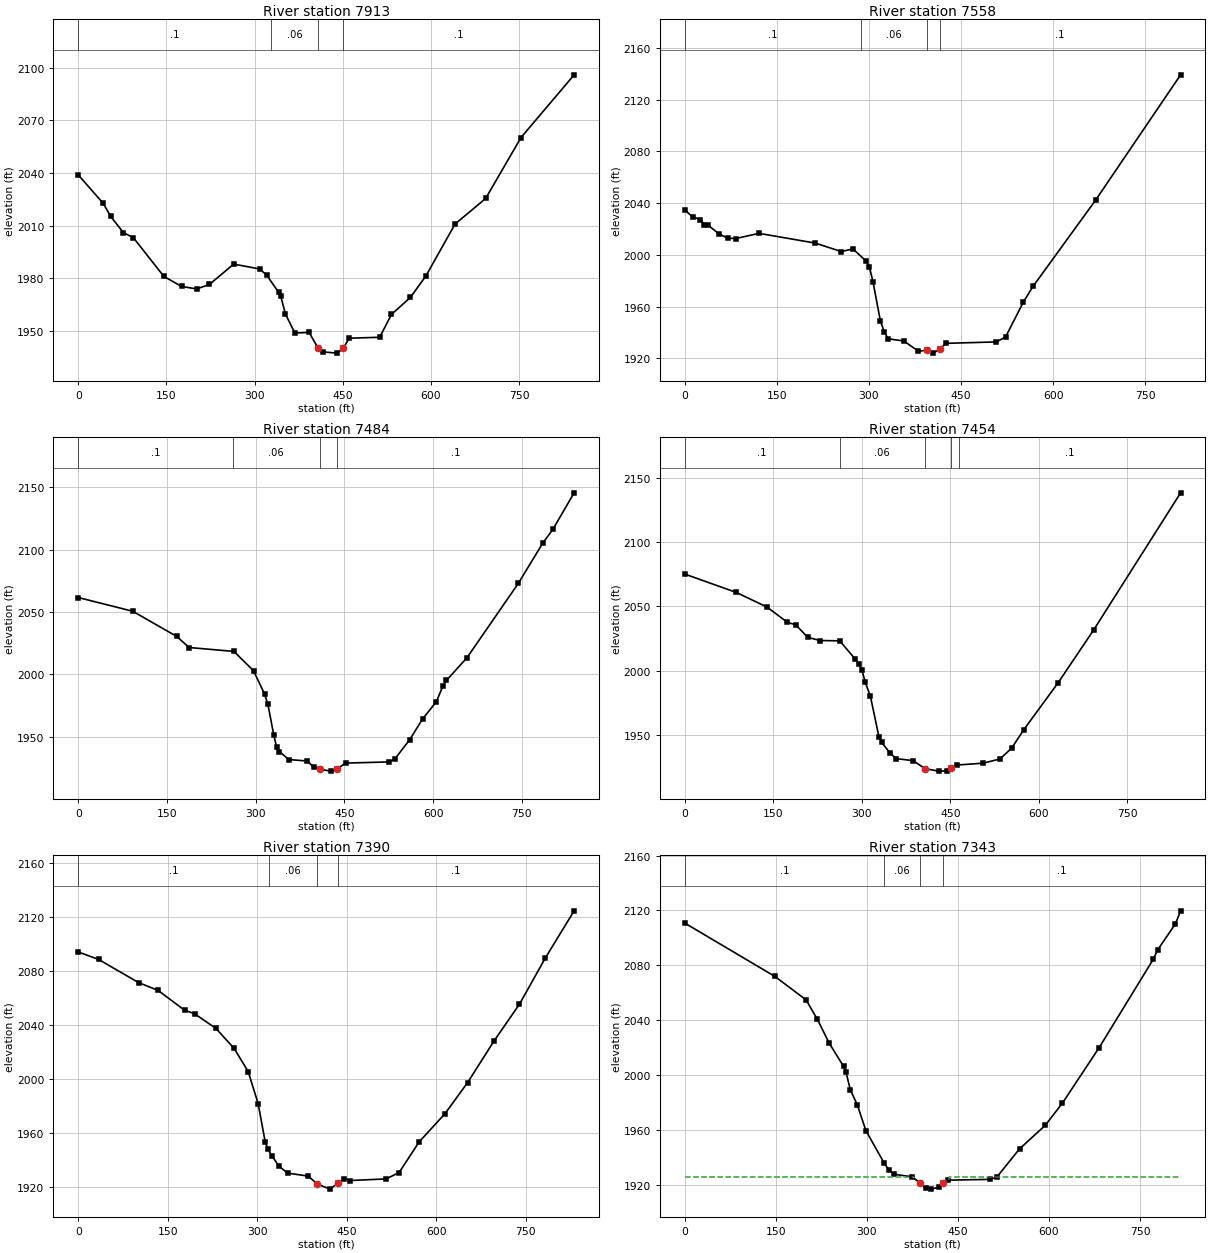
Type RM Length L Ch R = 1 ,7913    ,340.6,354.6,367.7
XS GIS Cut Line= 4
2417753.44735345668114.2657901082417842.93445627667889.198448656
     2417834.258      667696.308     2417808.484      667288.675
#Sta/Elev= 30
       0 2038.92    42.4 2022.76    55.3 2015.24    76.8 2006.08      94 2003.09
   145.7 1981.12   175.8  1975.4   201.6 1973.98   223.2 1976.53   264.5 1988.12
   308.6 1985.37   320.6 1981.85   340.9 1972.11   344.6 1969.83   352.6 1959.64
   368.6 1948.87   392.7 1949.23     4081940.383   416.7 1938.12   440.7 1937.44
   451.2 1940.23   460.8 1945.93   512.9 1946.47   532.9 1959.49     565 1969.11
   591.4 1981.33   641.1 2010.93   693.2  2025.5   753.3 2060.19   843.7 2095.88
#Mann= 4 ,-1 , 0
       0      .1       0  328.54     .06       0     408    .045       0
   451.2      .1       0
Bank Sta=408,451.2
XS Rating Curve= 0 ,0
Exp/Cntr=0.3,0.1

Type RM Length L Ch R = 1 ,7558    ,72.3,74.4,75.3
XS GIS Cut Line= 2
2417847.56667592 668050.929410172418476.34230776667543.927829934
#Sta/Elev= 30
       0 2034.76    12.8 2029.42    25.6 2027.27    31.9 2023.46    38.3 2022.89
    56.3 2016.07    70.2 2012.93    82.9 2012.59   121.1 2016.63   212.8 2009.09
     255 2002.57   274.1 2004.58   295.3 1995.31     301 1990.43   306.7 1979.13
   318.7    1949   325.1 1940.55   331.4 1935.11   356.9 1933.45   380.6 1925.54
   394.11926.272   404.9 1924.06   415.2 1926.99   425.4 1931.62   507.6 1932.73
   522.6 1936.53   551.3 1963.23   567.2 1975.56   669.2 2042.27   807.7 2139.15
#Mann= 4 ,-1 , 0
       0      .1       0  286.63     .06       0   394.1    .045       0
   415.2      .1       0
Bank Sta=394.1,415.2
XS Rating Curve= 0 ,0
Exp/Cntr(USF)=0,0
Exp/Cntr=0.5,0.3

Type RM Length L Ch R = 1 ,7484    ,28.8,29.5,33.4
XS GIS Cut Line= 2
2417867.05189778668089.5636860772418556.38498097 667612.49264555
#Sta/Elev= 30
       0 2061.62    92.1 2050.62   166.4 2030.45   187.4 2021.53   263.3 2018.39
   296.4 2002.85   315.1  1984.1   320.7 1975.82   330.4 1951.69   335.2    1942
   340.1    1938   356.1 1931.66   386.9 1930.47   398.4 1925.47   408.2 1923.84
   427.2 1922.37   437.4  1924.1     452 1928.82     525 1929.75   534.7 1931.84
     560 1947.34   582.4 1964.41   605.4 1978.06   616.2 1990.38   622.3 1995.08
   657.2 2013.37   743.9 2072.96   784.9 2104.99   802.3  2116.3   838.3  2145.6
#Mann= 4 ,-1 , 0
       0      .1       0  261.42     .06       0   408.2    .045       0
   437.4      .1       0
#XS Ineff= 2 , 0
           408.2    1923   437.4            1923
Permanent Ineff=
       F       F
Bank Sta=408.2,437.4
XS Rating Curve= 0 ,0
Exp/Cntr(USF)=0,0
Exp/Cntr=0.5,0.3

Type RM Length L Ch R = 1 ,7454    ,63.6,63.9,64.6
XS GIS Cut Line= 3
2417884.43060005668110.5658913482418111.05721806667951.650975618
2418582.00720867667642.358939653
#Sta/Elev= 30
       0  2075.1    87.6 2060.78   139.6 2049.38   173.6 2037.69   188.5 2035.52
   208.4 2025.89   229.3 2023.41   262.8 2023.16   288.7 2009.01   295.6 2004.82
   300.2 2000.53     306 1990.81   314.7 1980.01   329.1 1948.43   333.8 1944.17
   348.2 1935.67   358.3 1931.55   386.9 1929.98   407.1 1923.76   430.2 1921.82
   443.9 1922.02   450.4 1923.93     462 1926.58   506.1 1928.03   534.2  1931.3
     554 1939.72   574.6 1954.11   632.4 1990.37   692.8 2031.56   840.2 2138.28
#Mann= 5 ,-1 , 0
       0      .1       0  262.36     .06       0   407.1    .045       0
   450.4     .06       0  464.87      .1       0
Bank Sta=407.1,450.4
XS Rating Curve= 0 ,0
Exp/Cntr=0.5,0.3

Type RM Length L Ch R = 1 ,7390    ,47.2,47.4,47.6
XS GIS Cut Line= 2
2417917.95103694668146.0328628652418620.49364235667702.260117116
#Sta/Elev= 30
       0 2094.02    34.1 2088.51   101.4 2071.29   133.8 2065.57   178.2 2050.89
   194.9 2048.27   230.6 2037.46   261.2 2022.62   284.8 2005.49   301.5 1981.69
   313.2 1953.58   317.9  1947.9   324.7 1942.97   336.3 1935.39     351 1930.23
   385.6 1928.03   400.1 1922.26     422 1918.38   434.9 1922.67   445.7 1926.25
   455.2 1924.75   516.1 1925.96   537.7 1930.69   571.2 1953.32   614.7 1974.33
   652.4 1997.25   696.4 2027.86   739.4 2055.38   782.8 2089.63     831 2124.49
#Mann= 4 ,-1 , 0
       0      .1       0  319.68     .06       0   400.1    .045       0
   434.9      .1       0
Bank Sta=400.1,434.9
XS Rating Curve= 0 ,0
Exp/Cntr(USF)=0,0
Exp/Cntr=0.5,0.3

Type RM Length L Ch R = 1 ,7343    ,16.4,16.6,16.8
XS GIS Cut Line= 2
2417948.15059286668175.3595638042418645.19190367667749.495968436
#Sta/Elev= 30
       0 2110.87   148.4 2072.01   199.9 2054.93   218.7 2040.63   237.9 2023.44
   261.8 2006.38   265.5 2002.58   272.8 1989.47   284.3 1978.44   298.4 1959.71
   328.1 1936.37   336.8 1930.62   345.2 1927.81   374.7 1926.05   387.4 1921.61
   396.8 1917.84   406.2 1917.04   418.3 1918.45   424.9 1921.41   432.9 1923.56
   502.7 1924.15     514 1925.75   551.5 1946.35   593.7 1963.45     622  1979.6
   682.7 2020.16   771.8 2084.49   779.1  2091.4   808.2 2110.27   816.8 2119.76
#Mann= 4 ,-1 , 0
       0      .1       0   328.1     .06       0   387.4    .045       0
   424.9      .1       0
#XS Ineff= 2 , 0
          376.99 1925.99     436         1926.13
Permanent Ineff=
       F       F
Bank Sta=387.4,424.9
XS Rating Curve= 0 ,0
Exp/Cntr(USF)=0,0
Exp/Cntr=0.5,0.3

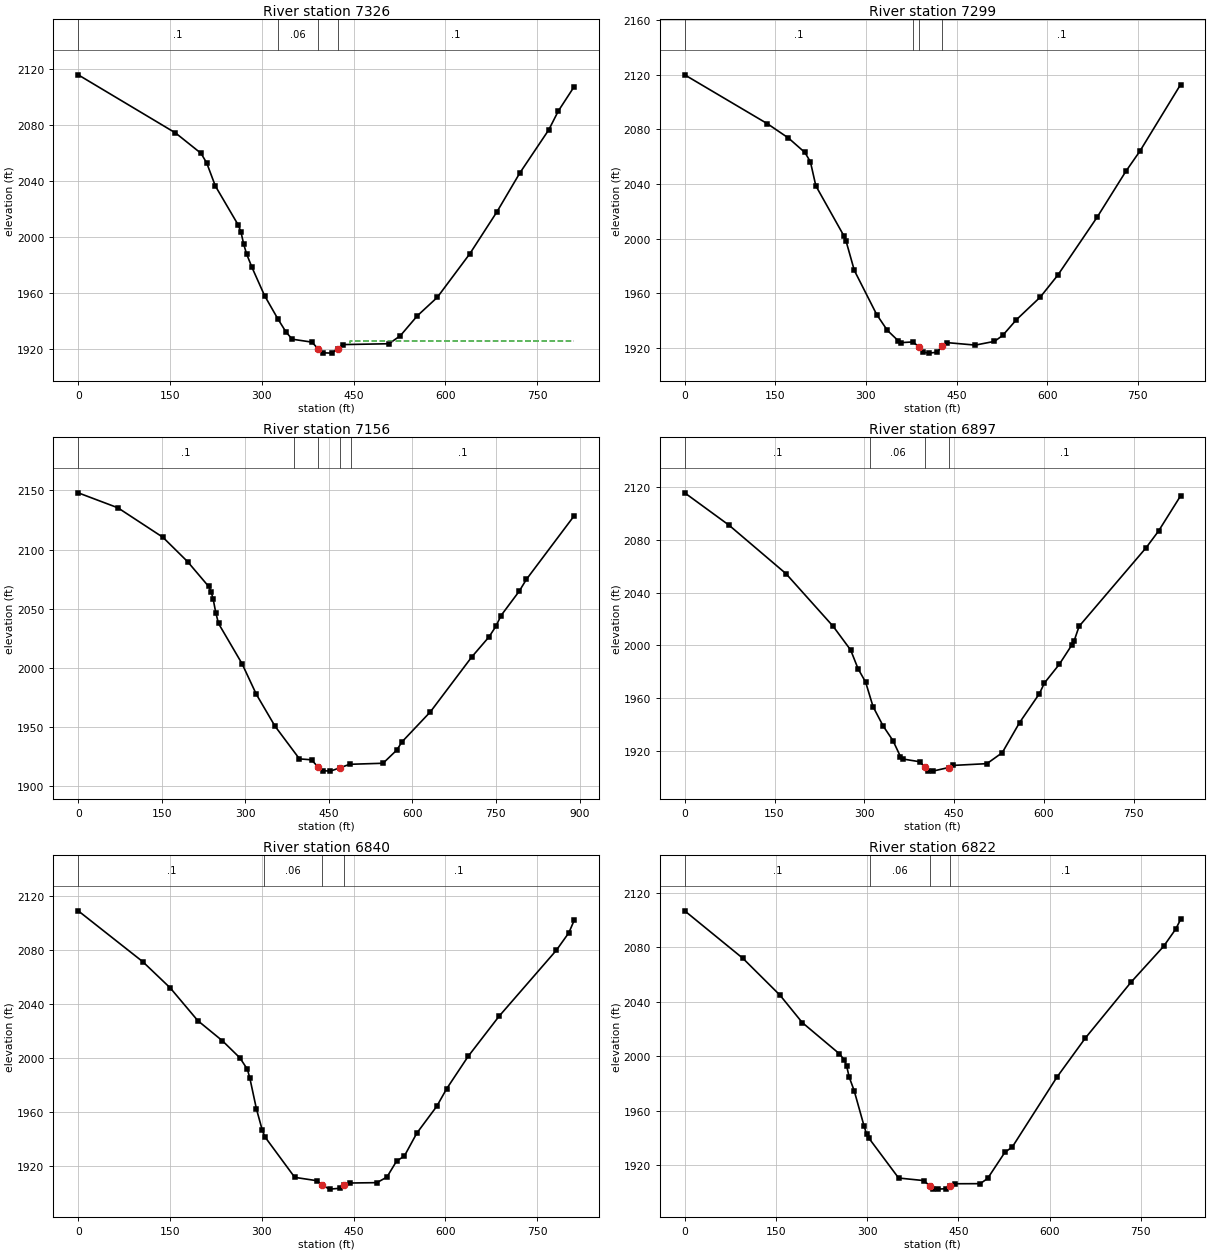
Type RM Length L Ch R = 1 ,7326    ,26.9,27.7,28.3
XS GIS Cut Line= 2
2417950.06029509668187.4543445392418647.10160589667773.685529907
#Sta/Elev= 30
       0 2115.55     159  2074.1   200.8 2059.52   210.1 2052.59   224.1 2036.29
   261.3 2008.59   265.9 2003.63   270.6 1994.53   275.2 1987.78     284 1978.18
   304.5 1958.12   326.4 1941.38   339.5 1932.18   349.7 1926.95   382.2 1924.84
     392 1920.07   400.8 1917.22   414.8 1917.01   424.1 1920.28   433.4 1923.11
   507.8  1923.7   526.3 1929.33   554.3 1943.64   586.9  1956.8   640.2 1987.98
   684.6 2017.96   721.8 2045.52   769.1  2076.3   784.7 2089.72   810.6 2107.11
#Mann= 4 ,-1 , 0
       0      .1       0   326.4     .06       0     392    .045       0
   424.1      .1       0
#XS Ineff= 2 , 0
                          444.83         1925.77
Permanent Ineff=
       F       F
Bank Sta=392,424.1
XS Rating Curve= 0 ,0
Exp/Cntr(USF)=0,0
Exp/Cntr=0.5,0.3

Type RM Length L Ch R = 1 ,7299    ,140,142.5,144.9
XS GIS Cut Line= 2
2417955.78940175668197.6394230532418677.65684143667806.787035077
#Sta/Elev= 30
       0 2119.94     137 2084.09   171.7 2073.66     199 2063.04   208.1 2056.23
   217.1 2038.61   263.9 2001.68   267.2 1998.02   280.8 1976.64   317.9 1944.26
   335.4 1932.76   353.6 1925.04   358.2 1923.73   377.5 1924.23   387.4 1920.89
   394.5 1916.87   403.6 1916.04   417.3 1916.65   426.2 1920.98     435 1923.71
     481 1921.92   512.8 1924.66   526.3 1928.96   549.2 1940.57   588.5 1957.04
   617.4 1973.05   682.9 2015.76   730.1 2049.13   753.5 2064.02   820.9 2112.84
#Mann= 4 ,-1 , 0
       0      .1       0   377.5     .06       0   387.4    .045       0
   426.2      .1       0
Bank Sta=387.4,426.2
XS Rating Curve= 0 ,0
Exp/Cntr(USF)=0,0
Exp/Cntr=0.3,0.1

Type RM Length L Ch R = 1 ,7156    ,257.5,259.3,261.4
XS GIS Cut Line= 2
 2417956.3406332668294.3330361862418786.73507078667973.097276968
#Sta/Elev= 30
       0 2147.97    71.2 2135.31   152.1 2110.33   196.3 2089.77   234.2 2068.73
   238.5 2064.47   242.4  2057.8     247 2046.48   251.9 2037.41   294.2 2003.32
   319.9 1977.39   353.2  1950.6   397.2 1922.84   418.9 1922.04   431.3 1915.55
     440 1912.82   452.8 1912.47   470.1 1915.32   487.2 1918.24   547.3 1919.14
   571.8 1930.21   581.6 1937.38   632.3 1962.65   706.5 2009.05   737.5 2026.03
   749.8 2034.92   759.1  2044.1   791.7 2064.67   804.6 2074.67   890.4 2128.52
#Mann= 5 ,-1 , 0
       0      .1       0  387.65     .06       0   431.3    .045       0
   470.1     .06       0  489.16      .1       0
Bank Sta=431.3,470.1
XS Rating Curve= 0 ,0
Exp/Cntr(USF)=0,0
Exp/Cntr=0.3,0.1

Type RM Length L Ch R = 1 ,6897    ,55.9,57.1,59
XS GIS Cut Line= 3
2418059.95475554668487.3783207212418455.22775554668376.134320721
2418858.39176519668267.287229049
#Sta/Elev= 30
       0  2115.5      74 2091.02   169.1 2054.33   248.1 2014.35   277.2 1996.48
   289.6 1982.27   302.1 1972.28   314.6  1953.6   331.2 1939.17   347.8 1927.94
   360.3 1915.85   364.4 1913.97   393.5 1911.85   400.5 1907.61     406 1904.98
   414.3 1904.81   440.6 1907.51   447.4 1909.11   504.7 1910.47   530.3 1918.75
   559.3 1941.59   592.4 1963.48   600.7 1971.49   625.6 1985.67   646.6 2000.36
   650.4 2003.51   658.7 2014.47   770.6 2073.95   791.3 2086.54   828.2 2113.24
#Mann= 4 ,-1 , 0
       0      .1       0  309.88     .06       0   400.5    .045       0
   440.6      .1       0
Bank Sta=400.5,440.6
XS Rating Curve= 0 ,0
Exp/Cntr=0.5,0.3

Type RM Length L Ch R = 1 ,6840    ,17.9,17.7,18
XS GIS Cut Line= 2
 2418067.1523154668508.081664268 2418863.3672682668355.864099762
#Sta/Elev= 30
       0 2109.31   105.5 2071.56   150.3 2052.15   195.5 2027.79   235.8 2012.82
   264.3 2000.17   276.5 1991.72   280.6    1985   291.3 1962.27   300.9 1946.45
   305.1 1941.61   353.9 1911.52   390.4 1909.01   398.7 1905.65   410.9 1902.78
   427.2 1903.38   434.9 1905.82   443.5 1907.31   488.3 1907.59   504.6 1911.74
   520.3 1923.54   533.1 1927.34   553.4  1944.3     586 1964.22   602.3 1977.33
   637.4 2001.35   687.8 2031.03   781.5 2080.03   801.9    2093   810.6 2102.21
#Mann= 4 ,-1 , 0
       0      .1       0  304.21     .06       0   398.7    .045       0
   434.9      .1       0
#XS Ineff= 2 , 0
           398.7    1904   434.9            1904
Permanent Ineff=
       F       F
Bank Sta=398.7,434.9
XS Rating Curve= 0 ,0
Exp/Cntr(USF)=0,0
Exp/Cntr=0.5,0.3

Type RM Length L Ch R = 1 ,6822    ,49.6,50.3,52.1
XS GIS Cut Line= 2
2418068.44716485668520.9414566232418871.17104608 668377.12873716
#Sta/Elev= 30
       0 2106.76    95.8 2071.86   156.8 2044.81   193.3 2024.76   254.3 2001.87
   262.4 1997.41   266.5 1992.53   270.5 1984.77   278.7 1974.76   294.9 1948.92
     299 1943.01     303 1939.86   351.8 1910.65   393.2 1908.77   403.5 1904.69
   408.7 1902.69   416.8  1902.5     429 1902.81   437.1 1904.84   445.3 1906.45
   485.9 1906.51   498.1 1910.31   526.6 1929.57   538.7 1933.41   611.9 1984.55
   658.7  2013.3   733.8  2054.3   787.5 2080.68   807.3 2093.26   815.5 2100.42
#Mann= 4 ,-1 , 0
       0      .1       0  304.91     .06       0   403.5    .045       0
   437.1      .1       0
Bank Sta=403.5,437.1
XS Rating Curve= 0 ,0
Exp/Cntr(USF)=0,0
Exp/Cntr=0.5,0.3

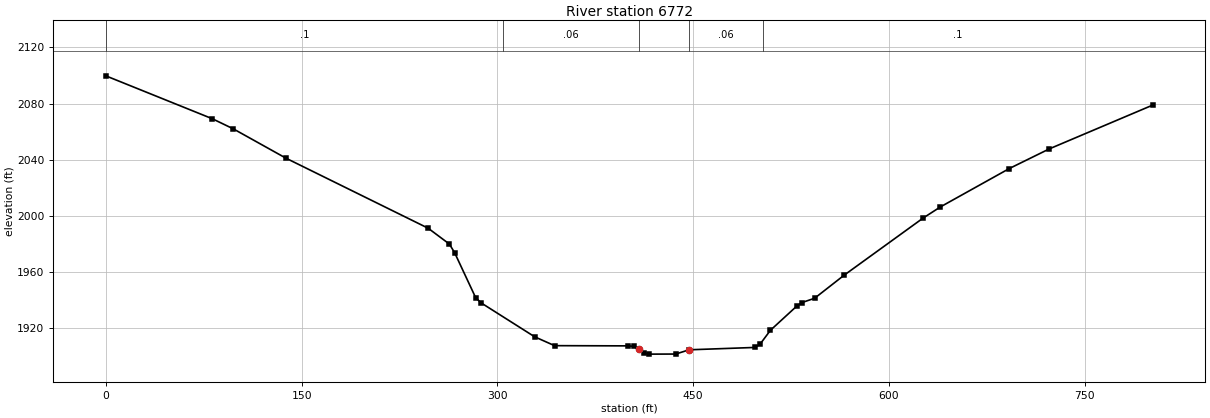
Type RM Length L Ch R = 1 ,6772    ,203.2,208.9,212.5
XS GIS Cut Line= 2
2418073.73045917668549.7053137152418869.46534118668447.274601846
#Sta/Elev= 30
       0 2099.76    81.7 2069.14    97.8 2061.92   138.1 2041.04     247 1991.14
   263.2 1979.89   267.2 1973.82   283.3 1941.78   287.4 1938.03   328.6 1913.76
   343.8 1907.47   400.3 1907.31   404.3 1906.94   408.4 1904.73   412.4 1902.16
   416.4 1901.43   436.6 1901.49   446.9 1904.51   497.1 1906.19   501.1 1908.35
   509.2 1918.45   529.3 1935.61   533.4 1938.21     543 1941.23   565.6 1957.65
   626.1 1998.36   639.4 2006.34   692.2  2033.7   722.9 2047.73   802.3 2079.01
#Mann= 5 ,-1 , 0
       0      .1       0  304.42     .06       0   408.4    .045       0
   446.9     .06       0  503.16      .1       0
Bank Sta=408.4,446.9
XS Rating Curve= 0 ,0
Exp/Cntr(USF)=0,0
Exp/Cntr=0.3,0.1