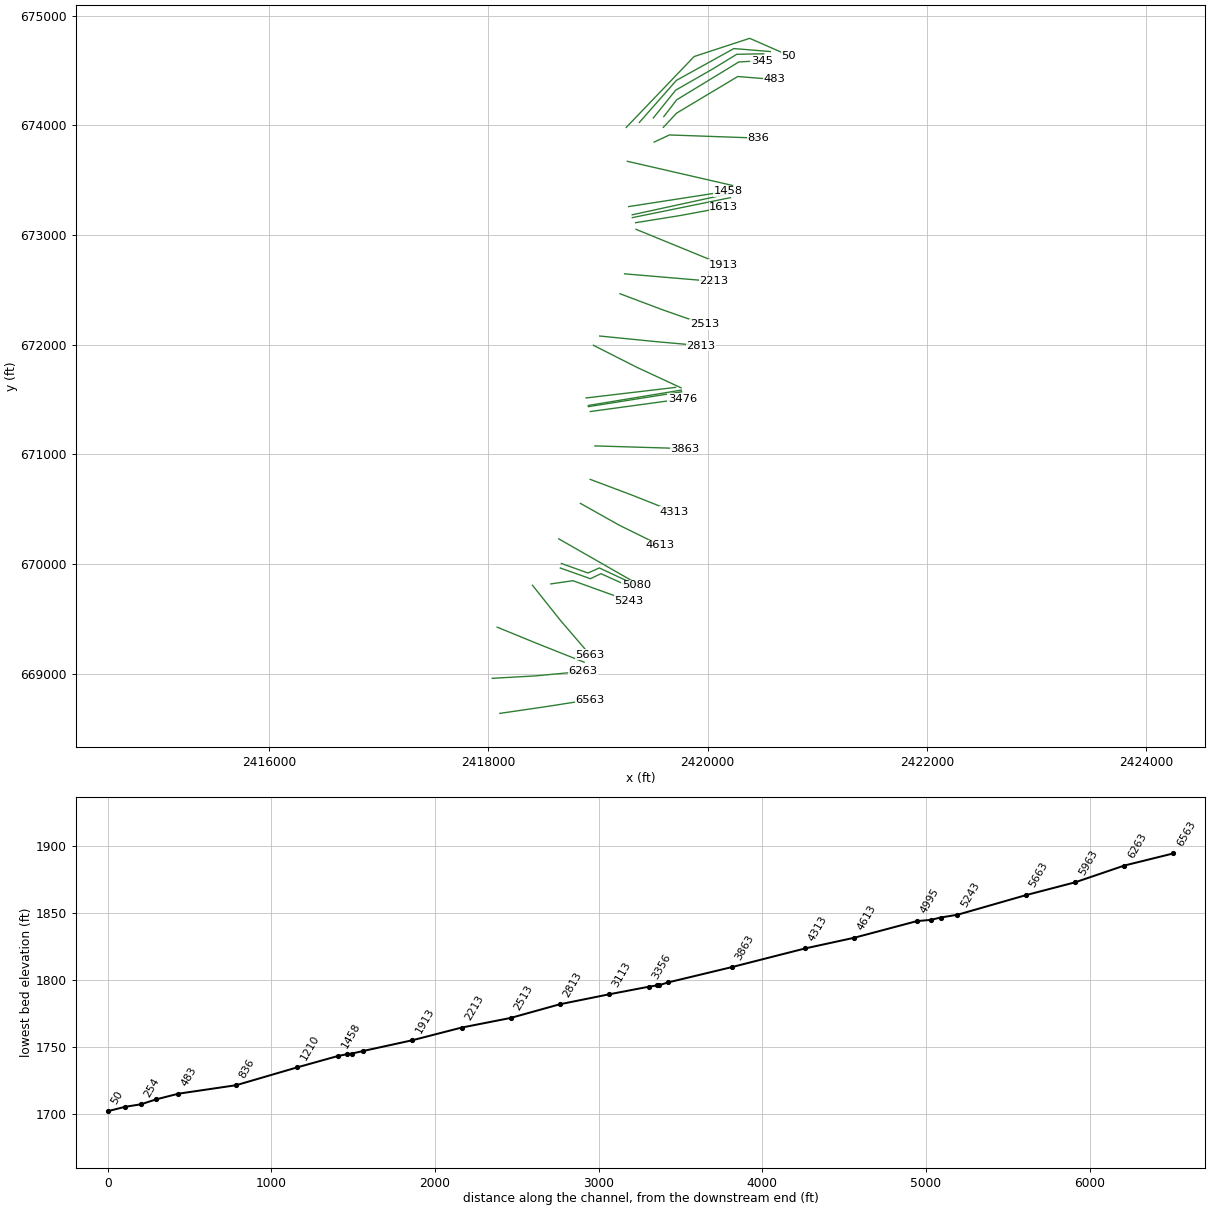
HEC-RAS study BRUSHRN.prj: BRUSHRN

--- BRUSHRN.g01 (geometry) --- (continued)

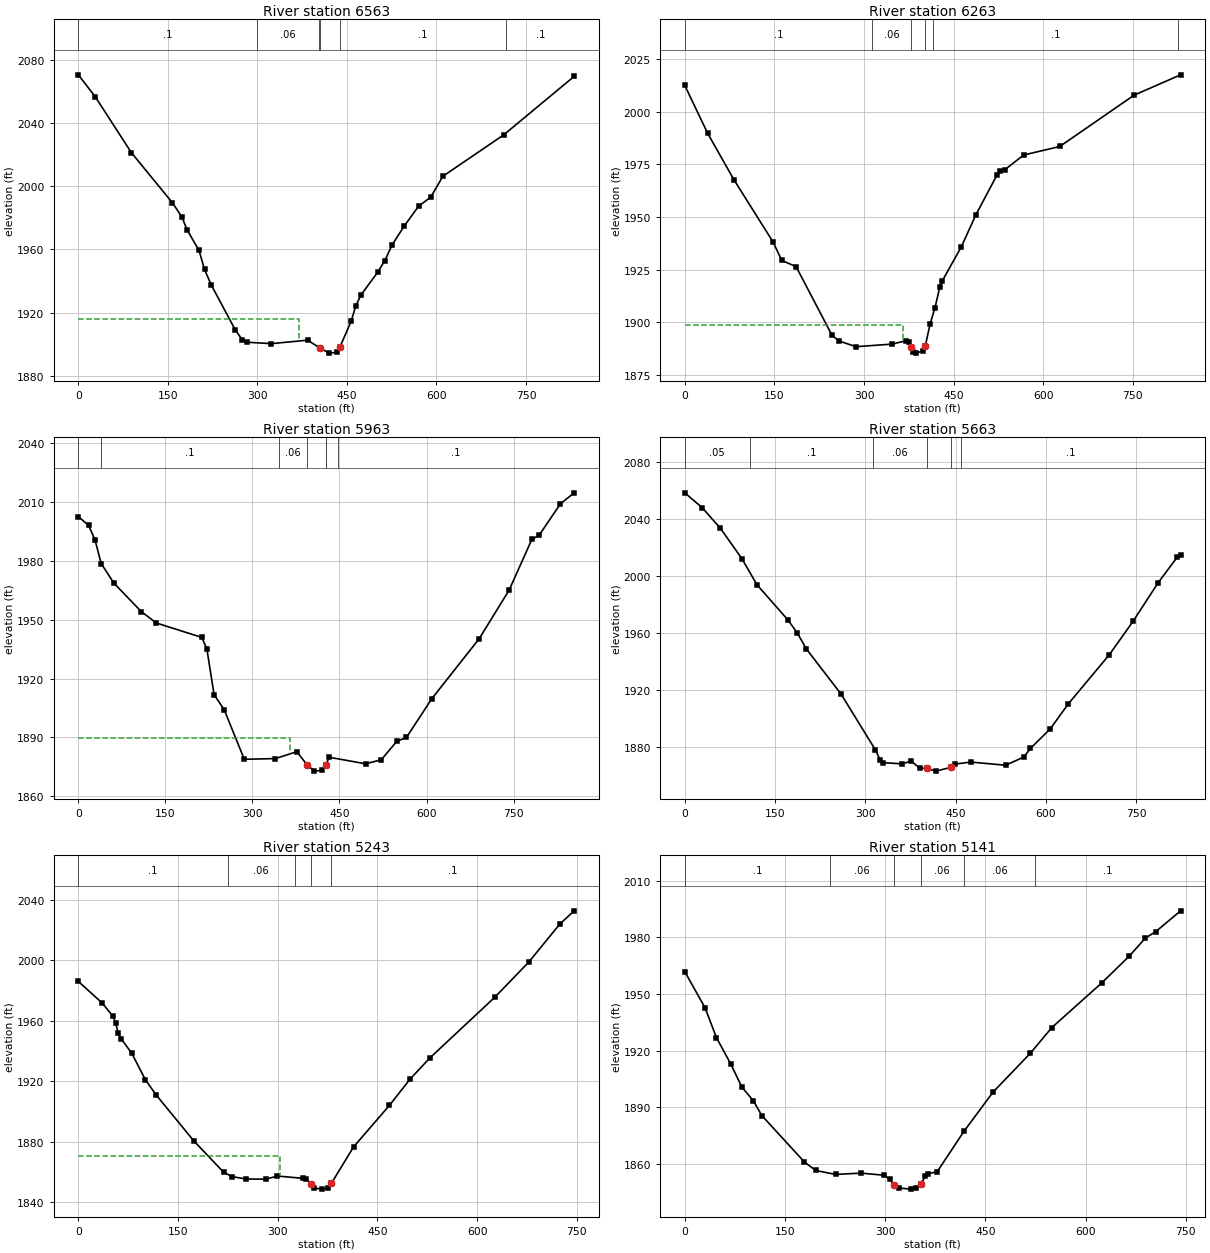
Type RM Length L Ch R = 1 ,6563    ,299.7,300,299.9
XS GIS Cut Line= 3
      2418106.71668637.572874555     2418525.249      668698.614
     2418928.072      668761.803
#Sta/Elev= 30
       0 2070.41    28.3 2056.57      89 2021.12   157.7 1989.45   173.9 1980.26
   181.9  1972.5   202.2 1959.33   211.4  1947.3   222.4 1937.69   262.8 1909.12
   274.9 1902.69   283.4 1901.22   323.4 1900.34   384.1 1902.53   404.3  1897.7
   420.4 1894.34   432.6 1894.86   438.5 1898.38   456.9 1914.35     465 1924.39
   473.5 1931.12   501.3 1945.41   513.6 1952.92   525.7 1962.84   545.9 1974.69
   570.2 1987.35   590.5 1993.02   610.7 2006.22   712.6  2032.4   830.7 2069.44
#Mann= 6 ,-1 , 0
       0      .1       0  299.65     .06       0  403.79      .1       0
   404.3    .045       0   438.5      .1       0  717.23      .1       0
#XS Ineff= 2 , 0
          369.61 1915.99
Permanent Ineff=
       F       F
Bank Sta=404.3,438.5
XS Rating Curve= 0 ,0
Exp/Cntr=0.3,0.1

Type RM Length L Ch R = 1 ,6263    ,305.4,300,292.5
XS GIS Cut Line= 3
2418036.66400965668957.265265365     2418427.489      668979.087
     2418864.198      669020.282
#Sta/Elev= 30
       0 2012.61    38.1 1989.92    82.2 1967.77   147.7 1938.18   162.3  1929.4
   186.4 1926.39   246.5 1893.73   258.5 1891.05   286.5 1888.34   346.6 1889.56
   370.7  1891.2   374.7 1890.48   378.1 1887.99   382.7  1885.7   386.7 1885.28
   398.7 1886.28   402.7  1888.8   410.8 1899.33   418.8 1906.79   426.8 1916.58
   430.9 1919.54     463 1935.88   487.1 1950.93   522.7 1970.03   527.3  1971.7
   535.3 1972.45   567.5 1979.52   627.7 1983.56   752.3 2007.99   830.1 2017.65
#Mann= 6 ,-1 , 0
       0      .1       0  314.09     .06       0   378.1    .045       0
   402.7     .06       0  416.01      .1       0  826.53      .1       0
#XS Ineff= 2 , 0
           365.5 1898.48
Permanent Ineff=
       F       F
Bank Sta=378.1,402.7
XS Rating Curve= 0 ,0
Exp/Cntr=0.3,0.1

Type RM Length L Ch R = 1 ,5963    ,306.5,300,290.1
XS GIS Cut Line= 3
2418082.31832517669423.554556324     2418459.793      669268.927
     2418874.835      669104.345
#Sta/Elev= 30
       0 2002.65    17.8 1998.19    28.9 1990.59    39.4 1978.73      61 1968.81
   108.5 1954.19   134.5 1948.37   212.8 1941.01   221.6 1935.01   233.9 1911.82
   251.2  1904.2     286 1878.82   339.4 1879.18   376.5 1882.69   393.8 1876.15
   406.8 1872.78   419.7 1873.17   426.11875.975   432.6 1879.84     495 1876.52
     522 1878.57   548.8    1888   565.4 1889.96     609  1909.7   690.8 1940.38
   742.4 1965.19   781.5 1991.05   794.1 1993.18   830.8 2009.23   854.4  2014.8
#Mann= 7 ,-1 , 0
       0     .05       0   39.39      .1       0  345.26     .06       0
   393.8    .045       0   426.1     .06       0  426.11     .06       0
  447.12      .1       0
#XS Ineff= 2 , 0
           365.5 1889.44
Permanent Ineff=
       F       F
Bank Sta=393.8,426.1
XS Rating Curve= 0 ,0
Exp/Cntr=0.3,0.1

Type RM Length L Ch R = 1 ,5663    ,411.3,419.5,428.7
XS GIS Cut Line= 3
2418404.27316356669805.082674827     2418661.249      669482.493
     2418929.418      669170.573
#Sta/Elev= 30
       0 2058.61    28.9  2048.2    59.1 2033.75    94.9 2012.35     120 1994.02
   171.3  1969.4   186.9 1960.24   202.2 1948.88   259.5  1917.4   316.4 1878.32
     325 1870.74   330.1 1869.18   360.8 1868.33   376.1 1870.26   390.4 1865.28
   401.7 1865.12   417.2 1863.22   441.6 1865.84   448.8 1868.16   475.2 1869.57
   533.2 1867.36   563.5 1873.19   574.3 1879.19   607.1 1892.85   637.3  1910.5
   705.4 1944.98   745.1 1968.61   786.4 1995.47   818.1 2013.41   823.8 2015.09
#Mann= 6 ,-1 , 0
       0     .05       0  107.51      .1       0     313     .06       0
   401.7    .045       0   441.6     .06       0  458.95      .1       0
Bank Sta=401.7,441.6
XS Rating Curve= 0 ,0
Exp/Cntr=0.3,0.1

Type RM Length L Ch R = 1 ,5243    ,88.1,102.2,117
XS GIS Cut Line= 3
2418571.12673008669818.0901836272418772.52227696669847.362792186
2419283.03657023669663.530810436
#Sta/Elev= 30
       0 1985.92      36 1971.55    52.2 1962.79    56.2 1958.38    60.2 1951.55
    64.3 1948.08    80.5 1938.29   100.7 1921.03   116.8 1910.97   173.4 1880.63
   218.6  1859.7   231.4 1856.78   252.6 1855.24   282.4  1855.1   299.4 1857.19
   337.7 1855.69   343.2 1855.07   349.4 1852.22   354.7 1849.21   367.4 1848.53
   375.9 1849.25   380.7 1852.28   414.2 1876.49   468.2 1903.96   499.4 1921.41
     529  1935.3   626.8 1975.48   677.8 1998.69   724.5 2023.82   746.1 2032.59
#Mann= 5 ,-1 , 0
       0      .1       0  224.66     .06       0   325.7      .1       0
   349.4    .045       0   380.7      .1       0
#XS Ineff= 2 , 0
          303.08 1870.17
Permanent Ineff=
       F       F
Bank Sta=349.4,380.7
XS Rating Curve= 0 ,0
Exp/Cntr(USF)=0,0
Exp/Cntr=0.5,0.3

Type RM Length L Ch R = 1 ,5141    ,65.4,61.6,66.9
XS GIS Cut Line= 4
 2418658.0823694669963.0283130482418932.02240198669865.537217373
2419028.30845404669911.3363766492419342.61796785669769.072351068
#Sta/Elev= 30
       0  1961.8    30.4 1942.61    47.4 1926.81    68.6    1913    85.6 1900.51
   102.6 1893.39   115.3 1885.51   179.1 1860.85     196 1856.37   225.7 1854.27
   263.9 1854.95   298.2 1853.85   307.1 1851.74     3131848.692   320.4 1847.07
   338.1 1846.47   346.9  1846.9   353.21849.084   360.2 1853.28   364.7 1854.67
   377.9 1855.69   417.9 1877.09   461.5 1897.91   517.5 1918.58   549.4 1932.12
     624 1955.75   665.6 1970.09   689.7 1979.69   704.9 1982.98   742.4 1994.09
#Mann= 6 ,-1 , 0
       0      .1       0   217.7     .06       0     313    .045       0
   353.2     .06       0   417.9     .06       0   524.5      .1       0
#XS Ineff= 2 , 0
          302.04  1851.6  363.27          1851.6
Permanent Ineff=
       F       F
Bank Sta=313,353.2
XS Rating Curve= 0 ,0
Exp/Cntr(USF)=0,0
Exp/Cntr=0.5,0.3

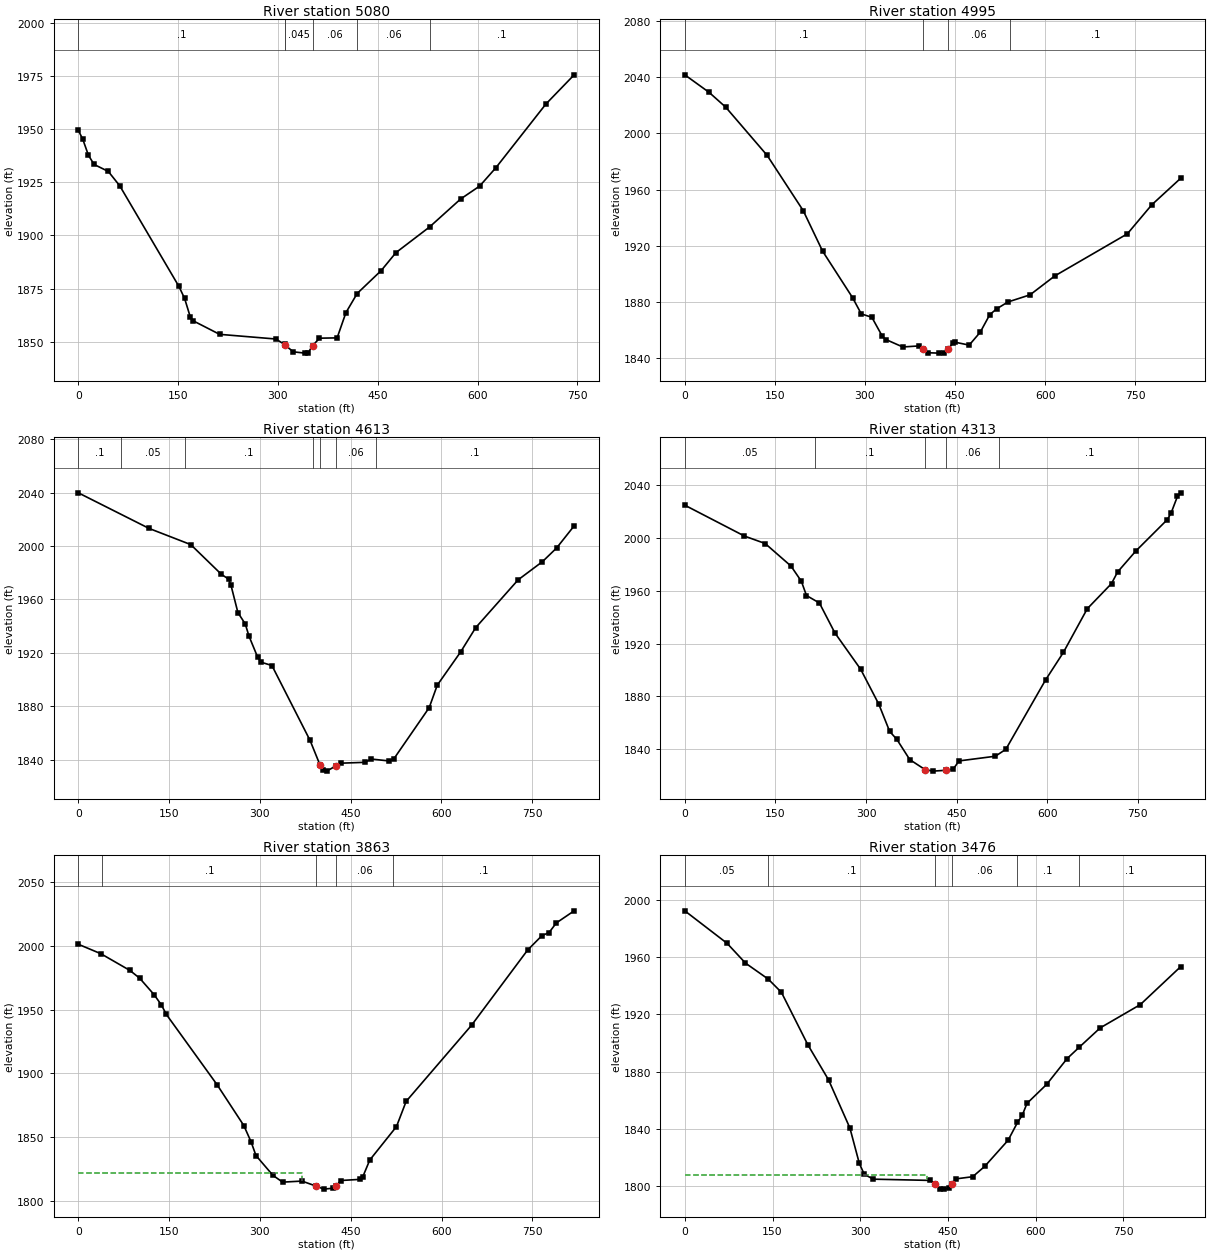
Type RM Length L Ch R = 1 ,5080    ,97.4,84.3,58.9
XS GIS Cut Line= 4
2418668.40346492670004.1367052572418909.71202646669917.555170617
2419013.92391387669963.5750684062419353.19782842669804.296921757
#Sta/Elev= 30
       0 1949.38     6.7 1945.19    15.2 1937.65    23.7 1933.35      45 1930.08
    62.2 1923.34   151.2 1876.01   159.7 1870.39   168.2 1861.72   172.5 1859.89
   212.3 1853.52   296.9 1851.32   309.91848.753   310.6 1848.48   323.1  1845.3
   340.6 1844.69     345 1844.77   352.2 1848.24   362.4 1851.71   388.9 1851.86
   402.1  1863.7     419 1872.71   455.2 1883.51   477.3 1891.92   527.8 1903.97
   574.5 1917.12     603 1923.17   627.5 1931.82   702.6 1961.73   745.1 1975.47
#Mann= 6 ,-1 , 0
       0      .1       0   309.9    .045       0   310.6    .045       0
   352.2     .06       0     419     .06       0   527.8      .1       0
Bank Sta=310.6,352.2
XS Rating Curve= 0 ,0
Exp/Cntr(USF)=0,0
Exp/Cntr=0.5,0.3

Type RM Length L Ch R = 1 ,4995    ,382.4,382.4,383.4
XS GIS Cut Line= 2
2418643.65736051 670228.86281458 2419360.3406639 669818.88981458
#Sta/Elev= 30
       0 2041.54    40.4  2029.1    68.1 2018.58   137.2 1984.26   197.2 1945.04
   229.5 1916.22   279.3 1883.25   293.9 1871.66   311.5 1869.24   329.1 1855.63
   335.3 1853.37     363 1848.15   390.6 1848.91   396.5 1847.04   404.5 1844.06
   422.9 1843.78   432.1 1844.13     439 1846.71   445.9 1850.72   450.6 1851.49
   473.6 1849.48     492 1858.65   507.9 1871.14   519.5 1875.29   538.1 1880.12
     575 1885.21   616.2 1898.66     737 1928.56   777.7 1949.19   825.7    1968
#Mann= 4 ,-1 , 0
       0      .1       0   396.5    .045       0     439     .06       0
   541.5      .1       0
Bank Sta=396.5,439
XS Rating Curve= 0 ,0
Exp/Cntr=0.3,0.1

Type RM Length L Ch R = 1 ,4613    ,298.2,300,301.3
XS GIS Cut Line= 3
     2418840.741       670552.54     2419198.446      670351.668
     2419565.823      670171.069
#Sta/Elev= 30
       0 2039.89     117  2013.2   185.8 2001.11   236.3  1978.9   248.4  1975.2
   252.4  1970.5   263.8 1950.11   275.9 1941.69   282.1 1932.51   296.5 1916.63
   302.3 1912.94     320 1910.49   383.1 1854.32   399.3 1836.18   405.2 1831.87
   410.6 1831.36   426.7 1835.54     435 1837.33   473.8 1837.96   484.5 1840.41
   513.1 1839.01   521.6 1840.59     580 1878.95   593.3 1895.76   632.2 1920.85
   656.8 1938.85     727  1974.7   767.2 1988.33   790.6 1998.57   819.6 2015.14
#Mann= 7 ,-1 , 0
       0      .1       0   70.62     .05       0  176.38      .1       0
   387.9     .06       0   399.3    .045       0   426.7     .06       0
  492.15      .1       0
Bank Sta=399.3,426.7
XS Rating Curve= 0 ,0
Exp/Cntr=0.3,0.1

Type RM Length L Ch R = 1 ,4313    ,445.4,450,456.9
XS GIS Cut Line= 3
     2418930.246      670771.262     2419313.079      670627.174
     2419695.682      670475.218
#Sta/Elev= 30
       0 2024.79    98.8 2001.39     133 1995.77   175.8 1978.67   192.9  1967.2
   201.4 1956.39   222.8 1950.72   248.4 1928.09   291.2 1900.46   321.1  1874.1
   339.1 1853.46     351 1847.42   372.4  1832.1   397.7 1824.54   410.8 1823.39
   432.4 1824.03   444.4 1824.98   453.9 1831.12   514.1 1834.68   531.4 1839.93
   597.1  1892.4   626.6 1913.27   666.2 1946.39   706.3 1965.43   716.4 1974.23
   746.5 1990.06   798.7 2013.88   804.9 2018.84   815.4 2031.39   820.7 2034.15
#Mann= 5 ,-1 , 0
       0     .05       0  215.87      .1       0   397.7    .045       0
   432.4     .06       0  520.25      .1       0
Bank Sta=397.7,432.4
XS Rating Curve= 0 ,0
Exp/Cntr=0.3,0.1

Type RM Length L Ch R = 1 ,3863    ,383.9,386.3,389.1
XS GIS Cut Line= 3
     2418973.514      671076.479     2419382.831      671064.251
     2419792.149      671052.024
#Sta/Elev= 30
       0 2001.17    37.2 1993.78    85.3 1980.65   101.3  1974.6   125.3 1961.63
   137.3 1953.58   145.3 1946.28   229.3 1891.08   273.4 1859.14   285.4 1846.35
   293.4  1835.7   321.4 1820.18   337.4 1814.86   369.4 1815.68   393.4 1811.64
   405.4 1809.38   421.4 1810.13   426.3 1811.98   433.4 1816.12   465.4 1817.04
   469.4 1818.52   481.4 1832.17   525.5 1858.37   541.5 1878.14   649.5 1937.74
   742.1 1996.63   765.6 2007.86   777.6 2010.39   789.6 2017.91     819 2027.37
#Mann= 5 ,-1 , 0
       0     .05       0   39.59      .1       0   393.4    .045       0
   426.3     .06       0  520.13      .1       0
#XS Ineff= 2 , 0
          369.21 1822.18
Permanent Ineff=
       F       F
Bank Sta=393.4,426.3
XS Rating Curve= 0 ,0
Exp/Cntr=0.3,0.1

Type RM Length L Ch R = 1 ,3476    ,56.2,56.5,56.8
XS GIS Cut Line= 2
 2418931.0801423671389.7938429922419771.00660541 671504.53789533
#Sta/Elev= 30
       0 1992.14    72.3 1969.48   103.7  1955.7   142.8 1944.47   165.2 1935.29
   210.2 1898.83   245.8 1874.22   282.3 1840.63   298.4 1815.95   306.9  1808.3
   322.6 1804.98   419.5 1804.12   427.11801.693   435.7 1798.32   443.7 1798.04
   451.8 1798.77   457.51801.754   463.9 1805.21   492.2  1806.7   512.7 1813.88
   552.8 1832.16   568.8 1844.54     577 1849.61     585 1857.82   618.7 1871.12
   653.7 1889.11   673.9 1896.83   710.2  1910.5   778.8 1926.74   847.7 1953.17
#Mann= 6 ,-1 , 0
       0     .05       0   142.8      .1       0   427.1    .045       0
   457.5     .06       0   568.8      .1       0   673.9      .1       0
#XS Ineff= 2 , 0
          414.49 1808.12
Permanent Ineff=
       F       F
Bank Sta=427.1,457.5
XS Rating Curve= 0 ,0
Exp/Cntr(USF)=0,0
Exp/Cntr=0.5,0.3

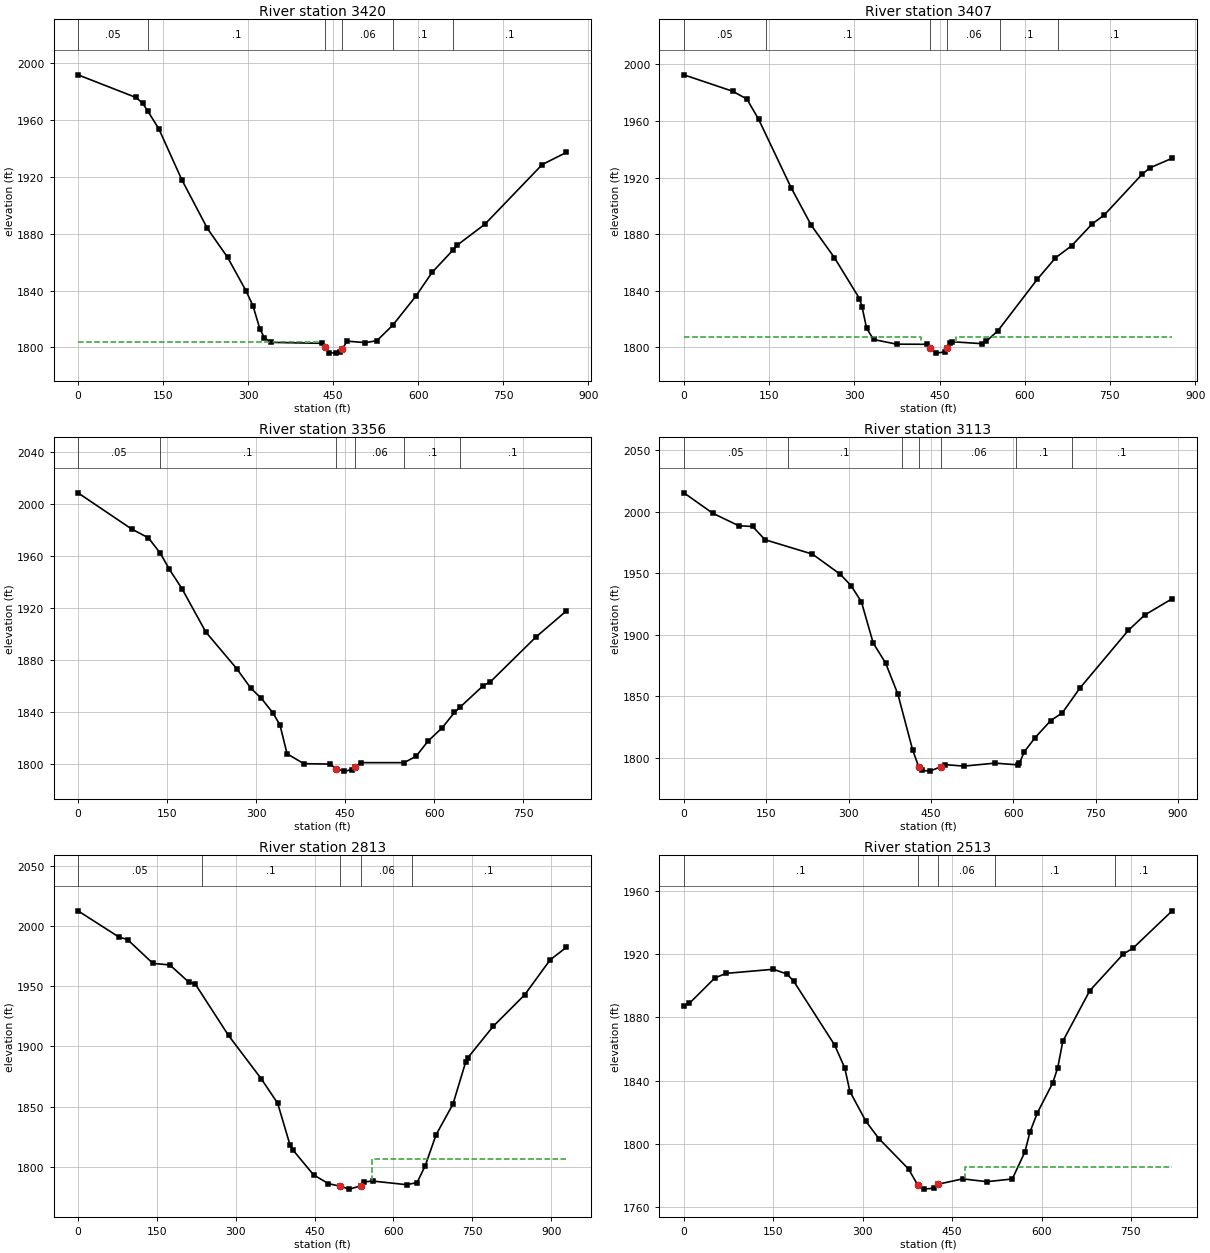
Type RM Length L Ch R = 1 ,3420    ,13.4,13.5,13.5
XS GIS Cut Line= 2
2418913.90609701671434.3252126962419764.53136098671569.739160198
#Sta/Elev= 30
       0 1991.85   102.1 1975.94   114.3  1971.8   123.5 1966.08   142.6 1953.89
   183.1 1918.05   228.3 1883.71   264.1 1863.25   296.5 1839.73   308.7 1829.27
   320.8 1813.11   328.9 1806.62   341.1 1803.49   430.2 1802.83   435.91800.089
   442.3 1796.26   454.5 1795.92   462.6 1796.82   466.3 1798.88   474.7 1804.36
   507.1 1803.31   527.4 1804.68   555.7 1815.77   596.3 1836.16   624.6 1852.71
   661.1 1868.29   669.2 1872.01   717.8 1886.66     819  1928.7   861.3 1937.17
#Mann= 6 ,-1 , 0
       0     .05       0   123.5      .1       0   435.9    .045       0
   466.3     .06       0   555.7      .1       0   661.1      .1       0
#XS Ineff= 2 , 0
          426.86  1803.9  475.14         1803.01
Permanent Ineff=
       F       F
Bank Sta=435.9,466.3
XS Rating Curve= 0 ,0
Exp/Cntr(USF)=0,0
Exp/Cntr=0.5,0.3

Type RM Length L Ch R = 1 ,3407    ,51.6,50.8,49.9
XS GIS Cut Line= 2
2418913.34657804671445.1276735362419761.38545374671585.152382412
#Sta/Elev= 30
       0 1992.66    86.3 1980.98   110.9 1975.52   131.5 1961.24   188.9  1912.7
   224.4 1886.09   264.9 1863.37     309  1834.4   313.6 1828.49   321.7 1813.28
   333.9 1805.41   374.4  1802.1   427.1 1802.02   433.1 1799.24   443.3 1795.76
   459.5 1796.58   463.6 1799.67   467.6 1802.86   471.7 1803.83   524.4 1802.46
   532.5 1804.19   552.8  1811.6   622.1 1848.01   654.1 1863.19   682.5 1871.69
     719 1887.31   739.3 1893.21   806.5 1922.27   820.4 1926.85   859.5 1933.65
#Mann= 6 ,-1 , 0
       0     .05       0  144.98      .1       0   433.1    .045       0
   463.6     .06       0  555.66      .1       0  657.83      .1       0
#XS Ineff= 2 , 0
          417.76 1807.15  479.14         1807.04
Permanent Ineff=
       F       F
Bank Sta=433.1,463.6
XS Rating Curve= 0 ,0
Exp/Cntr=0.5,0.3

Type RM Length L Ch R = 1 ,3356    ,252.8,242.9,231.7
XS GIS Cut Line= 2
2418892.83212486671513.717419517 2419709.8097775671610.102423481
#Sta/Elev= 30
       0 2008.32    90.5 1980.53   118.7 1973.76   138.9 1961.85   154.1 1949.57
   175.1 1934.88   215.4  1901.5   267.8 1873.21     291  1858.5     309  1850.6
   328.2 1839.57   340.3 1830.24   352.3 1808.06   380.5 1800.47   424.8 1800.15
   434.61796.683   448.4 1794.75   461.1 1795.72   466.41797.833   477.2 1801.26
   549.7 1801.26   569.8 1806.24   589.9 1817.82   614.1 1828.23   634.3 1839.79
   644.1 1843.97   682.6 1860.28   694.7 1863.23   771.2  1897.5   822.6  1917.6
#Mann= 6 ,-1 , 0
       0     .05       0   138.9      .1       0   434.6    .045       0
   466.4     .06       0   549.7      .1       0   644.1      .1       0
Bank Sta=434.6,466.4
XS Rating Curve= 0 ,0
Exp/Cntr(USF)=0,0
Exp/Cntr=0.3,0.1

Type RM Length L Ch R = 1 ,3113    ,290.5,300,305.2
XS GIS Cut Line= 3
 2418959.0860389671993.917964252     2419359.332      671791.223
2419759.19139083671605.905708086
#Sta/Elev= 30
       0 2015.38    52.6 1998.77   100.2 1988.55   125.2 1988.02   147.8 1977.25
   234.2 1965.53   284.8 1949.16   304.5 1939.92   323.4 1926.68   344.9 1893.16
   367.3 1877.09   389.7 1851.79   416.6 1806.42   427.6 1792.73   434.5 1789.65
     448 1789.07   468.5 1792.68   475.6 1794.38   509.7 1793.15     567 1795.57
   608.1 1794.17   611.1 1795.36   619.9 1804.71   639.7 1816.29   668.2 1830.14
   689.5 1836.55   721.3 1856.57   809.5 1903.51   839.5 1916.04   889.4 1929.26
#Mann= 7 ,-1 , 0
       0     .05       0  189.07      .1       0  397.52     .06       0
   427.6    .045       0   468.5     .06       0  604.33      .1       0
  707.48      .1       0
Bank Sta=427.6,468.5
XS Rating Curve= 0 ,0
Exp/Cntr=0.3,0.1

Type RM Length L Ch R = 1 ,2813    ,303.7,300,294.6
XS GIS Cut Line= 3
2419016.93263778672078.348045821      2419534.55      672026.849
     2419941.268      671990.409
#Sta/Elev= 30
       0 2012.42    78.2 1990.61    94.3 1988.61   142.5 1968.84   174.7 1967.56
   210.8  1953.3   222.9 1951.83   286.3 1909.08   348.5  1873.2   379.7 1852.93
   403.3 1818.18   408.8 1814.11     448  1793.5   476.2 1786.23   498.1 1784.11
   516.3 1781.66   538.7 1784.51   544.5 1787.67   560.5 1788.36   624.8 1785.35
   644.9 1787.05   660.4  1801.1     681 1826.74   713.1 1852.14   737.2  1886.9
   741.2 1890.47   789.4 1916.54   849.7 1942.88   897.9 1971.77   928.5 1982.06
#Mann= 5 ,-1 , 0
       0     .05       0  236.35      .1       0   498.1    .045       0
   538.7     .06       0  634.44      .1       0
#XS Ineff= 2 , 0
                          558.52         1806.98
Permanent Ineff=
       F       F
Bank Sta=498.1,538.7
XS Rating Curve= 0 ,0
Exp/Cntr=0.3,0.1

Type RM Length L Ch R = 1 ,2513    ,294.4,300,304.5
XS GIS Cut Line= 3
     2419202.155      672463.829     2419585.313      672319.396
     2419971.866      672183.836
#Sta/Elev= 30
       0 1887.39     9.2 1888.88    51.9 1904.91    70.7 1907.82   150.1 1910.41
   172.8 1907.44   184.4 1902.78   252.7 1862.66   269.9 1848.02   278.5 1833.16
   305.4 1814.31   327.2 1803.37   376.8 1784.21   392.4 1773.99   402.5 1771.46
   419.5 1772.07   426.7 1774.58   467.5 1777.94   508.5 1776.17   550.9 1777.87
   572.1 1794.99   580.5 1807.48     593 1819.67   618.7 1838.52   627.2 1848.25
   635.7 1864.96   680.9 1896.89   737.4 1920.16   753.1 1923.63   819.1 1947.36
#Mann= 5 ,-1 , 0
       0      .1       0   392.4    .045       0   426.7     .06       0
  521.92      .1       0  723.68      .1       0
#XS Ineff= 2 , 0
                          471.66         1785.62
Permanent Ineff=
       F       F
Bank Sta=392.4,426.7
XS Rating Curve= 0 ,0
Exp/Cntr=0.3,0.1

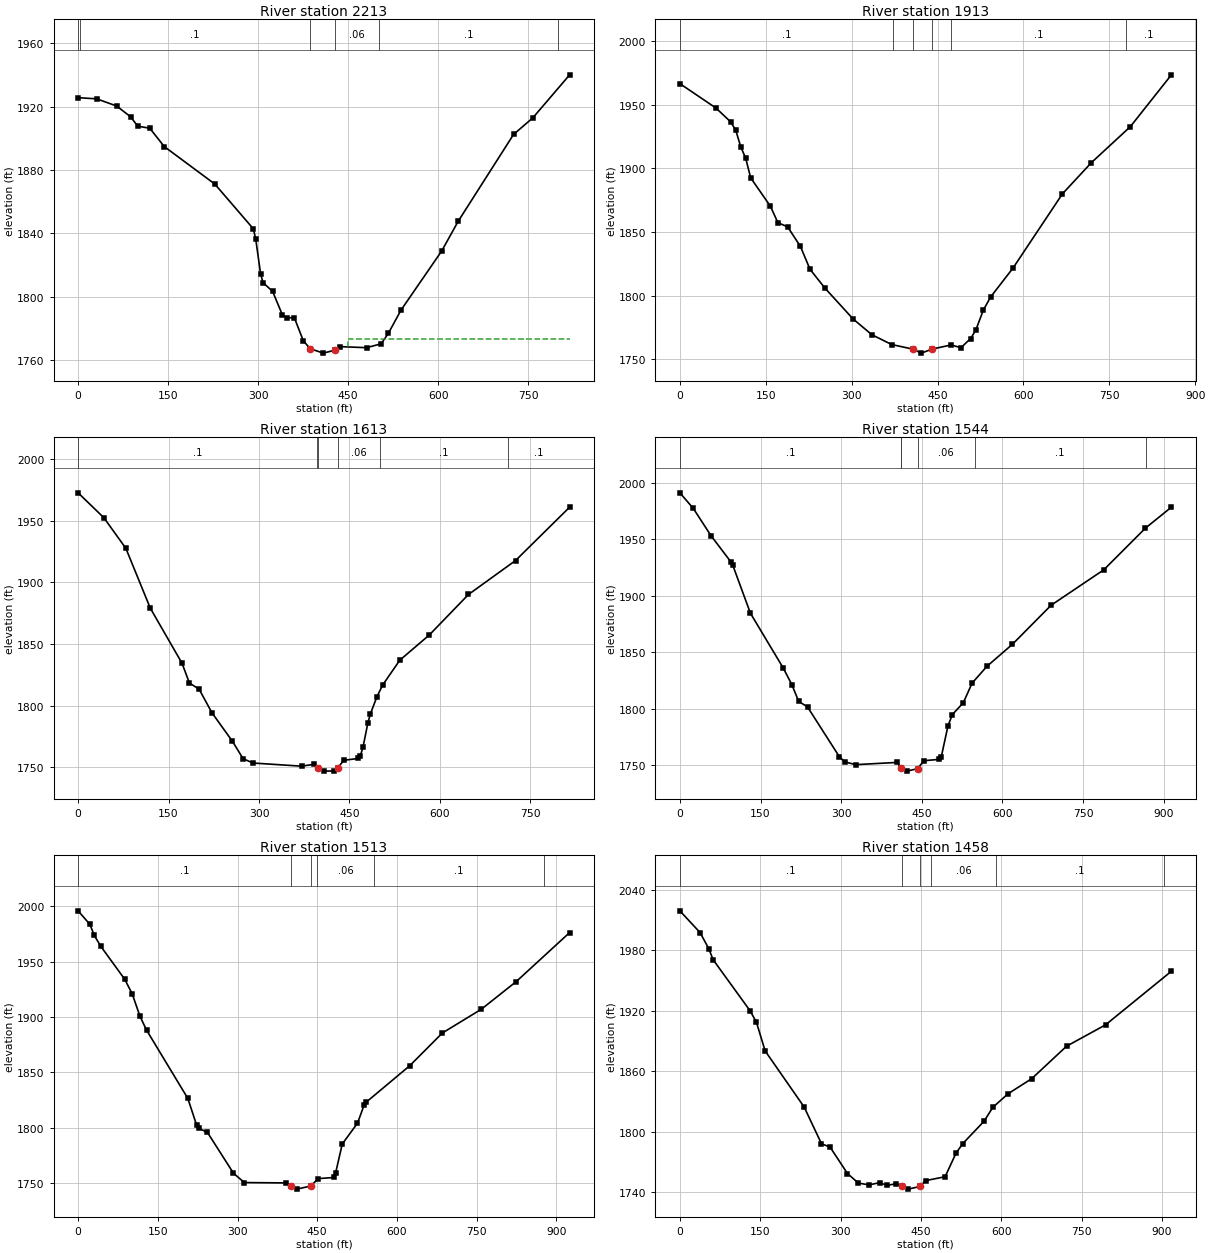
Type RM Length L Ch R = 1 ,2213    ,306.1,300,294.1
XS GIS Cut Line= 3
      2419243.79      672645.383     2419651.829      672610.817
     2420059.867       672576.25
#Sta/Elev= 30
       0 1925.73    31.1 1924.98    64.3 1920.44    87.3 1913.69    99.3 1907.73
   119.4  1906.4   143.5 1894.84   227.8 1871.11     292 1842.81     296 1836.17
     304  1814.5   308.1 1808.81   324.1 1803.26   340.2 1788.57   348.2 1786.51
   360.2 1786.72   375.1 1772.17   386.5 1767.08   408.4 1764.25   428.5 1766.19
   436.5 1768.35   480.7 1767.69   504.8 1770.14   516.8 1776.67     538 1791.46
   605.8 1828.81   633.2 1847.55   725.5 1902.48   757.7    1913     819 1940.17
#Mann= 6 ,-1 , 0
       0      .1       0    3.41      .1       0   386.5    .045       0
   428.5     .06       0  501.44      .1       0  800.25      .1       0
#XS Ineff= 2 , 0
                          449.97         1773.14
Permanent Ineff=
       F       F
Bank Sta=386.5,428.5
XS Rating Curve= 0 ,0
Exp/Cntr=0.3,0.1

Type RM Length L Ch R = 1 ,1913    ,290.2,300,308.4
XS GIS Cut Line= 3
2419348.32923474 673051.11399119     2419740.775      672890.676
2420142.81931278672725.903791064
#Sta/Elev= 30
       0 1966.51    63.1 1947.32      89 1936.36    97.7 1929.75   106.3 1916.92
     115 1907.87   123.6 1892.57   158.2 1870.16   171.1 1857.38   188.4 1853.91
   210.6 1838.59   227.3 1820.67   253.2 1805.97   302.6 1781.63   335.4 1769.26
   370.1 1761.54   406.9 1757.99   421.8 1754.82   440.7 1758.03   473.7 1761.23
   490.9 1759.08   507.8 1766.29   516.9 1772.91   529.9  1788.5   542.8 1798.95
   581.8 1821.61   668.2 1879.95   718.7 1904.43   786.9 1932.78   858.5 1973.43
#Mann= 6 ,-1 , 0
       0      .1       0  371.98     .06       0   406.9    .045       0
   440.7     .06       0  473.93      .1       0  779.81      .1       0
Bank Sta=406.9,440.7
XS Rating Curve= 0 ,0
Exp/Cntr=0.3,0.1

Type RM Length L Ch R = 1 ,1613    ,68.2,69,69.3
XS GIS Cut Line= 3
     2419344.579      673111.622     2419754.838      673177.656
2420147.67753639673250.555920933
#Sta/Elev= 30
       0 1972.66    42.7 1952.45    79.2 1927.59   119.7 1879.03   172.3 1834.36
   184.5 1818.36   200.7 1813.28   221.9 1794.18     256 1770.94   273.6  1756.9
   289.8 1753.39   370.5 1750.83   391.1 1752.33   398.1 1749.55   407.3 1746.81
   423.6 1746.91   430.2 1749.26   440.5 1755.59   464.3 1757.09     468 1759.26
   472.4 1766.23   480.5 1785.92   484.6 1793.17   495.4 1807.06   504.9 1816.58
   533.4 1836.82   582.2 1857.22   647.3 1890.15   725.4 1917.73   815.1 1961.04
#Mann= 6 ,-1 , 0
       0      .1       0  395.94     .06       0   398.1    .045       0
   430.2     .06       0  501.28      .1       0  712.29      .1       0
Bank Sta=398.1,430.2
XS Rating Curve= 0 ,0
Exp/Cntr=0.5,0.3

Type RM Length L Ch R = 1 ,1544    ,31.5,31.2,31.2
XS GIS Cut Line= 2
2419314.17269042673157.7837618132420209.91451232673340.444839222
#Sta/Elev= 30
       0 1991.22    25.1 1977.36    57.7 1953.41    94.5 1930.33    98.6 1926.91
   131.2 1884.66   192.5 1835.95   208.3  1821.4     221  1806.6   237.4 1801.72
   296.7 1757.59     307 1752.99   327.2 1750.63   404.7  1752.6   411.81747.453
   421.9 1744.88   442.2 1747.05   453.7 1754.11   482.3 1755.27   486.3 1757.72
   498.6 1784.85   506.8 1794.94   527.2 1805.46   543.5 1822.77   571.1 1837.64
   618.6  1857.2   690.5 1891.73   788.5  1923.1     866 1960.01   914.2 1978.53
#Mann= 6 ,-1 , 0
       0      .1       0  411.79      .1       0   411.8    .045       0
   442.2     .06       0  548.01      .1       0   866.6      .1       0
#XS Ineff= 2 , 0
           404.5    1750   452.4            1750
Permanent Ineff=
       F       F
Bank Sta=411.8,442.2
XS Rating Curve= 0 ,0
Exp/Cntr(USF)=0,0
Exp/Cntr=0.5,0.3

Type RM Length L Ch R = 1 ,1513    ,55.1,54.3,53.2
XS GIS Cut Line= 2
2419313.00178607673183.5436573452420216.93993838673380.255586862
#Sta/Elev= 30
       0 1995.81    22.3 1983.47    30.4  1973.6    42.7 1963.72    87.8 1933.92
   101.8 1920.76   116.4 1900.58   128.7 1888.09   206.5 1826.31   222.8  1802.5
   226.9  1799.3   243.3  1795.7   292.4 1758.72   312.9  1750.3   390.9 1749.98
     401 1747.44   411.1 1744.37   437.4 1747.09   452.1 1753.88   480.7 1754.88
   484.8  1759.3   497.1 1785.11   525.8 1803.98     538 1819.93   542.1 1822.91
     624  1855.8   685.4 1885.38   759.1 1906.98   824.6 1931.91   925.1 1976.19
#Mann= 6 ,-1 , 0
       0      .1       0     401    .045       0   437.4      .1       0
  449.73     .06       0  556.47      .1       0  876.67      .1       0
Bank Sta=401,437.4
XS Rating Curve= 0 ,0
Exp/Cntr(USF)=0,0
Exp/Cntr=0.5,0.3

Type RM Length L Ch R = 1 ,1458    ,254,248.4,241
XS GIS Cut Line= 2
2419281.51616831673258.7040070822420188.21765486673399.072019644
#Sta/Elev= 30
       0    2019    37.7 1997.44    53.9 1981.55      62 1970.58   130.8  1920.1
   142.9 1908.58   159.1 1880.15     232 1824.45   264.3 1788.13   280.5 1784.61
   312.9 1758.52   333.2 1749.03   353.4 1747.27   373.6 1749.56   385.8 1746.75
   404.3  1748.4   414.1  1745.7   426.2 1743.06   448.31745.717   458.6 1751.48
   495.1 1755.35   515.3 1778.56     528 1788.17   567.9 1810.42   584.1 1824.11
   612.4 1837.54     657 1852.66   721.7 1884.73   794.6 1905.96   917.5  1959.1
#Mann= 6 ,-1 , 0
       0      .1       0   414.1    .045       0   448.3      .1       0
  469.36     .06       0   589.8      .1       0   903.1      .1       0
Bank Sta=414.1,448.3
XS Rating Curve= 0 ,0
Exp/Cntr(USF)=0,0
Exp/Cntr=0.3,0.1

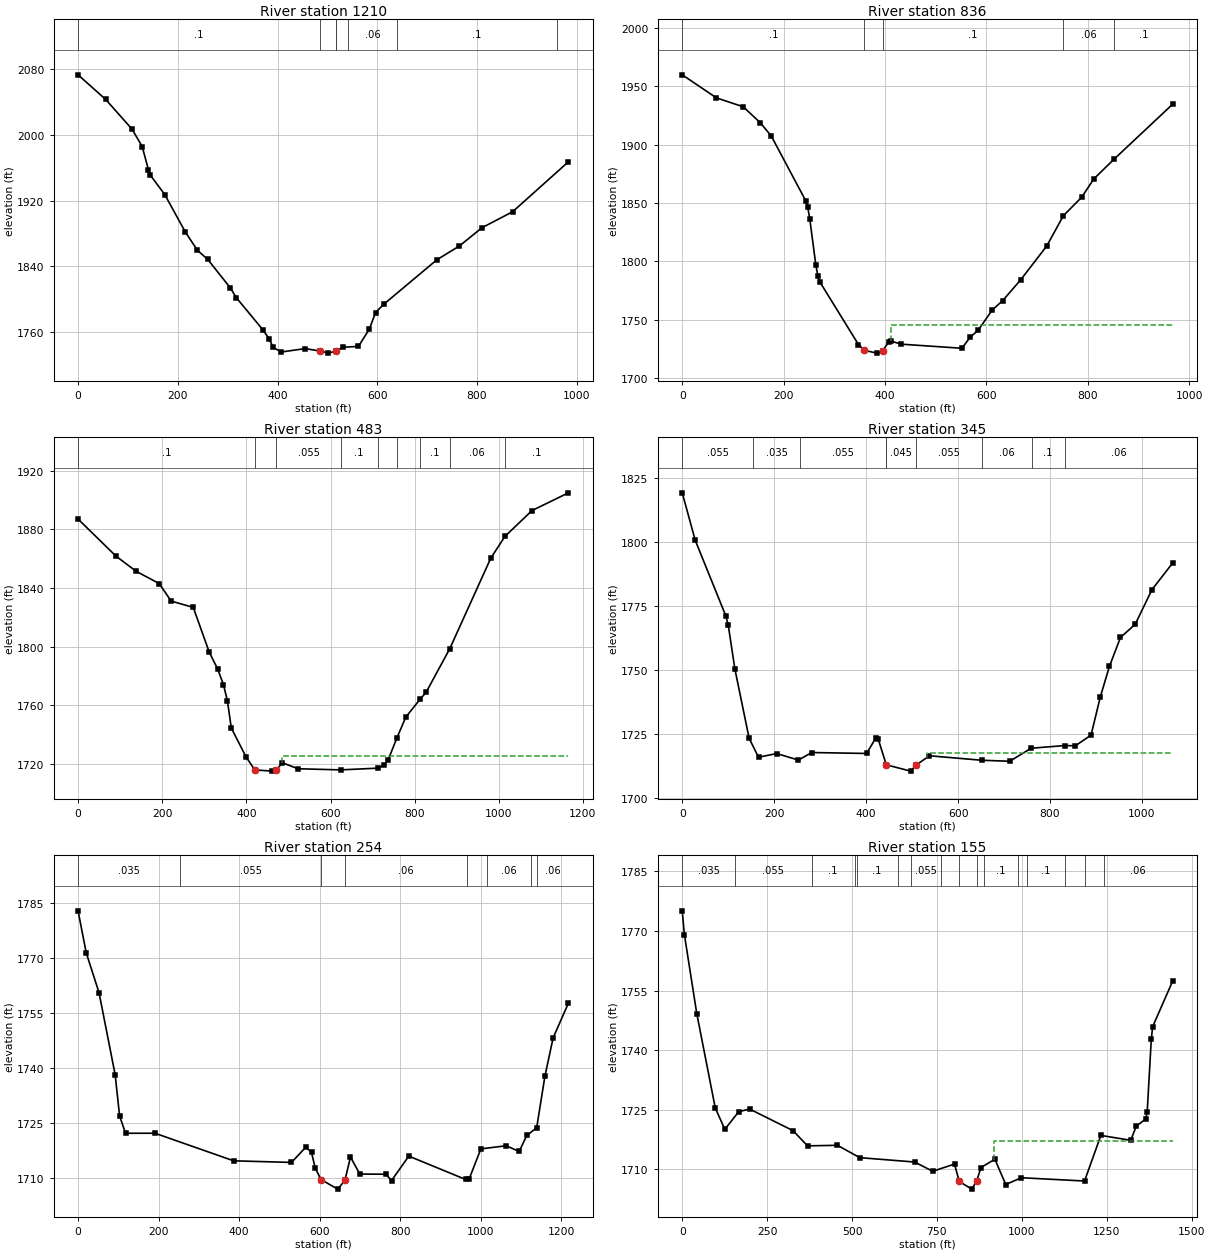
Type RM Length L Ch R = 1 ,1210    ,371,374.4,378.3
XS GIS Cut Line= 2
2419269.29652564673671.5677472332420227.71597187673451.241437754
#Sta/Elev= 30
       0 2073.06    55.2 2043.25   108.2 2007.05   128.7 1985.79     141 1957.84
   145.1 1950.94   173.9 1927.42   214.9 1882.16   239.5 1859.54   260.1 1848.59
   305.2  1814.1   317.5 1801.96   370.9 1762.77   383.2    1752   391.4 1741.46
   407.8 1735.97   455.6  1740.1     486 1737.05   502.2 1734.59   517.41737.149
   530.9 1741.68   562.4 1742.82   584.3 1763.91   596.6 1783.95     613 1793.96
   719.7 1848.15   764.9 1864.94     810 1887.06   871.6 1906.56   983.4 1967.27
#Mann= 7 ,-1 , 0
       0      .1       0     486    .045       0   517.4      .1       0
  517.42      .1       0  540.87     .06       0   640.4      .1       0
  959.58      .1       0
Bank Sta=486,517.4
XS Rating Curve= 0 ,0
Exp/Cntr(USF)=0,0
Exp/Cntr=0.3,0.1

Type RM Length L Ch R = 1 ,836     ,341,352.6,369.8
XS GIS Cut Line= 3
2419513.61756719673846.7930011412419652.76979236673911.793665026
 2420465.9387942673882.934814808
#Sta/Elev= 30
       0 1959.87    67.5  1940.1   120.4 1932.46   153.6 1918.94   175.6 1907.46
   243.6  1851.9   247.6 1846.23   251.6 1836.25   263.6 1796.62   267.6 1787.45
   271.6 1782.21   347.7 1728.56   359.21723.681   383.7 1721.23   395.21722.984
   407.6 1731.15   411.5 1731.64   431.7 1728.92   551.8 1725.39   567.8 1734.79
   583.8 1740.86   611.8 1758.34   631.9 1766.12   667.9  1784.2   719.1 1813.11
   751.9 1839.05     788 1854.92     812 1870.64   852.1 1887.62   967.3 1934.62
#Mann= 5 ,-1 , 0
       0      .1       0   359.2    .045       0   395.2      .1       0
   751.9     .06       0   852.1      .1       0
#XS Ineff= 2 , 0
       0                   411.5       0    1745
Permanent Ineff=
       F       F
Bank Sta=359.2,395.2
XS Rating Curve= 0 ,0
Exp/Cntr(USF)=0,0
Exp/Cntr=0.3,0.1

Type RM Length L Ch R = 1 ,483     ,127.6,137.6,133.5
XS GIS Cut Line= 4
2419597.33123618  673981.32209262419718.10783991674110.761483589
2420275.86600165674444.5305774112420613.19703589674417.723082151
#Sta/Elev= 30
       0 1887.11    89.8 1861.88     138 1851.42   192.9 1843.03   221.3 1831.07
   273.8 1826.74   311.7 1796.26   332.2 1784.38   345.6 1773.94   354.9 1763.05
   364.2  1744.4   399.2 1724.62   420.11715.715   462.1 1714.89   471.61715.703
   485.4 1720.64   522.7 1716.52   623.8 1715.74   712.5 1716.92   727.8 1718.97
   737.2 1722.71   757.9 1737.63   779.1 1751.84   813.4  1764.2     827 1768.62
   883.3 1798.43   980.9 1860.35  1014.5 1875.23  1078.7 1892.87  1165.4 1905.03
#Mann= 9 ,-1 , 0
       0      .1       0   420.1    .045       0   471.6    .055       0
   623.8      .1       0   712.5    .035       0   757.9      .1       0
   813.4      .1       0   883.3     .06       0  1014.5      .1       0
#XS Ineff= 2 , 0
       0                   485.4       0    1725
Permanent Ineff=
       F       F
Bank Sta=420.1,471.6
XS Rating Curve= 0 ,0
Exp/Cntr(USF)=0,0
Exp/Cntr=0.5,0.3

Type RM Length L Ch R = 1 ,345     ,97.3,91.1,96.6
XS GIS Cut Line= 4
2419601.51373783674079.6085820962419718.85880904674232.012521201
 2420284.9178653674577.0207290432420495.91551764674589.844990144
#Sta/Elev= 30
       0 1819.03    28.2 1800.57      95    1771   100.1 1767.46   114.5 1750.41
   145.5  1723.4   165.9 1716.01   205.6 1717.45   252.6 1714.91   281.7 1717.85
     401 1717.48   421.7  1723.7   426.4 1723.05   443.8 1713.11   443.91713.071
   496.7  1710.6   508.7 1712.96   537.8 1716.58   651.2 1714.84   712.2 1714.44
     759 1719.52   831.8 1720.56   855.3 1720.47   889.3 1724.64   909.2 1739.35
   929.2 1751.38   953.3  1762.7   985.3 1767.78  1021.6 1781.26  1066.6 1791.64
#Mann= 9 ,-1 , 0
       0    .055       0  154.56    .035       0  256.79    .055       0
   443.8    .055       0   443.9    .045       0   508.7    .055       0
   651.2     .06       0  760.36      .1       0   831.8     .06       0
#XS Ineff= 2 , 0
          426.12 1716.73  531.43         1717.62
Permanent Ineff=
       F       F
Bank Sta=443.9,508.7
XS Rating Curve= 0 ,0
Exp/Cntr(USF)=0,0
Exp/Cntr=0.5,0.3

Type RM Length L Ch R = 1 ,254     ,99.4,99.4,99.4
XS GIS Cut Line= 5
2419506.09262579 674067.105031042419709.67089619674320.181687127
2420044.27114286674511.550016932 2420266.4349699 674647.24157849
2420512.86311316674651.853181912
#Sta/Elev= 30
       0 1782.86    20.3  1771.4    52.1 1760.52    92.1 1738.16   103.1 1726.96
   117.8 1722.21   190.9 1722.22   386.2  1714.7   529.8 1714.26   565.6 1718.45
   579.5 1716.98   588.7 1712.72   603.1 1709.59   644.5 1706.98   662.4 1709.36
   676.2 1715.74   699.3  1711.1     764 1711.04   778.1 1709.32     821 1715.98
   962.2 1709.61   970.9 1709.78   999.8 1717.95  1062.9 1718.81  1094.9 1717.24
  1113.9 1721.62  1138.4 1723.71    1159 1737.87  1179.2 1748.21  1217.1 1757.68
#Mann= 8 ,-1 , 0
       0    .035       0  253.56    .055       0   603.1    .045       0
   662.4     .06       0  964.86      .1       0 1015.39     .06       0
 1123.52      .1       0 1139.86     .06       0
Bank Sta=603.1,662.4
XS Rating Curve= 0 ,0
Exp/Cntr(USF)=0,0
Exp/Cntr=0.5,0.3

Type RM Length L Ch R = 1 ,155     ,104.4,104.4,104.4
XS GIS Cut Line= 4
2419378.45489367674026.122940673 2419716.2994487674409.448228083
2420240.39825072674699.5144546472420573.11710867674672.246513147
#Sta/Elev= 30
       0 1775.08     6.4 1769.07    42.8 1749.23    97.2 1725.48   125.4 1720.09
   166.3 1724.52   198.3  1725.2   326.3 1719.75   368.9 1715.93     457 1716.07
   522.9 1712.96   684.5 1711.86   737.5 1709.53   801.8 1711.35   815.5    1707
   852.1 1705.04     867 1707.03   879.5 1710.48   920.6 1712.56   952.6  1706.2
   998.4 1707.91  1184.6 1707.08  1232.7 1718.56  1320.5 1717.33  1337.1  1720.9
    1365 1722.71  1369.2 1724.57  1381.2 1742.82  1385.2 1745.92  1443.8 1757.35
#Mann= 16 ,-1 , 0
       0    .035       0   154.9    .055       0  381.32      .1       0
  507.97    .055       0  513.75      .1       0  634.62     .06       0
  672.25    .055       0  761.27     .06       0   815.5    .045       0
     867    .035       0  887.93      .1       0  989.26    .035       0
 1014.15      .1       0 1127.91     .06       0  1185.8      .1       0
 1241.67     .06       0
#XS Ineff= 2 , 0
                          919.33         1717.27
Permanent Ineff=
       F       F
Bank Sta=815.5,867
XS Rating Curve= 0 ,0
Exp/Cntr(USF)=0,0
Exp/Cntr=0.3,0.1

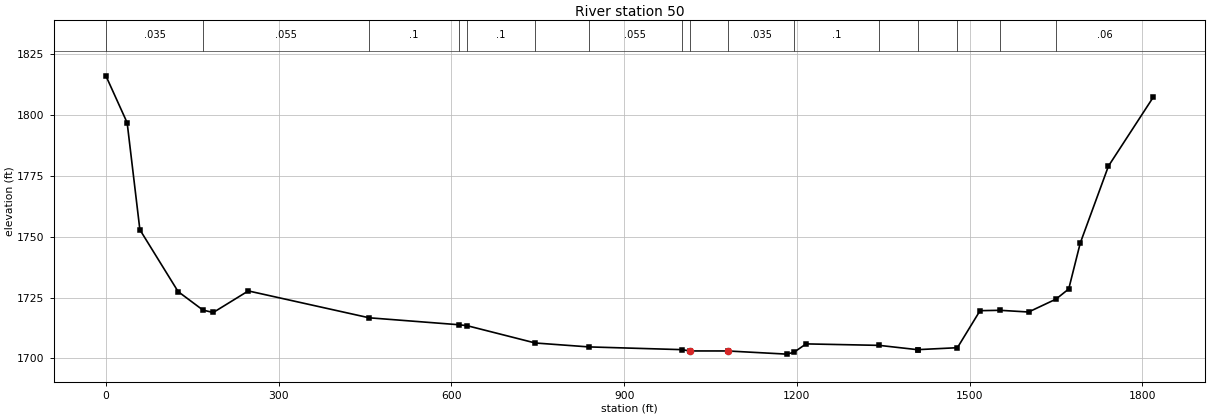
Type RM Length L Ch R = 1 ,50      ,,,
XS GIS Cut Line= 4
2419258.91562251673980.2706217172419877.92889677674626.918417147
2420384.56178493674792.7255441812420741.96825875674636.129924205
#Sta/Elev= 30
       0 1816.23    36.9 1796.95      59 1752.95   125.4 1727.51   168.6 1719.89
   186.4 1718.91   247.3 1727.78   457.2 1716.73   612.7 1713.88     627  1713.5
   745.6 1706.37   838.5 1704.76  1000.4 1703.63  1013.9  1703.1  1079.7 1703.09
  1182.2 1701.79  1194.9 1702.55  1215.9    1706  1342.9 1705.39  1409.5 1703.62
  1409.5 1703.63  1478.7 1704.43    1518 1719.66  1552.8 1719.81  1602.3 1719.11
  1649.9 1724.41    1672 1728.58    1692 1747.43    1741 1779.121818.453 1807.32
#Mann= 16 ,-1 , 0
       0    .035       0   168.6    .055       0   457.2      .1       0
   612.7    .055       0     627      .1       0   745.6     .06       0
   838.5    .055       0  1000.4     .06       0  1013.9    .045       0
  1079.7    .035       0  1194.9      .1       0  1342.9    .035       0
  1409.5      .1       0  1478.7     .06       0  1552.8      .1       0
  1649.9     .06       0
Bank Sta=1013.9,1079.7
XS Rating Curve= 0 ,0
Exp/Cntr(USF)=0,0
Exp/Cntr=0.3,0.1
LCMann Table=0

Chan Stop Cuts=-1
Use User Specified Reach Order=0
Composite Channel Slope=5

--- BRUSHRN.g02 (geometry) ---

Geom Title=Geometry_backup
Program Version=5.07

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
River Reach=BRUSHRN         ,Main
Reach XY= 30
     2405984.549      649948.396     2407095.943      650620.536
     2407466.378      651299.194     2407421.783      652099.271
      2407635.23      652936.782     2408599.107      654220.207
     2409636.051      656143.147     2410711.691       657052.96
     2411465.433      658344.444     2411971.065      660076.133
     2412003.328      662199.904     2412792.922      663743.334
     2413500.397      664121.985     2413694.581      664514.911
     2414078.373      664765.115     2414318.188      665463.431
      2414709.55      665956.774     2415162.737      666223.668
     2415673.508      666208.624     2416435.357      667032.492
      2417550.56      667694.158     2418273.511      667925.113
     2418532.627       668651.58      2418467.53      669295.547
     2418851.902      669630.778     2419360.405      670718.944
     2419310.753      671696.523     2419763.148      672926.159
     2419697.244      673405.171     2420005.424      674719.419