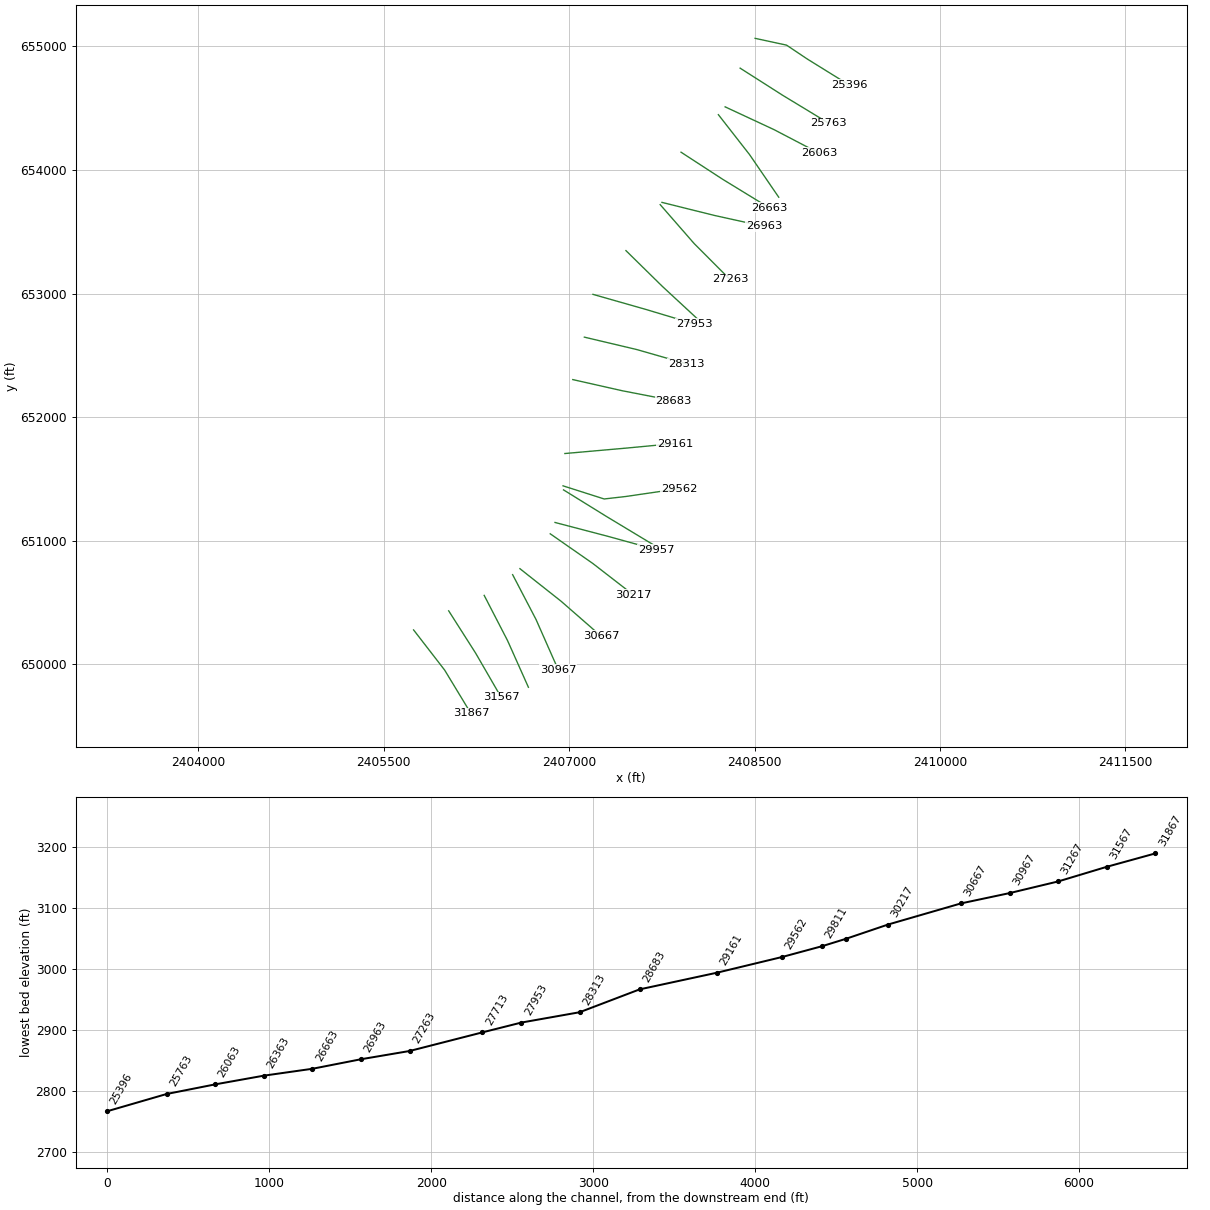
HEC-RAS study BRUSHRN.prj: BRUSHRN

--- BRUSHRN.g02 (geometry) --- (continued)

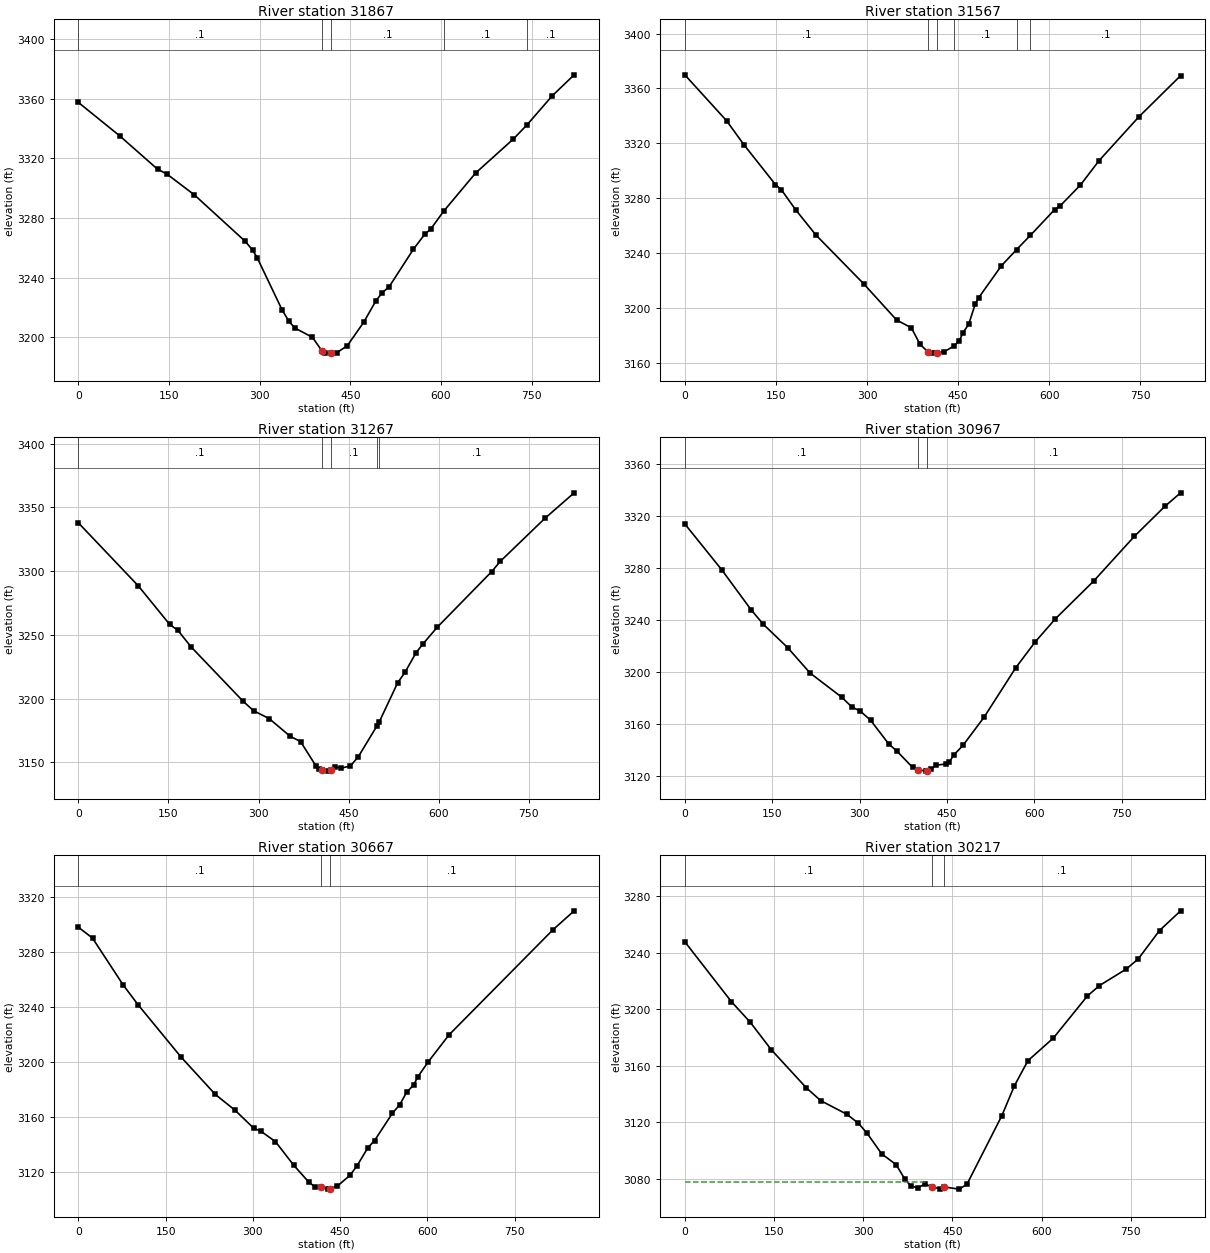
Type RM Length L Ch R = 1 ,31867   ,300,300,300
XS GIS Cut Line= 3
     2405741.817      650278.606     2405992.985       649953.76
     2406205.379      649603.412
#Sta/Elev= 30
       0 3357.66    68.9 3335.01   131.1 3312.74   146.3 3309.59   191.8 3295.58
   276.2 3264.26   288.5  3258.3   295.8 3253.38   336.9 3218.43   348.5 3210.51
   358.6 3205.98   387.3 3199.84   403.13190.675   408.2  3189.2   418.1 3189.42
     428 3189.59   444.9 3194.15   472.2 3209.98   492.6 3224.54   502.9 3229.82
   514.3 3233.84   554.3 3258.97     573 3269.03   582.9 3272.48  604.233284.449
   657.2 3310.17   719.8 3333.08  742.443342.624   783.8 3361.97   820.3 3376.17
#Mann= 5 ,-1 , 0
       0      .1       0   403.1    .045       0   418.1      .1       0
  604.23      .1       0  742.44      .1       0
Bank Sta=403.1,418.1
XS Rating Curve= 0 ,0
Exp/Cntr=0.3,0.1

Type RM Length L Ch R = 1 ,31567   ,300,300,300
XS GIS Cut Line= 3
     2406025.835      650432.847     2406244.957      650088.724
 2406449.3006501649735.289720775
#Sta/Elev= 30
       0 3369.91    68.7 3336.51    97.7 3318.79   149.3 3289.96   158.8 3286.31
   182.5 3271.63   215.7 3253.33   294.7 3217.62   348.5 3191.41   372.9 3185.67
   387.4 3173.56   400.53168.078   407.7 3167.23   415.53167.493   427.5 3168.34
  443.46 3172.57   451.7 3176.06   457.5 3181.74   467.5 3188.43     478 3202.87
   483.5 3207.42     521 3230.77  546.133242.615  568.743252.938   608.8 3271.74
     618 3274.53   651.3 3289.68   681.9  3307.4   747.3 3339.25   816.2 3369.32
#Mann= 6 ,-1 , 0
       0      .1       0   400.5    .045       0   415.5      .1       0
  443.46      .1       0  546.13      .1       0  568.74      .1       0
Bank Sta=400.5,415.5
XS Rating Curve= 0 ,0
Exp/Cntr=0.3,0.1

Type RM Length L Ch R = 1 ,31267   ,300,300,300
XS GIS Cut Line= 3
     2406312.952      650558.054      2406502.59      650190.976
     2406670.703      649814.639
#Sta/Elev= 30
       0 3337.89    99.8 3288.45   152.1  3258.2   165.6 3253.63   187.7 3240.61
   273.8 3198.21   291.6 3190.58   317.6 3184.43   352.5 3170.57   369.9 3166.41
   395.3 3147.44   399.8 3144.89   405.73144.114   416.4 3143.23   420.73144.465
   426.4 3146.69   437.6 3145.63   452.8 3147.25   465.8 3154.36  497.383178.918
  500.823181.784   531.5 3212.45   543.6 3220.62   562.2 3236.06   573.8 3243.03
   597.3 3255.97   688.2 3299.71   702.4  3307.7   776.7 3341.41   825.3 3361.38
#Mann= 5 ,-1 , 0
       0      .1       0   405.7    .045       0   420.7      .1       0
  497.38      .1       0  500.82      .1       0
Bank Sta=405.7,420.7
XS Rating Curve= 0 ,0
Exp/Cntr=0.3,0.1

Type RM Length L Ch R = 1 ,30967   ,300,300,300
XS GIS Cut Line= 3
     2406543.131      650725.508     2406732.101      650363.471
     2406911.253      649958.261
#Sta/Elev= 30
       0  3313.7    63.9 3278.22   114.3 3247.58   135.1  3236.6   176.6 3218.84
   215.1 3199.34   269.2 3180.89   287.2 3173.19   300.8 3170.32   318.9 3163.21
   350.4 3144.84   363.9 3139.62     391 3127.05   400.93125.221   413.4 3124.11
   415.93124.175     423 3125.48   430.9 3128.66   448.4 3129.55   454.5 3131.27
   461.5 3136.27   477.6 3143.81     514 3165.54   568.5 3203.52   601.9 3223.34
   636.4 3240.95     702 3269.83     772 3304.18   824.5 3327.23   851.4 3337.54
#Mann= 3 ,-1 , 0
       0      .1       0   400.9    .045       0   415.9      .1       0
Bank Sta=400.9,415.9
XS Rating Curve= 0 ,0
Exp/Cntr=0.3,0.1

Type RM Length L Ch R = 1 ,30667   ,450,450,450
XS GIS Cut Line= 3
     2406601.975         650774.     2406935.152      650510.628
     2407257.298      650229.531
#Sta/Elev= 30
       0 3297.88    24.4 3289.92    76.8    3256   102.4 3241.56   176.5 3203.37
   235.5 3176.11   269.5 3164.58   301.7 3151.43   313.2 3149.53   338.8 3141.77
   370.1 3124.65   395.7  3112.5   407.1 3108.65   417.23108.389   429.5  3107.2
   432.23107.594   445.4 3109.51   466.9 3117.25   479.1 3124.25   497.9  3137.5
   509.1 3142.53   539.9 3162.51   552.1 3168.46   564.2 3177.61   576.4 3183.12
   583.4 3188.84   600.7 3199.48   637.2 3219.53   815.5  3295.9   852.2 3309.79
#Mann= 3 ,-1 , 0
       0      .1       0   417.2    .045       0   432.2      .1       0
Bank Sta=417.2,432.2
XS Rating Curve= 0 ,0
Exp/Cntr=0.3,0.1

Type RM Length L Ch R = 1 ,30217   ,259.8,259.8,259.8
XS GIS Cut Line= 3
     2406847.193      651056.203     2407191.037      650816.667
     2407518.822      650562.949
#Sta/Elev= 30
       0 3247.83    78.2 3205.45   109.8 3190.92   145.7 3171.19   204.2 3144.38
   228.6 3135.24   272.5  3125.6   291.9 3119.24   306.6  3112.1     331 3097.57
   355.3 3089.92   369.9 3079.72   379.7 3074.93   391.4 3073.43   404.1 3076.27
   415.2 3074.11   428.8 3072.92     435 3074.18   461.2 3072.58   474.3 3075.97
     533 3124.57   554.1 3145.75   576.9 3163.56   619.7 3179.62   676.8 3209.38
   696.9 3216.71   742.2 3228.48   762.3 3235.62   798.1 3255.76   833.6 3269.73
#Mann= 3 , 0 , 0
       0      .1       0   415.2    .045       0     435      .1       0
#XS Ineff= 2 , 0
          403.42 3077.88
Permanent Ineff=
       F       F
Bank Sta=415.2,435
XS Rating Curve= 0 ,0
Exp/Cntr=0.3,0.1

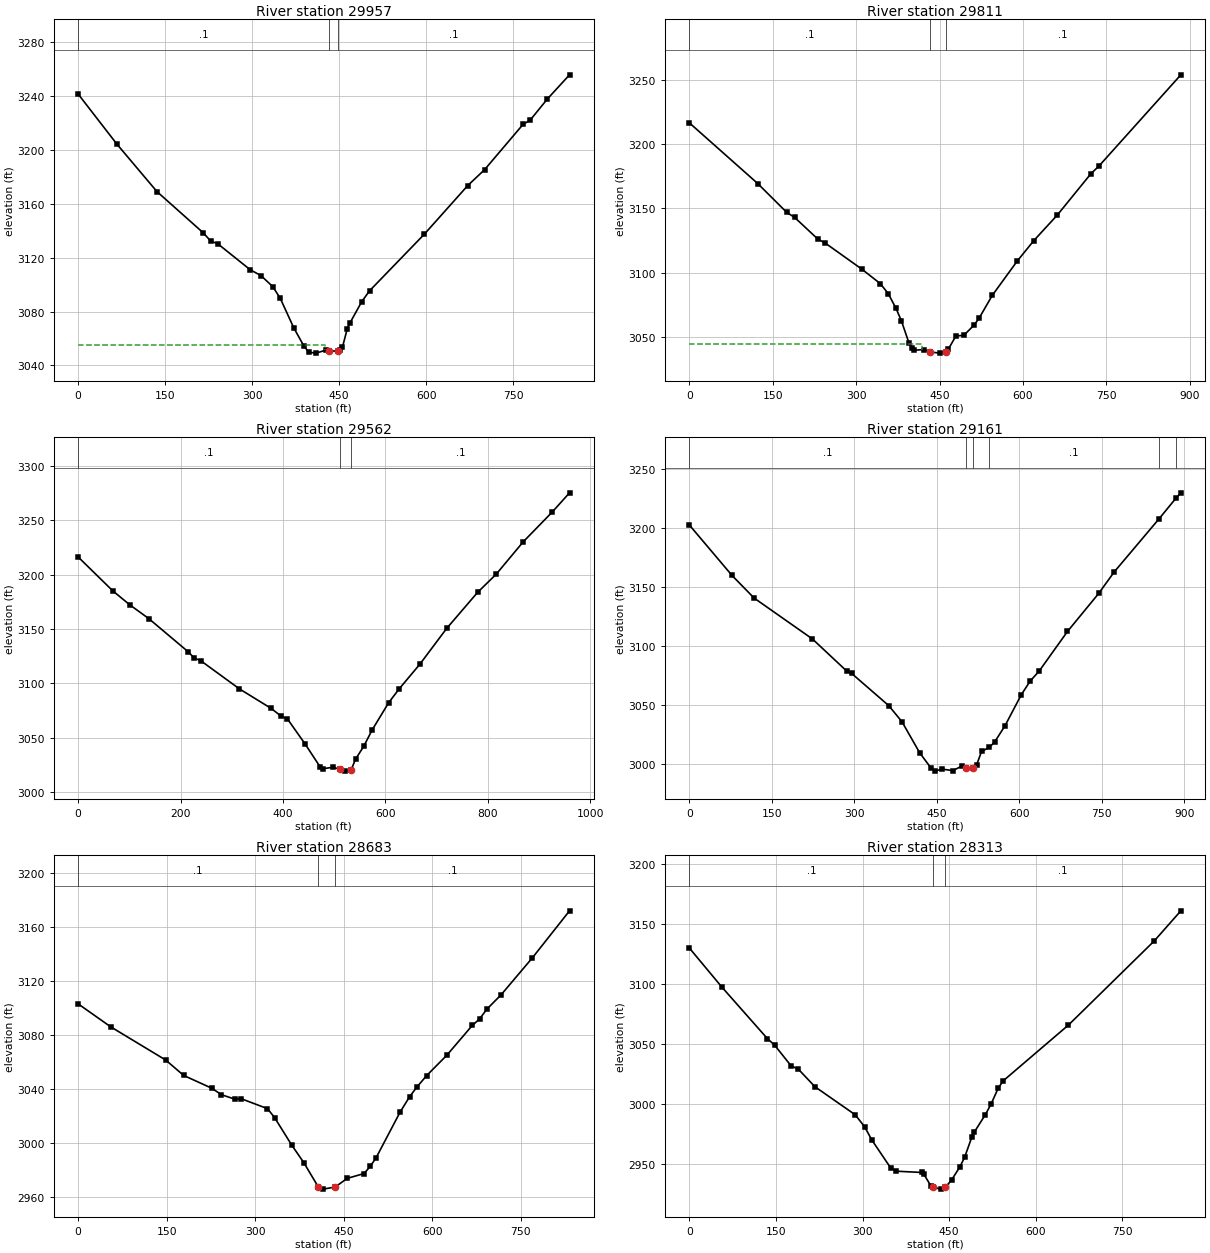
Type RM Length L Ch R = 1 ,29957   ,146.8,146.8,146.8
XS GIS Cut Line= 3
2406885.83325563651147.908394713 2407314.4397605651035.585365469
     2407704.038      650928.131
#Sta/Elev= 30
       0  3241.6    67.1 3204.25   135.9 3169.15     216 3138.42   228.4 3132.48
   240.8 3130.38   296.8 3111.07   315.2 3106.77   335.4 3098.64   348.3 3090.06
   371.8 3067.95   389.6 3054.19   397.9 3049.83   410.3 3049.18   426.9 3051.41
   432.93050.861   447.93050.655   451.7  3051.2   455.8 3053.68   464.1  3067.4
   468.3 3071.29     489 3087.42   502.4 3095.44   596.8 3137.45   671.6 3173.55
   700.7 3185.39     767 3218.99   779.5 3222.26   809.2    3238   847.2 3255.84
#Mann= 3 ,-1 , 0
       0      .1       0   432.9    .045       0   447.9      .1       0
#XS Ineff= 2 , 0
          425.61 3055.54
Permanent Ineff=
       F       F
Bank Sta=432.9,447.9
XS Rating Curve= 0 ,0
Exp/Cntr=0.3,0.1

Type RM Length L Ch R = 1 ,29811   ,248.8,248.8,248.8
XS GIS Cut Line= 3
2406954.65337414651411.4886297682407305.72011655651194.219674827
2407709.21511655650950.919674827
#Sta/Elev= 30
       0 3216.79   122.8  3169.5   174.8 3147.05   189.4 3142.97   230.6 3126.25
   244.4 3122.97   310.6  3102.5   343.4 3091.33   357.6 3083.57   371.7 3071.98
   381.2 3062.46   395.2 3044.64     400 3040.91   404.7 3039.39   421.9 3039.85
   433.5 3037.92   451.4  3037.1   460.8 3038.17   465.8 3040.23   479.4 3050.53
   493.5 3050.95   512.3  3059.1   521.5 3064.68   544.8 3082.19   589.7 3108.99
   619.6 3124.97   661.6 3144.79   722.3 3177.18   736.6 3183.09     884 3254.33
#Mann= 3 ,-1 , 0
       0      .1       0   433.5    .045       0   460.8      .1       0
#XS Ineff= 2 , 0
          418.86 3044.54
Permanent Ineff=
       F       F
Bank Sta=433.5,460.8
XS Rating Curve= 0 ,0
Exp/Cntr=0.3,0.1

Type RM Length L Ch R = 1 ,29562   ,400.8,400.8,400.8
XS GIS Cut Line= 4
2406950.69814299651444.2145847092407283.52793476 651337.90154762
2407458.48739471651357.9804436762407888.30104506651420.806210573
#Sta/Elev= 30
       0  3216.3    67.9 3185.02   100.8 3172.28   137.9 3159.62   214.7 3129.17
   226.8  3123.3   239.4 3120.87     315 3094.94   376.8 3077.02   396.9 3069.69
     409 3067.18   443.5 3044.13   473.4 3022.66   477.4 3021.37   497.7 3022.79
   511.1 3021.01   521.7 3019.23   533.6 3020.66   541.9 3030.23   557.9 3042.04
   574.3 3057.08   606.6 3082.16   626.8 3094.72   667.3 3117.44   719.8 3150.46
   780.4 3183.72   816.8 3200.49   869.4 3230.17     926 3257.54   959.9 3275.28
#Mann= 3 ,-1 , 0
       0      .1       0   511.1    .045       0   533.6      .1       0
Bank Sta=511.1,533.6
XS Rating Curve= 0 ,0
Exp/Cntr=0.3,0.1

Type RM Length L Ch R = 1 ,29161   ,478.1,478.1,478.1
XS GIS Cut Line= 3
 2406965.6992274651705.5806889012407459.24372268651749.175288648
2407855.47220097651786.671435907
#Sta/Elev= 30
       0 3202.33    77.3 3159.68   117.5 3140.45   223.6 3105.72     286 3078.45
   294.8 3076.52   362.5 3049.09   386.5 3035.43   418.7 3009.09   438.7 2996.52
   446.8 2993.56   458.8 2995.28   478.9 2994.01     495 2997.76     503 2996.14
   515.1 2995.96   522.3 2998.95   531.1 3010.26  545.473013.752   555.3 3018.55
   573.7    3032   603.4 3058.38   619.5 3069.97   635.6 3078.27   687.4  3112.1
   744.1 3144.33   772.2 3162.51  853.393207.407  885.083225.436   893.5 3229.72
#Mann= 6 ,-1 , 0
       0      .1       0     503    .045       0   515.1      .1       0
  545.47      .1       0  853.39      .1       0  885.08      .1       0
Bank Sta=503,515.1
XS Rating Curve= 0 ,0
Exp/Cntr=0.3,0.1

Type RM Length L Ch R = 1 ,28683   ,370.1,370.1,370.1
XS GIS Cut Line= 3
2407029.74590434 652303.668399622407429.05290434 652213.69139962
2407844.45252171652132.894365008
#Sta/Elev= 30
       0 3103.14      55 3086.22   148.5 3061.56   178.8 3050.22   226.5 3040.75
   242.9 3035.95   265.8 3032.66   275.9 3033.07   320.8 3025.66   332.8  3019.1
   361.8 2998.77   382.4 2985.72     407 2967.71   415.1 2966.17   435.5 2967.74
   455.9 2974.12   484.4 2977.69     495 2983.04   504.8 2989.34   545.5 3023.13
   561.8 3034.63     574 3041.65   590.3 3050.03   624.7 3065.18   667.8  3087.2
     680 3091.91   692.2 3099.07   716.8 3109.93   769.6 3137.17   832.5  3171.9
#Mann= 3 ,-1 , 0
       0      .1       0     407    .045       0   435.5      .1       0
Bank Sta=407,435.5
XS Rating Curve= 0 ,0
Exp/Cntr=0.3,0.1

Type RM Length L Ch R = 1 ,28313   ,360.1,360.1,360.1
XS GIS Cut Line= 3
     2407123.185      652647.138     2407545.082      652547.343
2407946.97946199652432.359875742
#Sta/Elev= 30
       0 3129.99    56.3  3097.4   135.2 3054.37   147.5 3049.02   176.3 3031.58
   188.6 3028.96   217.4 3014.25   287.3  2990.8   303.7  2980.7     316 2969.81
   348.9 2946.29   358.8 2943.65   402.4 2942.62   406.5 2940.95   418.1 2931.63
   422.9  2930.2   435.2 2928.69   443.6 2930.23   454.7 2936.64   468.6 2947.21
   476.9  2955.3   489.4 2972.18   493.5 2976.19   512.9 2990.96   522.6 2999.63
   535.1 3012.98   543.4    3019   656.8 3065.73   805.6 3136.04   851.6 3161.14
#Mann= 3 ,-1 , 0
       0      .1       0   422.9    .045       0   443.6      .1       0
Bank Sta=422.9,443.6
XS Rating Curve= 0 ,0
Exp/Cntr=0.3,0.1

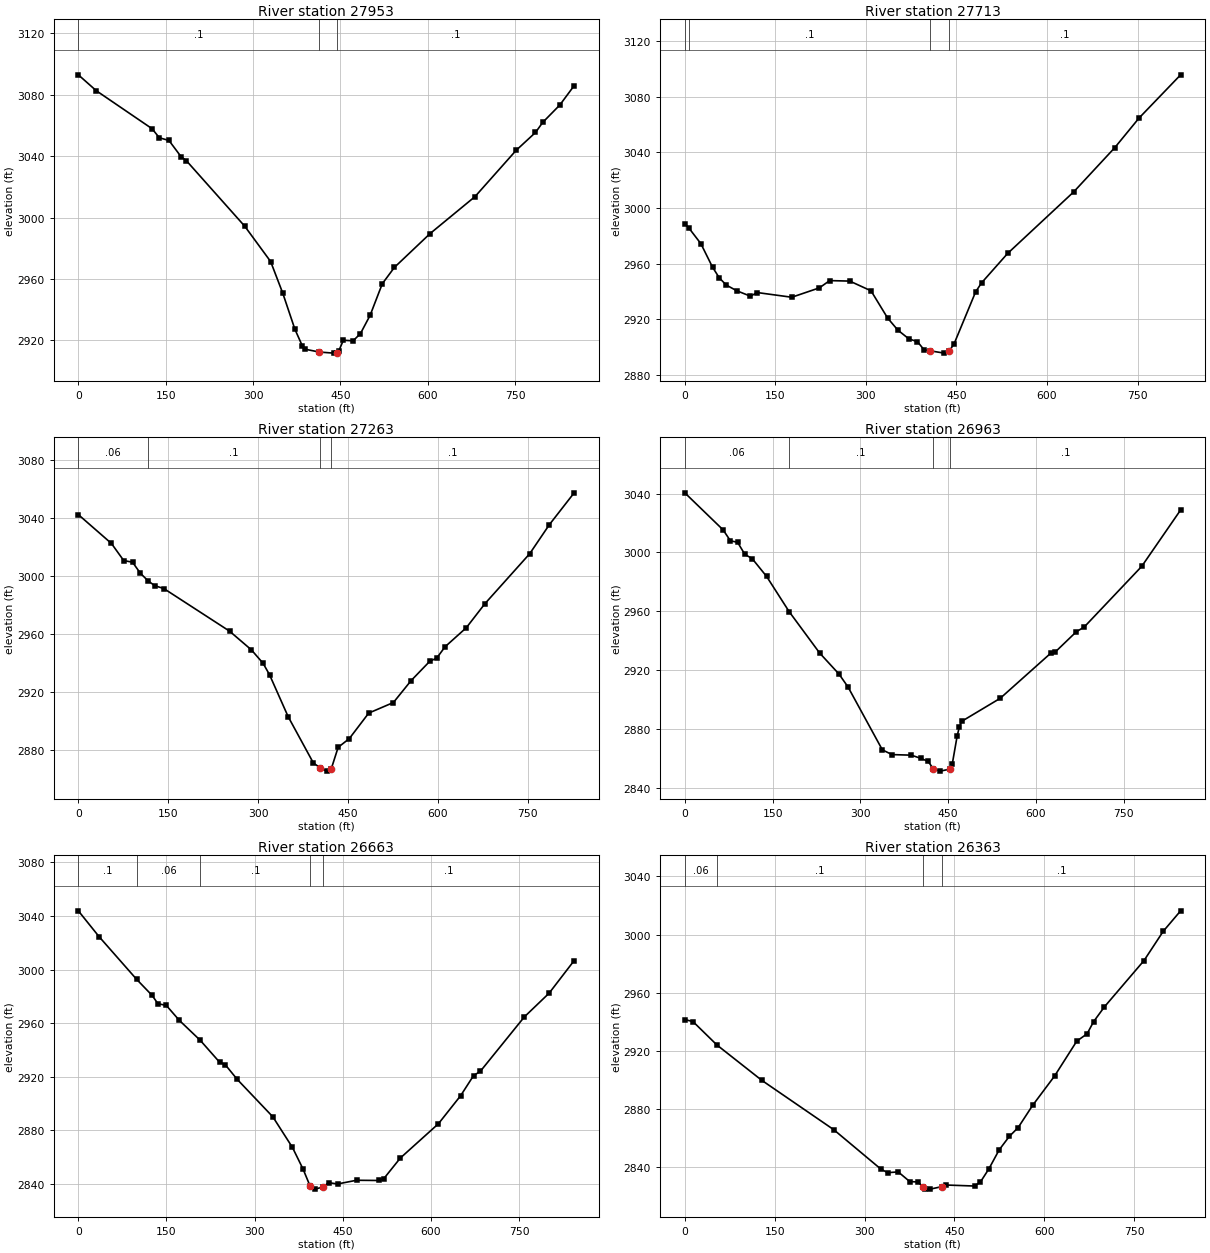
Type RM Length L Ch R = 1 ,27953   ,239.9,239.9,239.9
XS GIS Cut Line= 3
2407192.98055115652993.267850781 2407621.1223304652871.255312776
 2408010.3493304652754.397312776
#Sta/Elev= 30
       0  3092.9    30.9 3082.54   126.6 3057.83   139.1 3051.95   155.7 3050.15
   176.5 3039.59   185.3 3037.11     286 2994.26   330.3 2971.35   351.2 2950.68
     372 2927.22   384.5 2916.65   388.6 2914.35   413.92912.431   438.6 2911.73
   443.6  2911.9   446.9 2912.81   455.2 2920.12   471.9 2919.74   484.5 2924.41
   501.2 2936.39   522.1 2956.93   542.9 2967.55   604.2 2989.57   681.3 3013.62
   751.9 3043.72   785.2 3055.38   797.7 3061.97   826.9 3073.22   851.6 3085.85
#Mann= 3 ,-1 , 0
       0      .1       0   413.9    .045       0   443.6      .1       0
Bank Sta=413.9,443.6
XS Rating Curve= 0 ,0
Exp/Cntr=0.3,0.1

Type RM Length L Ch R = 1 ,27713   ,450,450,450
XS GIS Cut Line= 3
     2407459.794      653347.064      2407754.03      653058.045
      2408054.11      652780.164
#Sta/Elev= 30
       0 2988.78    6.91 2985.54    26.6 2974.41    45.9 2957.51    57.3  2949.7
    68.7 2944.63    85.9 2940.56   108.7 2936.62   120.1 2939.23   177.2 2935.86
   222.9  2942.6     240 2947.83   273.3 2947.47   308.5 2940.48     336 2920.91
   352.9 2912.26   371.3 2905.89   385.4 2903.95   396.6 2897.93   405.5  2897.4
   429.8 2895.68   437.8 2896.91   446.3 2902.57   481.8 2939.73   491.6 2946.19
   534.8 2967.35   644.4 3011.67   712.4 3043.46   752.6 3064.74   821.4 3095.78
#Mann= 4 ,-1 , 0
       0     .06       0    6.91      .1       0   405.5    .045       0
   437.8      .1       0
Bank Sta=405.5,437.8
XS Rating Curve= 0 ,0
Exp/Cntr=0.3,0.1

Type RM Length L Ch R = 1 ,27263   ,300,300,300
XS GIS Cut Line= 3
      2407736.95      653718.989     2408010.915       653405.06
     2408300.655      653114.287
#Sta/Elev= 30
       0 3042.07    55.2 3022.17    75.7 3010.37    90.4 3009.23   103.4 3001.66
  116.332996.374   127.5 2993.01   142.6 2991.06   252.2 2961.68   288.7 2948.75
   308.1 2939.54   318.9 2931.64     350 2902.68   392.1 2870.71   403.6 2867.36
   414.2  2865.1   422.1 2866.89   433.4 2881.53     452 2887.53   484.4 2905.13
   525.6 2912.44   555.2 2927.59   586.4 2940.94   597.8 2943.03   611.7 2950.86
   647.2 2964.03   678.3 2980.64   752.9 3015.06   785.8 3035.16   827.1 3057.09
#Mann= 4 ,-1 , 0
       0     .06       0  116.33      .1       0   403.6    .045       0
   422.1      .1       0
Bank Sta=403.6,422.1
XS Rating Curve= 0 ,0
Exp/Cntr=0.3,0.1

Type RM Length L Ch R = 1 ,26963   ,300,300,300
XS GIS Cut Line= 3
2407751.16973342653737.222124258     2408177.123      653631.343
     2408575.732      653543.408
#Sta/Elev= 30
       0 3040.49    65.5 3015.32    77.9 3007.94    90.2 3006.91   102.6  2998.7
     115 2995.88   139.7 2983.77  178.342959.805   230.4 2931.74   263.4 2917.49
   278.9 2908.67   337.5 2866.03     354  2862.8     387 2862.42   403.5 2860.21
   415.9 2858.14   424.42853.248   436.5 2851.58   452.9 2852.95     457 2856.47
   465.2 2875.18   469.2 2881.83   473.3 2885.43   538.9 2901.02   624.9 2931.52
   633.1 2932.53   668.9 2946.19   682.3 2949.36   780.6 2990.56   847.1 3028.86
#Mann= 4 ,-1 , 0
       0     .06       0  178.34      .1       0   424.4    .045       0
   452.9      .1       0
Bank Sta=424.4,452.9
XS Rating Curve= 0 ,0
Exp/Cntr=0.3,0.1

Type RM Length L Ch R = 1 ,26663   ,300,300,300
XS GIS Cut Line= 3
     2407905.247      654143.353     2408245.551      653922.121
2408619.12718609653693.645163563
#Sta/Elev= 30
       0 3043.89    35.2 3024.64   99.082992.759   125.6 2980.68   135.4 2974.51
   149.7 2973.21     172 2961.99  207.642947.064   240.3 2930.83   250.1 2928.88
   270.3    2918     331 2889.98   364.4 2867.08   382.5 2850.87   394.6 2838.03
   403.3 2835.95   416.7 2837.64     426  2840.8   441.1  2839.8   473.4 2842.57
   511.8  2842.4   519.7  2843.7     548 2859.19   612.8  2884.8   650.6 2905.76
   672.7 2920.85   683.9 2923.85     759 2964.61   801.2 2982.37   843.8 3006.71
#Mann= 5 ,-1 , 0
       0      .1       0   99.08     .06       0  207.64      .1       0
   394.6    .045       0   416.7      .1       0
Bank Sta=394.6,416.7
XS Rating Curve= 0 ,0
Exp/Cntr=0.3,0.1

Type RM Length L Ch R = 1 ,26363   ,300,300,300
XS GIS Cut Line= 3
     2408207.567      654446.838     2408460.817      654122.323
2408695.81685211653779.032521712
#Sta/Elev= 30
       0 2941.42    13.6 2940.07   53.752923.876   128.7 2899.53   248.6  2865.6
   327.1 2838.51   338.5 2835.98   356.3 2836.49   375.4 2829.89   389.8 2829.52
   397.2 2826.23   400.8 2825.04   409.8 2824.64   429.2 2826.38   435.6 2827.48
   483.7 2826.77   493.4 2829.49   507.6 2838.59   524.8 2851.69   541.8    2861
   556.4 2866.99   580.6 2882.31   617.2  2902.5   654.3 2926.55   671.6 2931.65
   682.4 2939.97   700.4 2950.14   766.6 2982.09   798.7 3002.25   827.7 3016.33
#Mann= 4 ,-1 , 0
       0     .06       0   53.75      .1       0   397.2    .045       0
   429.2      .1       0
Bank Sta=397.2,429.2
XS Rating Curve= 0 ,0
Exp/Cntr=0.3,0.1

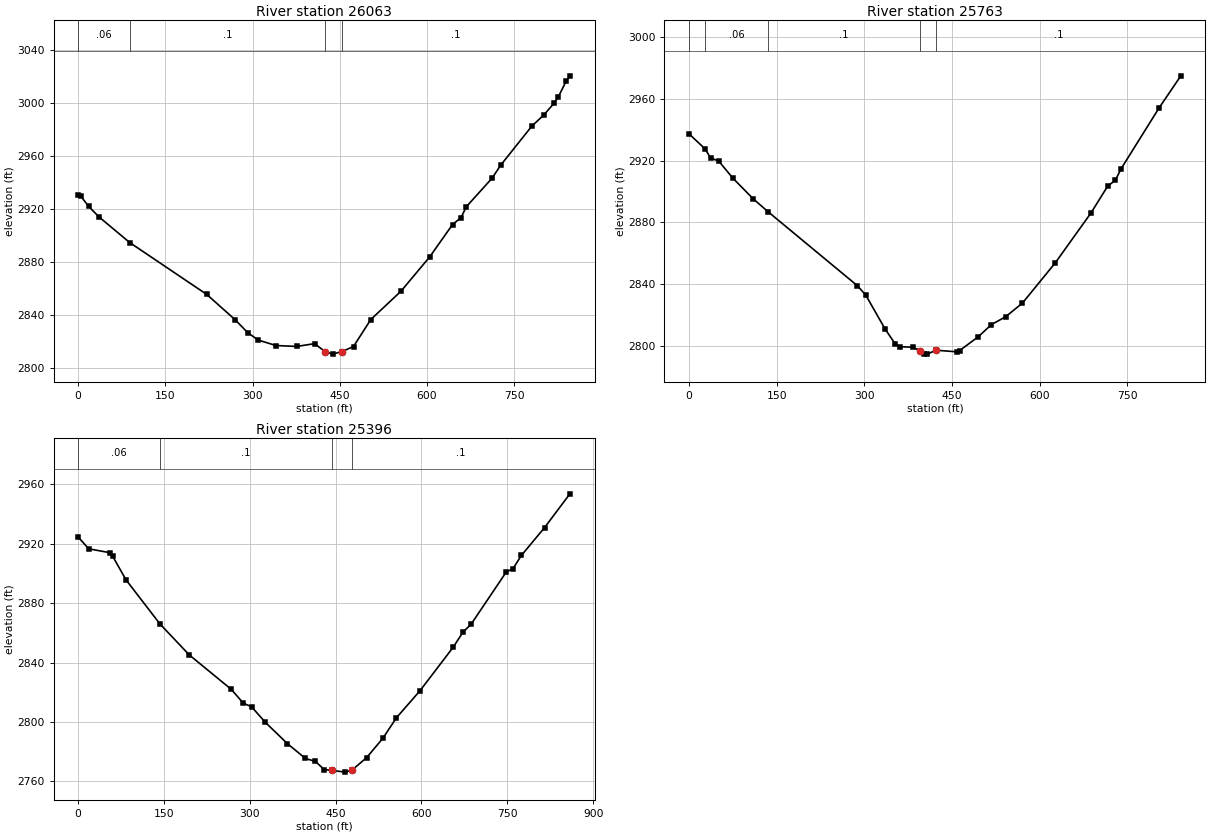
Type RM Length L Ch R = 1 ,26063   ,300,300,300
XS GIS Cut Line= 3
      2408262.18      654510.125      2408656.35      654326.612
2409020.67384055654136.385598243
#Sta/Elev= 30
       0 2930.77       5 2929.51    17.9 2922.03    35.9 2914.02   88.832894.624
   221.2 2855.47   269.8 2836.44   291.8 2826.55   309.9 2820.96   340.4 2816.86
   376.2 2816.18   406.6 2818.29   424.7 2812.29   437.5 2810.37   454.2 2812.35
   473.6 2816.13   503.3 2836.49   555.2 2857.88   604.5 2883.74   643.9 2908.25
   658.6 2913.55   667.6 2921.69   712.1 2943.37   726.9  2953.2   780.4 2982.67
     801 2991.07   818.8 3000.06   825.6 3004.42   839.1 3016.47   845.8 3020.61
#Mann= 4 ,-1 , 0
       0     .06       0   88.83      .1       0   424.7    .045       0
   454.2      .1       0
Bank Sta=424.7,454.2
XS Rating Curve= 0 ,0
Exp/Cntr=0.3,0.1

Type RM Length L Ch R = 1 ,25763   ,366.8,366.8,366.8
XS GIS Cut Line= 3
2408383.71958276654823.080699309     2408728.255      654603.394
     2409098.427      654378.785
#Sta/Elev= 30
       0 2937.49   27.312927.764    36.8 2921.96      51 2919.73    74.7 2908.87
   109.5 2895.44  135.452886.881   288.2 2838.92   302.5 2832.84   335.7 2810.74
   352.8 2801.23   361.5 2799.41   383.1 2799.03   394.7  2796.8     402 2794.73
   407.9 2794.58   422.4 2797.13   458.3 2796.08     463 2796.87   495.2 2805.94
   517.5 2813.74   541.8 2818.83   570.6 2827.72   626.8 2853.83   687.6 2886.03
   716.5 2903.61   729.7 2907.42     739  2914.6   804.5 2954.39   841.6 2975.13
#Mann= 5 ,-1 , 0
       0      .1       0   27.31     .06       0  135.45      .1       0
   394.7    .045       0   422.4      .1       0
Bank Sta=394.7,422.4
XS Rating Curve= 0 ,0
Exp/Cntr=0.3,0.1

Type RM Length L Ch R = 1 ,25396   ,233.2,233.2,233.2
XS GIS Cut Line= 4
2408504.74976891655064.4320246982408759.02968059655009.434843707
2408926.96305559654896.944724207 2409264.5059853654687.737575343
#Sta/Elev= 30
       0  2924.6    18.4 2916.61    55.2 2914.03    60.2 2911.73    83.7  2895.7
  143.07 2865.98   194.4 2845.12   267.6 2822.01   288.7 2812.69   303.1 2810.28
   327.2 2799.79   365.7 2785.47   397.3 2775.47   414.6 2773.48     430 2768.04
   443.4 2767.48   466.5 2766.29  478.64 2767.66   504.2 2776.08   532.6 2789.11
   556.2 2802.86   597.3 2821.03   655.4 2850.35   672.8 2860.67   686.4 2865.67
   748.3 2901.07     760 2903.27   774.5 2912.12   815.2 2930.93   859.4 2953.62
#Mann= 4 ,-1 , 0
       0     .06       0  143.07      .1       0   443.4    .045       0
  478.64      .1       0
Bank Sta=443.4,478.64
XS Rating Curve= 0 ,0
Exp/Cntr=0.3,0.1