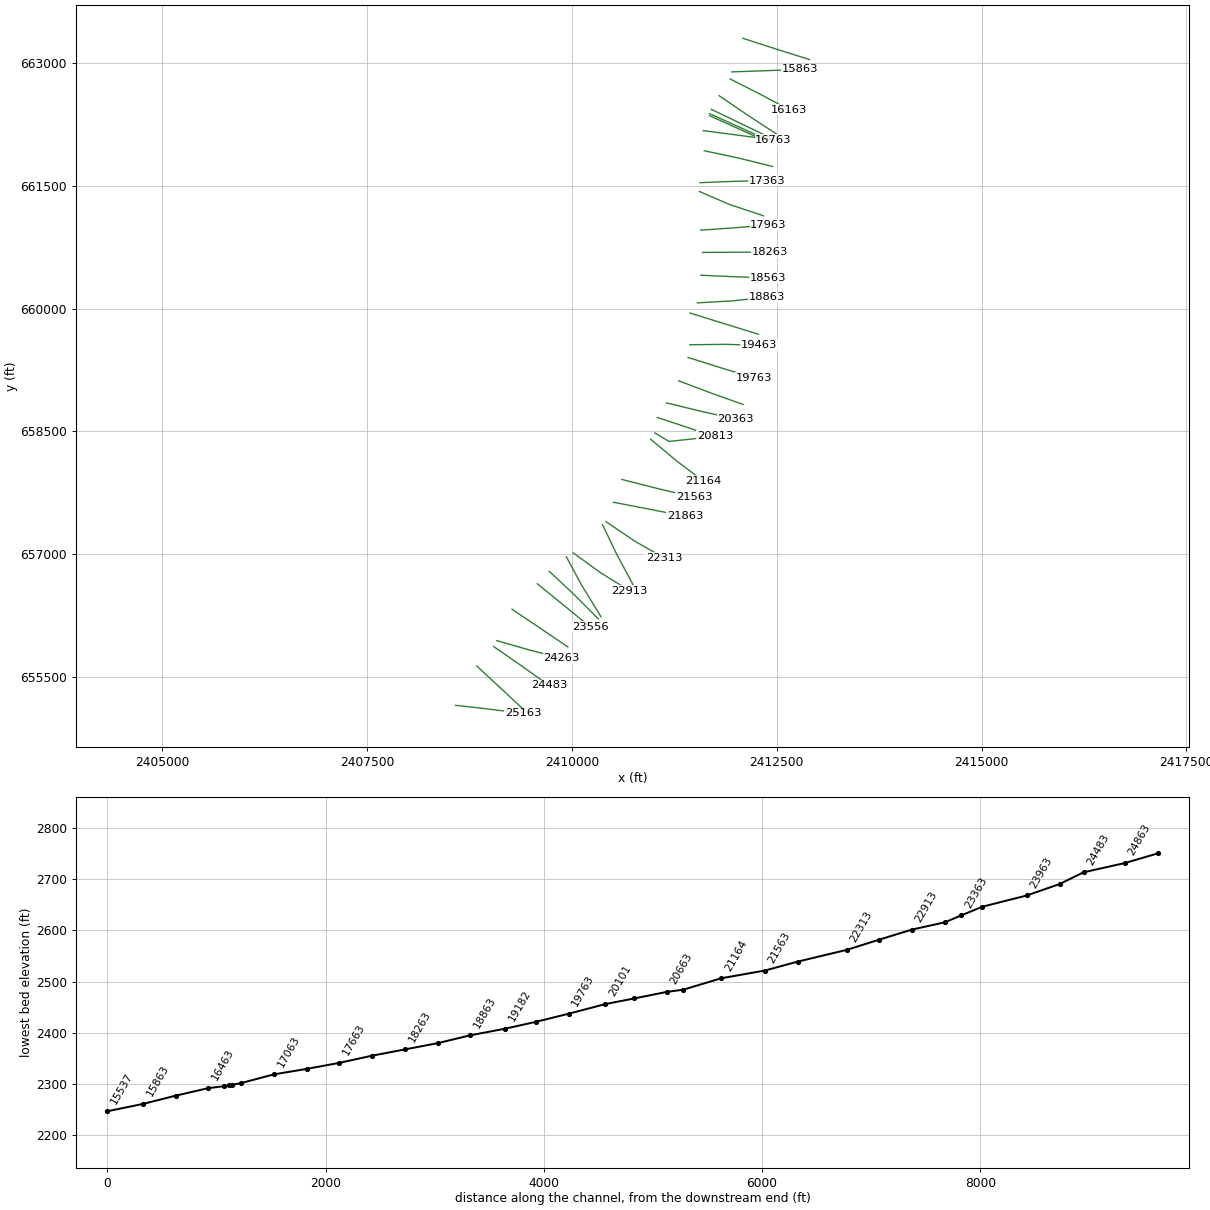
HEC-RAS study BRUSHRN.prj: BRUSHRN

--- BRUSHRN.g02 (geometry) --- (continued)

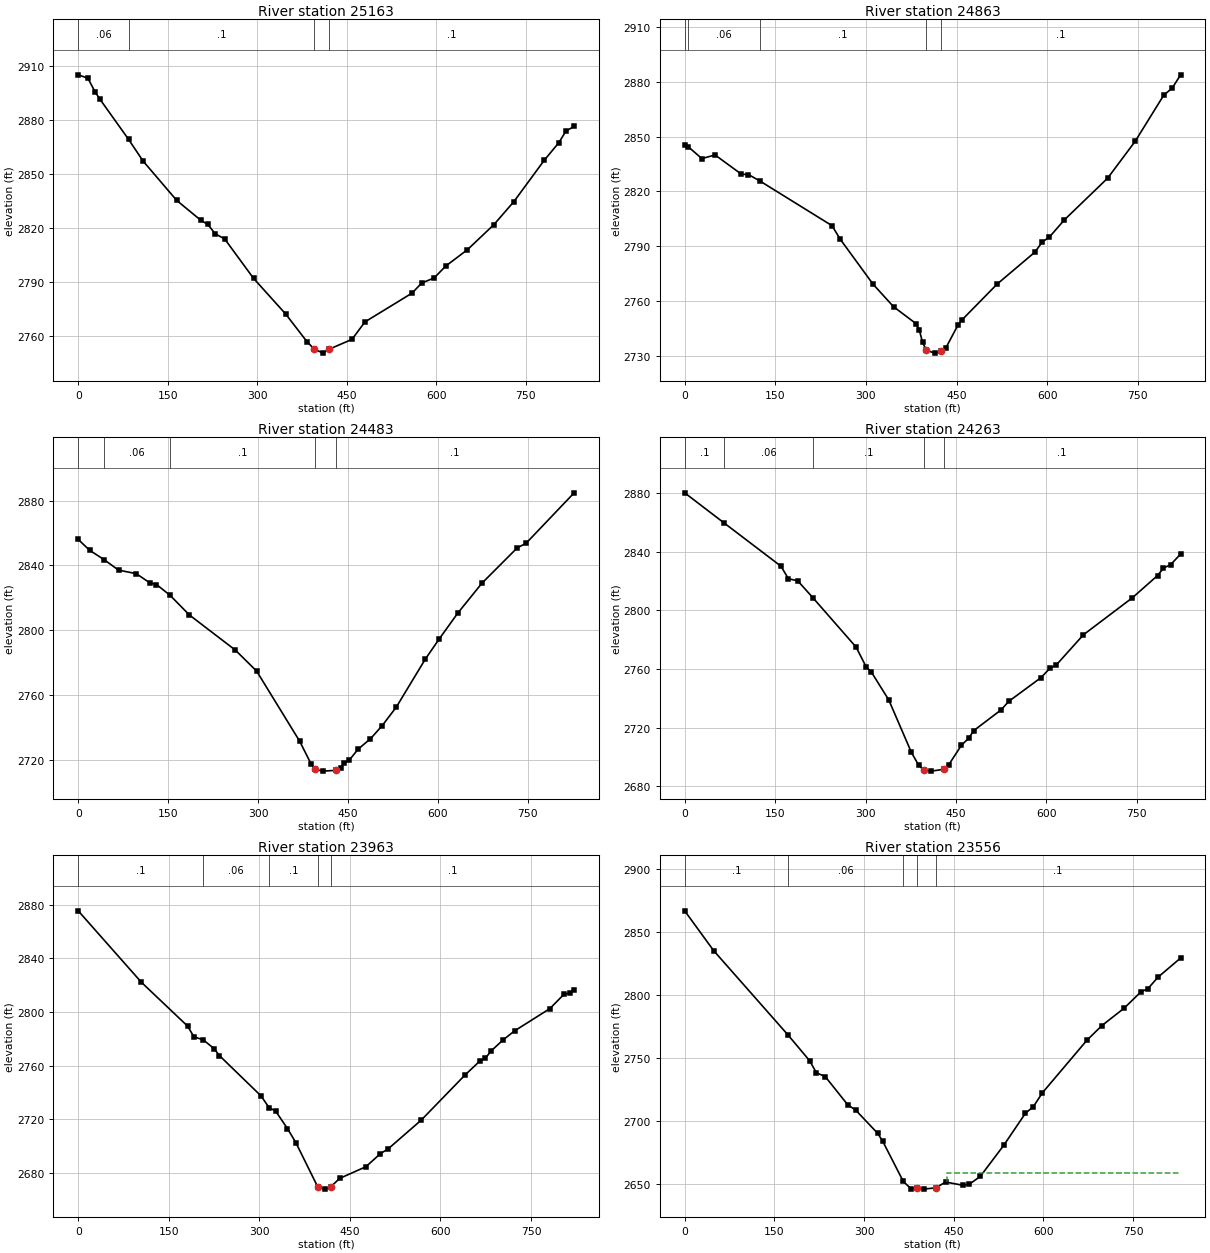
Type RM Length L Ch R = 1 ,25163   ,300,300,300
XS GIS Cut Line= 3
     2408578.689      655155.475      2408983.54      655109.559
2409404.37723474655057.267408432
#Sta/Elev= 30
       0 2905.14    16.2 2903.27    28.2 2895.68    36.3 2891.62   84.552869.155
   108.7 2857.16   165.1 2835.25   205.4 2824.22   217.4 2821.84   229.5  2816.7
   245.6 2813.77   293.9 2791.88   347.7 2772.05   383.8 2756.51   395.6 2752.51
   410.7 2750.23   419.9 2752.29     459  2757.9   480.8 2767.62   559.7 2783.63
   575.9 2789.24   596.8 2792.09   616.2 2798.69   652.5 2807.78   696.9 2821.74
   730.3 2834.51   781.5 2857.64   805.7 2867.32   817.8 2873.85   831.5 2876.41
#Mann= 4 ,-1 , 0
       0     .06       0   84.55      .1       0   395.6    .045       0
   419.9      .1       0
Bank Sta=395.6,419.9
XS Rating Curve= 0 ,0
Exp/Cntr=0.3,0.1

Type RM Length L Ch R = 1 ,24863   ,379.9,379.9,379.9
XS GIS Cut Line= 3
     2408837.828      655634.655     2409139.935      655354.937
     2409439.033      655075.623
#Sta/Elev= 30
       0 2845.33     5.62844.538    28.5 2837.98    50.3 2839.97    93.9 2829.44
   105.6 2829.24  124.822825.657   243.9 2801.25   257.5 2793.85   311.8 2769.23
   345.8 2756.87   382.8 2747.66   388.3  2744.3   393.7  2737.5     400  2733.1
   413.7 2731.47   425.1 2732.76     432  2734.1   452.8 2747.09     459 2749.64
   517.3 2769.29   579.8 2786.78     592 2792.35   603.4 2794.87   628.6 2804.44
   700.2 2827.27   745.8 2847.45   793.2 2872.76   807.1 2876.57     821 2883.84
#Mann= 5 ,-1 , 0
       0      .1       0     5.6     .06       0  124.82      .1       0
     400    .045       0   425.1      .1       0
Bank Sta=400,425.1
XS Rating Curve= 0 ,0
Exp/Cntr=0.3,0.1

Type RM Length L Ch R = 1 ,24483   ,220.1,220.1,220.1
XS GIS Cut Line= 3
2409043.15259825655873.1468436952409379.48059824655640.481843695
2409720.13813204655397.837749673
#Sta/Elev= 30
       0 2856.04      19 2849.36   42.97 2843.65    67.2 2837.15    96.8 2834.96
   119.2 2829.36   130.5 2828.28  152.972821.724   185.3 2809.56   262.2 2787.85
   297.5    2775   369.2  2731.9   388.6 2717.68   395.2  2714.4   408.1 2713.37
   429.7 2713.84   437.5  2715.2     444 2718.35   452.3 2720.22   466.9 2726.91
   487.5  2733.3   507.1 2741.41   530.8 2752.93   578.8 2782.24   601.7 2794.54
   633.3 2810.77   673.4 2829.09   732.2 2850.84   746.9 2853.63   827.2 2884.73
#Mann= 5 ,-1 , 0
       0      .1       0   42.97     .06       0  152.97      .1       0
   395.2    .045       0   429.7      .1       0
Bank Sta=395.2,429.7
XS Rating Curve= 0 ,0
Exp/Cntr=0.3,0.1

Type RM Length L Ch R = 1 ,24263   ,300,300,300
XS GIS Cut Line= 3
     2409081.368      655945.494     2409474.321      655832.691
     2409874.643      655728.158
#Sta/Elev= 30
       0 2880.03      662859.307   159.6 2830.07   172.1 2821.51   187.5 2820.08
  212.782808.508   284.4 2774.89   301.1 2761.38   309.4  2758.1   338.5 2738.95
     376 2703.23     388 2694.53   396.8 2691.04   408.8 2690.43   429.3 2691.62
   438.2 2694.88   458.9 2707.98   471.3 2712.98   479.6 2718.07     525 2732.21
   537.4 2737.91   591.2 2754.19   605.9 2760.54     616 2762.58   661.4 2783.33
   742.6 2808.54   784.4  2823.7   794.2 2828.74   806.1 2831.14   822.6 2838.32
#Mann= 5 ,-1 , 0
       0      .1       0      66     .06       0  212.78      .1       0
   396.8    .045       0   429.3      .1       0
Bank Sta=396.8,429.3
XS Rating Curve= 0 ,0
Exp/Cntr=0.3,0.1

Type RM Length L Ch R = 1 ,23963   ,406.7,406.7,406.7
XS GIS Cut Line= 3
     2409268.028       656329.01     2409606.824      656099.924
      2409948.49       655868.87
#Sta/Elev= 30
       0 2875.41   104.7 2822.16   181.2 2789.52   191.6 2781.57  206.892779.355
   225.2 2772.71   233.9 2767.55   302.7 2737.59  316.352728.665   326.8 2726.34
   346.6 2713.22   360.6 2702.63   396.5 2669.96   408.9 2668.11   418.5 2669.94
     433 2676.08   476.5 2684.81   500.6 2694.57   513.4 2698.11   568.1  2719.5
   640.7 2753.13   664.8 2763.34   674.5 2765.62   683.3 2770.79   703.4 2779.13
   722.8 2786.01   781.3 2802.61   804.3 2813.15   814.5 2814.21   821.4  2816.8
#Mann= 5 ,-1 , 0
       0      .1       0  206.89     .06       0  316.35      .1       0
   396.5    .045       0   418.5      .1       0
Bank Sta=396.5,418.5
XS Rating Curve= 0 ,0
Exp/Cntr=0.3,0.1

Type RM Length L Ch R = 1 ,23556   ,193.3,193.3,193.3
XS GIS Cut Line= 2
2409577.10981196656639.3598119582410220.15441529656115.141601385
#Sta/Elev= 30
       0 2866.58    48.6    2835  172.692768.378     209 2747.93   220.4 2738.32
     235 2735.41     273 2712.89   285.8 2708.93   322.8 2690.44   331.3 2684.13
   365.72652.323   378.8 2646.47   389.2 2647.07   399.5 2646.25   420.1  2647.3
   436.5 2651.85   464.9 2649.35   476.3 2650.18   494.5  2656.3   533.7 2680.91
   570.1 2706.38   583.2  2711.5   598.5 2722.57     673 2764.19     698 2775.74
   735.1  2789.5   763.4 2802.49   774.8 2804.91   791.7 2813.99   829.6 2829.23
#Mann= 5 ,-1 , 0
       0      .1       0  172.69     .06       0   365.7      .1       0
   389.2    .045       0   420.1      .1       0
#XS Ineff= 2 , 0
                          438.23         2658.63
Permanent Ineff=
       F       F
Bank Sta=389.2,420.1
XS Rating Curve= 0 ,0
Exp/Cntr=0.3,0.1

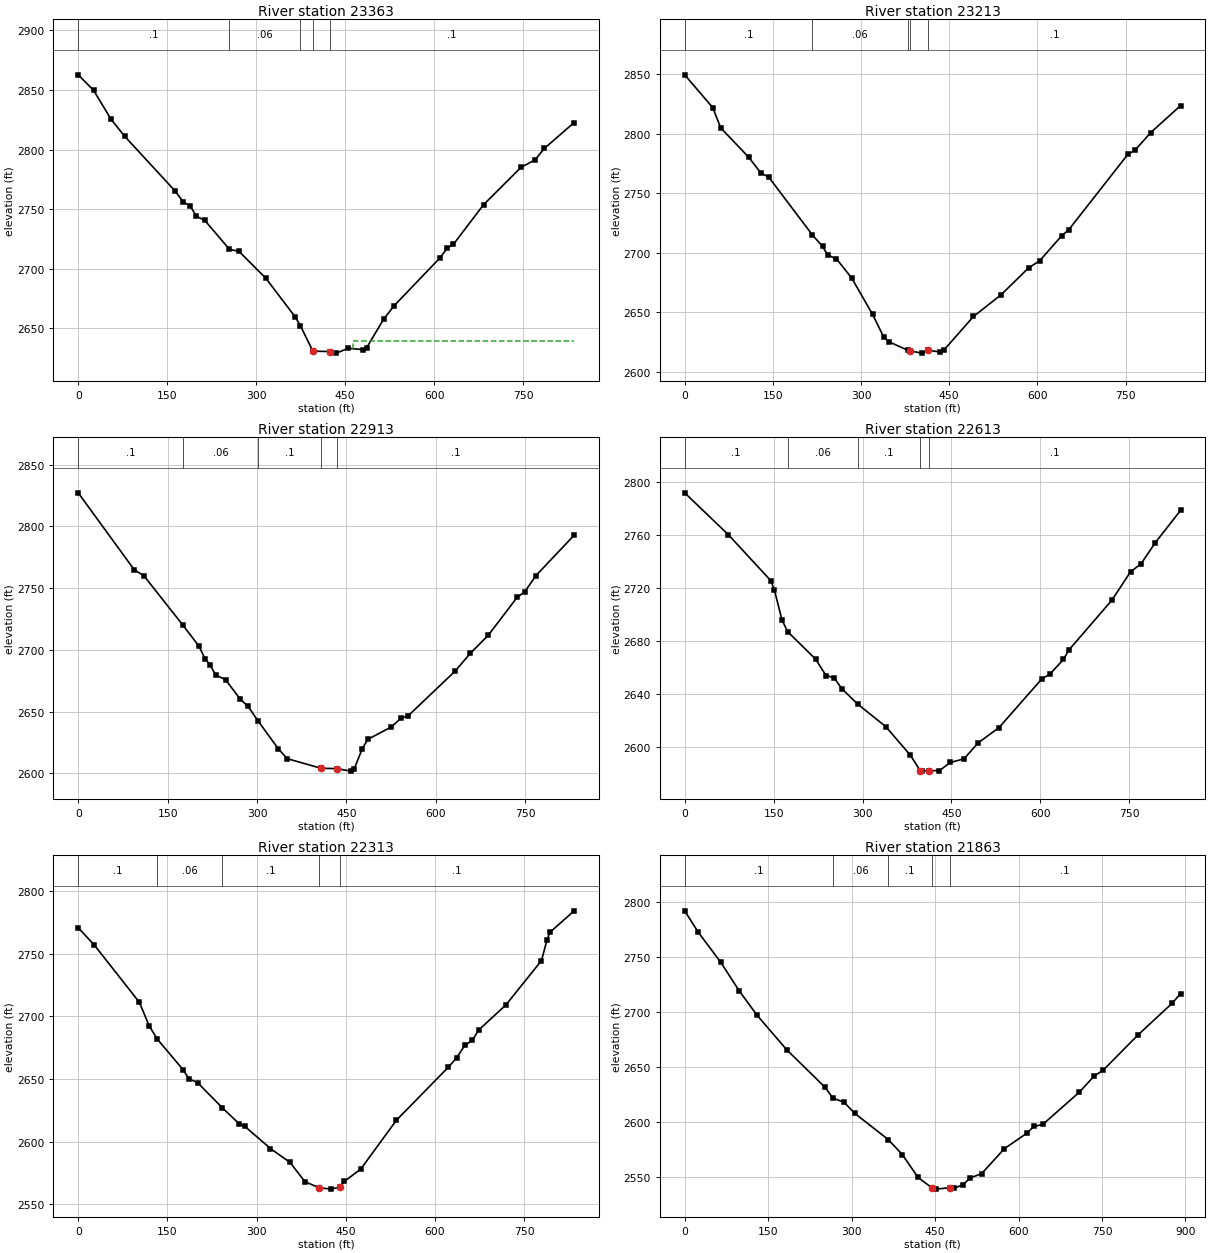
Type RM Length L Ch R = 1 ,23363   ,150,150,150
XS GIS Cut Line= 3
2409721.44384271656792.745685424     2410025.753      656507.812
     2410321.387      656210.556
#Sta/Elev= 30
       0 2862.58    26.1 2849.47    55.4 2825.29    78.6 2810.91   163.5 2765.15
   177.1 2756.06     189 2752.58   199.1 2744.13   213.4 2740.58  255.01 2716.35
   271.1 2714.62   316.4 2692.04   365.6 2659.86  374.682652.219   395.6    2631
   423.8 2630.69   435.3 2629.35     455 2633.39   480.2 2632.32   486.4    2634
   514.7 2657.57   531.7 2668.59     610 2709.24   621.9 2717.26   632.6 2720.56
   683.3 2753.71   746.3 2784.96     770 2791.25   785.9 2800.92   836.1 2822.59
#Mann= 5 ,-1 , 0
       0      .1       0  255.01     .06       0  374.68      .1       0
   395.6    .045       0   423.8      .1       0
#XS Ineff= 2 , 0
                          462.47         2639.28
Permanent Ineff=
       F       F
Bank Sta=395.6,423.8
XS Rating Curve= 0 ,0
Exp/Cntr=0.3,0.1

Type RM Length L Ch R = 1 ,23213   ,300,300,300
XS GIS Cut Line= 3
2409930.88656023656968.828094022     2410122.531      656613.787
      2410352.59      656238.408
#Sta/Elev= 30
       0 2849.56    47.7 2822.09    61.3 2805.01   109.2  2780.2   129.5 2767.16
     143 2763.65  217.152715.143   234.5  2705.5   243.4 2698.17   258.2 2694.99
     284 2678.97   319.7 2648.29   338.6 2629.27   347.7 2625.28  380.042618.107
     384 2617.69   403.5 2615.82   414.5 2618.17   434.5 2616.81   440.6 2618.13
   491.3  2646.6   538.2 2664.78   585.1 2687.43   603.9 2693.38   641.3 2714.35
     653 2719.21     754  2782.8   766.4 2786.36   792.6 2800.93   843.7 2823.77
#Mann= 5 ,-1 , 0
       0      .1       0  217.15     .06       0  380.04      .1       0
     384    .045       0   414.5      .1       0
Bank Sta=384,414.5
XS Rating Curve= 0 ,0
Exp/Cntr=0.3,0.1

Type RM Length L Ch R = 1 ,22913   ,300,300,300
XS GIS Cut Line= 3
2410014.56276885657016.681838389     2410357.576      656768.391
     2410705.237      656553.889
#Sta/Elev= 30
       0 2827.12      94 2764.79   110.3  2759.9  175.472720.033   202.7 2702.85
   212.6 2692.78   221.4 2687.65   230.6 2679.52   247.1 2675.83   271.8 2660.02
     285 2654.11  301.412642.594     336 2619.57   350.9 2611.78   407.62604.014
   434.1 2603.75   457.4 2601.72   463.2 2603.69   476.5 2619.88   485.9 2627.49
   525.3 2637.51   542.3 2644.94   553.3 2646.42     632 2682.56   657.9 2697.13
     688 2711.81   736.4 2742.49   749.1 2746.96   767.9  2760.1     832 2792.78
#Mann= 5 ,-1 , 0
       0      .1       0  175.47     .06       0  301.41      .1       0
   407.6    .045       0   434.1      .1       0
Bank Sta=407.6,434.1
XS Rating Curve= 0 ,0
Exp/Cntr=0.3,0.1

Type RM Length L Ch R = 1 ,22613   ,300,300,300
XS GIS Cut Line= 3
     2410371.585      657361.961     2410547.269      656997.042
 2410751.3349421656616.700985526
#Sta/Elev= 30
       0 2791.61    73.6 2760.13   145.5 2725.42   151.5 2718.24     164 2696.11
  173.622687.163   220.9  2666.4   238.4 2654.11     252 2652.44   265.3 2644.06
  292.032632.538   339.3 2615.62   380.8 2594.11   397.52582.354   400.2 2582.16
   412.52582.469   429.8 2582.59   448.3 2588.71   471.2  2591.4   494.8 2603.34
   530.3 2614.95   602.6 2651.64     616 2655.12     639 2666.25     648 2673.24
   720.7 2710.86   752.4 2732.36   769.6 2737.98   793.2 2753.71   836.6 2778.46
#Mann= 5 ,-1 , 0
       0      .1       0  173.62     .06       0  292.03      .1       0
   397.5    .045       0   412.5      .1       0
Bank Sta=397.5,412.5
XS Rating Curve= 0 ,0
Exp/Cntr=0.3,0.1

Type RM Length L Ch R = 1 ,22313   ,450,450,450
XS GIS Cut Line= 3
2410414.69492763657397.665932453     2410767.539      657159.156
     2411122.527      656956.954
#Sta/Elev= 30
       0  2770.9    26.4 2757.51   102.9 2711.32   119.2 2692.72  133.05 2681.87
   176.4 2657.46   186.4  2650.1   200.8 2647.13   242.52627.022   270.4 2614.39
   280.1 2612.25   323.5 2594.43   356.4 2583.37   381.5 2567.95   404.9 2563.15
   425.5    2562   440.2 2563.63     448 2568.27   475.4 2578.04   535.5 2617.15
   622.9 2659.54   636.6 2666.89   650.5    2677   663.1 2680.93   673.6 2689.09
   719.6 2709.25   779.4 2744.65   788.6 2760.92   793.3 2767.14   834.4 2784.44
#Mann= 5 ,-1 , 0
       0      .1       0  133.05     .06       0   242.5      .1       0
   404.9    .045       0   440.2      .1       0
Bank Sta=404.9,440.2
XS Rating Curve= 0 ,0
Exp/Cntr=0.3,0.1

Type RM Length L Ch R = 1 ,21863   ,300,300,300
XS GIS Cut Line= 3
 2410506.8472335657634.527887171     2410956.776      657547.737
2411381.60891017657463.857432713
#Sta/Elev= 30
       0  2792.1    24.3 2772.73    65.1 2745.14    97.7 2719.55   130.3 2697.03
   183.2 2665.91   252.5 2631.55  266.432621.809   286.5 2618.07   305.4 2608.08
  365.792584.189     391 2570.57   419.6 2549.67   443.6 2540.54   452.1 2539.09
   476.5 2540.41   484.7 2539.98   500.3 2543.13   513.2 2549.32   533.6 2553.11
   574.4  2575.8   615.2 2590.03   627.3 2596.03   643.7 2597.93   709.2 2627.21
   736.4 2642.14   751.7 2647.02   814.9 2679.34   875.6 2707.86   891.3 2716.87
#Mann= 5 ,-1 , 0
       0      .1       0  266.43     .06       0  365.79      .1       0
   443.6    .045       0   476.5      .1       0
Bank Sta=443.6,476.5
XS Rating Curve= 0 ,0
Exp/Cntr=0.3,0.1

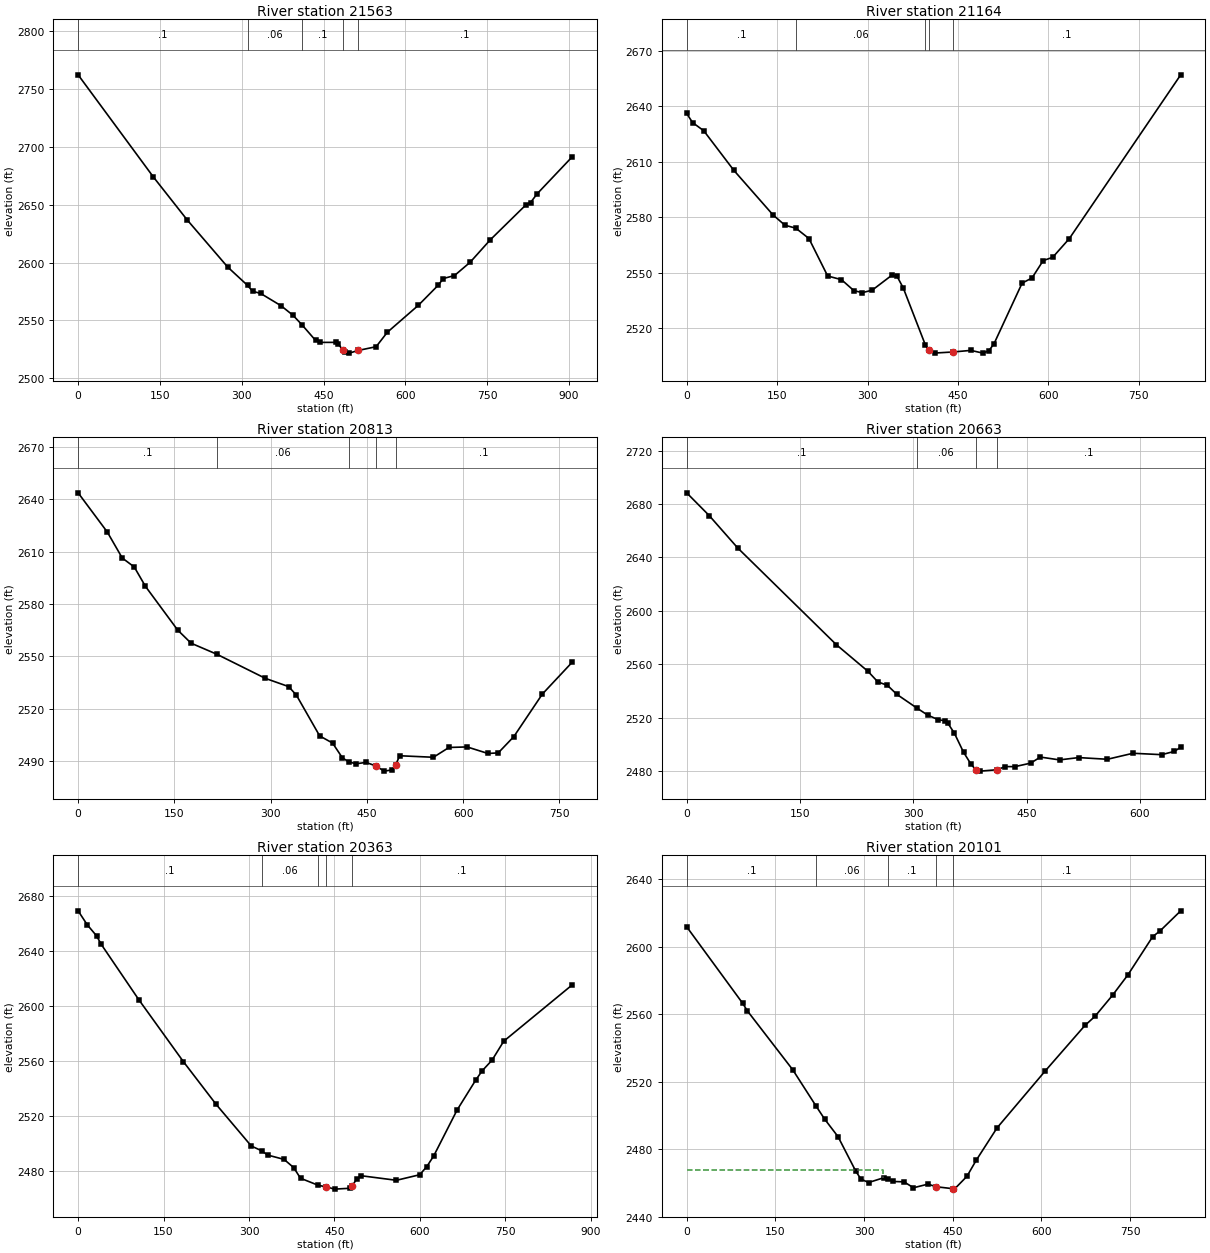
Type RM Length L Ch R = 1 ,21563   ,399.3,399.3,399.3
XS GIS Cut Line= 3
2410608.76760919657913.211787708     2411090.353      657790.925
      2411489.13      657699.375
#Sta/Elev= 30
       0 2762.29   138.2 2673.86   200.1 2636.81   274.4 2596.06  310.822580.199
   319.8 2575.15   334.5 2573.36   372.2 2562.64   394.1  2554.4  410.522546.179
   435.4 2532.73   443.6 2530.98   472.5 2530.99   477.5 2529.56   484.9 2524.53
     489 2522.51   497.3 2521.69   513.3 2523.97   546.5 2527.24     567 2539.69
   624.1  2563.1   660.8 2580.62   669.6 2586.18   690.2 2588.75   718.9 2600.25
   755.8 2619.63     821 2649.77   829.7 2651.91     842 2659.54     906 2691.37
#Mann= 5 ,-1 , 0
       0      .1       0  310.82     .06       0  410.52      .1       0
   484.9    .045       0   513.3      .1       0
Bank Sta=484.9,513.3
XS Rating Curve= 0 ,0
Exp/Cntr=0.3,0.1

Type RM Length L Ch R = 1 ,21164   ,350.7,350.7,350.7
XS GIS Cut Line= 3
2410959.32920747658405.1353039632411273.08720747658142.183303963
2411601.08420747657895.832303963
#Sta/Elev= 30
       0 2636.14     9.7 2631.24    28.4 2626.76    78.2 2605.41   143.1 2581.36
     163 2575.73  181.11 2574.15   202.8 2568.56   233.9  2548.3   256.7 2546.34
   277.5 2540.37   291.5 2539.32   307.8 2540.65   339.8 2548.58   348.9 2548.18
   359.3 2541.85  395.95 2511.08   401.9 2508.14   411.4 2506.67   441.4 2507.24
   471.5 2508.11   491.5 2506.63   501.5 2507.97     510 2511.79   556.5 2544.47
   572.9 2547.24   591.5 2556.65   607.2 2558.39   634.7 2568.47   819.6    2657
#Mann= 5 ,-1 , 0
       0      .1       0  181.11     .06       0  395.95      .1       0
   401.9    .045       0   441.4      .1       0
Bank Sta=401.9,441.4
XS Rating Curve= 0 ,0
Exp/Cntr=0.3,0.1

Type RM Length L Ch R = 1 ,20813   ,150,150,150
XS GIS Cut Line= 4
     2411011.769       658480.912411183.42894969658377.852560834
     2411461.894      658406.6062411748.71614576658448.416174409
#Sta/Elev= 30
       0 2643.71    45.5 2621.24    68.8 2606.36    87.5 2601.23   104.9 2590.15
   155.2 2565.08   176.1 2557.56  216.142551.249     292 2537.39   328.2 2532.69
   340.3 2527.74   376.5 2504.44   396.6 2500.35   411.9 2491.88  421.882489.583
   432.8 2488.48   448.9 2489.26   463.72487.282     477 2484.27   489.1 2484.95
     495 2487.94   501.2 2493.08   553.8 2492.21     578 2497.83   606.3 2498.13
   638.7 2494.39   654.8 2494.72   679.1 2504.05   723.6 2528.44     770 2546.64
#Mann= 5 ,-1 , 0
       0      .1       0  216.14     .06       0  421.88      .1       0
   463.7    .045       0     495      .1       0
Bank Sta=463.7,495
XS Rating Curve= 0 ,0
Exp/Cntr=0.3,0.1

Type RM Length L Ch R = 1 ,20663   ,300,300,300
XS GIS Cut Line= 3
     2411042.495      658670.098     2411418.577      658545.287
2411662.60250508658461.578264239
#Sta/Elev= 30
       0 2688.33    29.8 2671.32    67.7 2646.98   198.3 2574.59   240.1 2554.68
   253.1  2546.8   265.8 2544.21   278.4 2537.42  304.452527.346   319.2  2521.9
   333.2 2518.47   341.6 2517.71   345.9 2515.75   354.3 2508.59   366.6 2494.15
   376.1 2485.54   382.5 2481.16   388.8 2479.98   410.9 2481.01   421.8 2483.38
   434.5 2483.33   455.6 2485.98   468.3 2490.51   493.7 2488.39   519.1 2490.12
   557.1 2488.86     591 2493.35     629  2492.3   645.9 2494.77   654.2 2497.94
#Mann= 4 ,-1 , 0
       0      .1       0  304.45     .06       0   382.5    .045       0
   410.9      .1       0
Bank Sta=382.5,410.9
XS Rating Curve= 0 ,0
Exp/Cntr=0.3,0.1

Type RM Length L Ch R = 1 ,20363   ,262.2,262.2,262.2
XS GIS Cut Line= 3
2411151.30798361658848.320698868     2411589.015      658742.436
     2411995.897      658651.408
#Sta/Elev= 30
       0 2669.42    15.9 2659.34    32.3 2651.27    40.6 2645.05   106.4 2604.91
   184.6 2559.91   242.2 2528.79     304  2498.5  321.952495.064   332.8 2491.91
   361.6 2488.75   378.5 2482.77   390.4 2475.06  421.562469.938   435.7 2468.77
   450.3 2467.15   476.7 2467.77   480.8 2469.17     489 2474.58   497.2 2476.87
   558.8 2473.57   599.7 2477.61   612.2 2483.58   624.3 2491.31   665.2 2524.58
     698 2546.39   709.3 2553.14   726.7  2560.9   747.2 2574.67   867.3 2615.56
#Mann= 5 ,-1 , 0
       0      .1       0  321.95     .06       0  421.56      .1       0
   435.7    .045       0   480.8      .1       0
Bank Sta=435.7,480.8
XS Rating Curve= 0 ,0
Exp/Cntr=0.3,0.1

Type RM Length L Ch R = 1 ,20101   ,337.8,337.8,337.8
XS GIS Cut Line= 3
2411302.84978217659117.2492944122411703.31378217658966.175294412
2412087.43240759658829.453081981
#Sta/Elev= 30
       0 2611.87    94.9  2566.4   102.5 2562.07   179.4 2527.06  218.822505.533
   233.3 2497.81     256 2487.38   286.3 2466.72   294.9 2462.17   307.7 2460.15
   333.4 2463.01  340.152462.194   349.4 2460.77   367.6 2460.57   383.6 2457.05
   408.4 2459.22   421.4 2457.67   449.7 2456.53   452.9 2456.24   474.1 2463.84
   489.6 2473.26   525.1 2492.61   606.2 2526.22   673.7 2553.34   690.7 2558.75
   720.4 2571.27   746.4 2583.36   788.3 2606.03     801  2609.5   835.7 2621.34
#Mann= 5 ,-1 , 0
       0      .1       0  218.82     .06       0  340.15      .1       0
   421.4    .045       0   449.7      .1       0
#XS Ineff= 2 , 0
          332.05 2467.34
Permanent Ineff=
       F       F
Bank Sta=421.4,449.7
XS Rating Curve= 0 ,0
Exp/Cntr=0.3,0.1

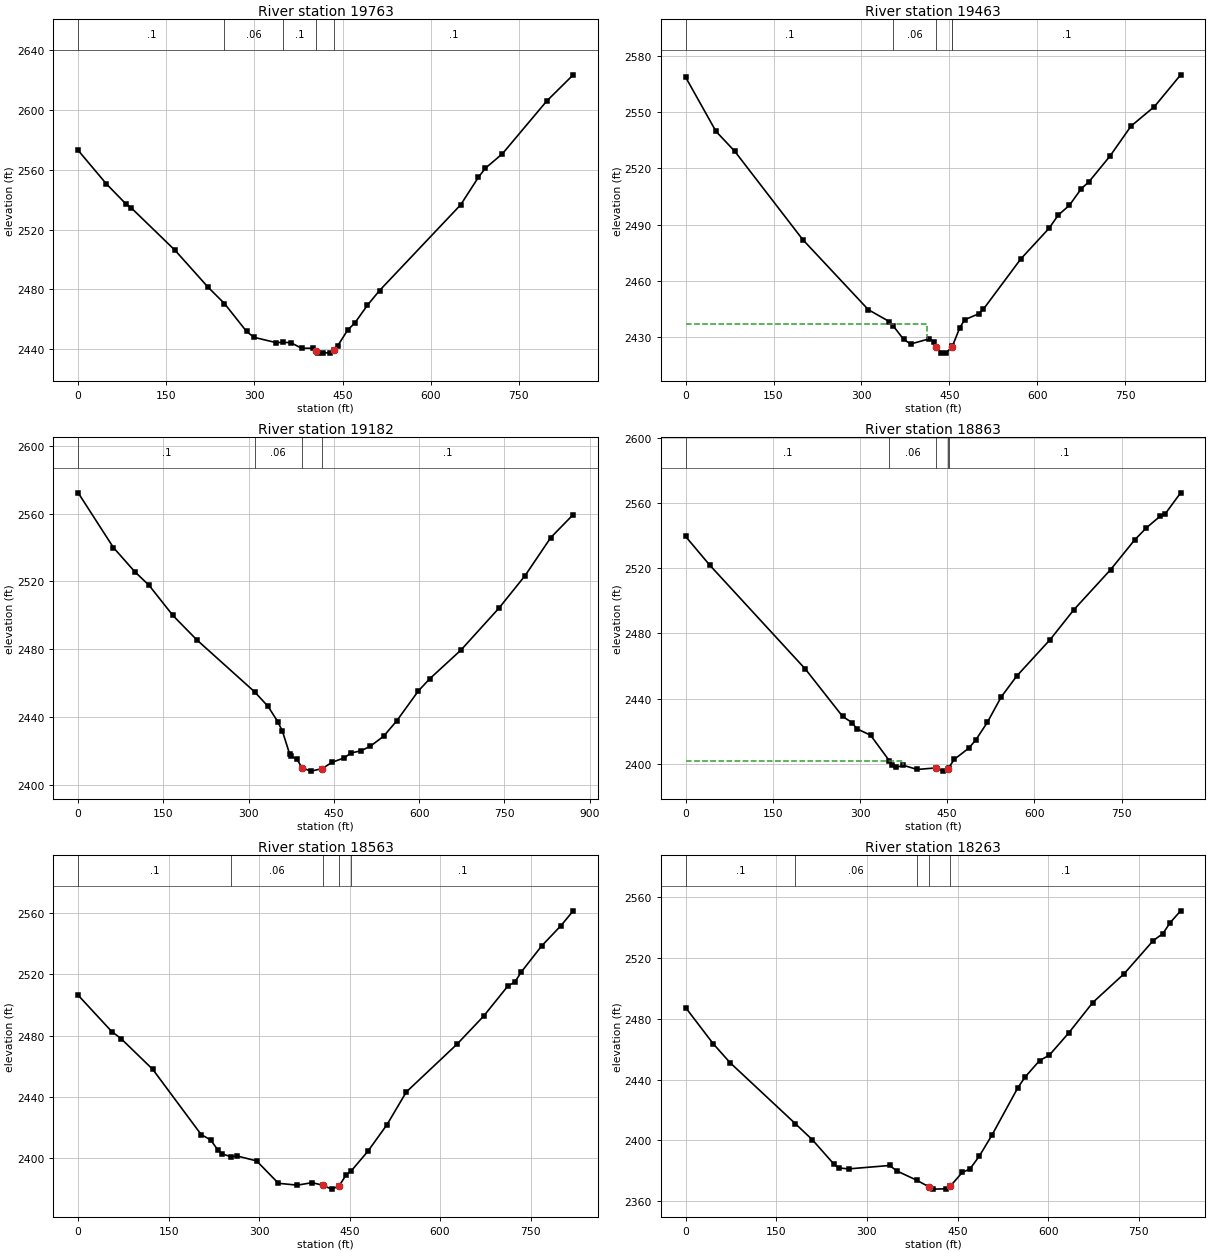
Type RM Length L Ch R = 1 ,19763   ,300,300,300
XS GIS Cut Line= 3
     2411417.281      659402.621     2411816.176      659276.983
2412221.86962586659152.038006279
#Sta/Elev= 30
       0 2573.07    47.7 2550.77    81.2 2537.22    90.3  2534.6   165.1  2506.1
     221 2481.54  249.082470.515   286.7 2451.84   299.3 2447.94     337 2444.39
  349.45 2444.62   362.2 2444.32   380.5  2440.6   399.6 2440.67   404.1 2439.01
   408.3 2437.73   416.7 2437.36   429.3 2437.76   434.7 2439.12   441.8 2442.24
   458.6 2452.72   471.1 2457.63   492.3 2469.37     513 2479.26   651.1 2536.64
   681.1 2554.92     693 2561.06   722.3 2570.86   797.6 2606.09   842.7 2623.63
#Mann= 5 ,-1 , 0
       0      .1       0  249.08     .06       0  349.45      .1       0
   404.1    .045       0   434.7      .1       0
Bank Sta=404.1,434.7
XS Rating Curve= 0 ,0
Exp/Cntr=0.3,0.1

Type RM Length L Ch R = 1 ,19463   ,281.1,281.1,281.1
XS GIS Cut Line= 3
     2411438.947       659557.64     2411880.347      659563.229
2412283.40532517  659549.9110339
#Sta/Elev= 30
       0 2568.55    51.8 2539.69    83.8 2529.09   199.8 2482.04   311.8 2444.67
   347.8  2438.3  354.552435.892   371.8 2428.96   383.8 2426.37   415.8 2429.16
   423.8 2427.68     428 2424.94   435.8 2421.85   443.8 2421.53  453.75 2424.59
  455.282425.322   467.8    2435   475.9 2439.28   499.9 2442.45   507.9 2444.85
   571.9  2471.7   619.9 2487.95   635.9 2495.09   654.7 2500.22   675.3 2509.18
   688.2  2512.8     724 2526.45     760 2542.47     800 2552.89   844.7 2569.79
#Mann= 5 ,-1 , 0
       0      .1       0  354.55     .06       0     428    .045       0
  453.75     .06       0  455.28      .1       0
#XS Ineff= 2 , 0
          412.73 2437.31
Permanent Ineff=
       F       F
Bank Sta=428,453.75
XS Rating Curve= 0 ,0
Exp/Cntr=0.3,0.1

Type RM Length L Ch R = 1 ,19182   ,318.9,318.9,318.9
XS GIS Cut Line= 2
2411443.50594162659944.1580734442412275.54667483659686.241131826
#Sta/Elev= 30
       0  2572.2      62 2539.96    99.7 2525.69   124.8 2517.69   166.7 2499.93
   208.6 2485.61  310.312454.982   334.2 2446.33     351 2437.44   359.4 2431.75
   371.9 2418.51   374.4  2416.9   384.5 2415.49     3942410.136   409.6 2408.22
   428.8 2409.64   447.3 2413.49   468.2 2416.03   479.9  2418.9   497.5 2420.18
   514.3 2422.93   537.5  2428.8   560.4 2437.77   598.7 2455.52     619 2462.77
   673.4  2479.5   740.4 2504.26   786.5 2523.46   831.6 2545.84   871.1 2559.39
#Mann= 4 ,-1 , 0
       0      .1       0  310.31     .06       0     394    .045       0
   428.8      .1       0
Bank Sta=394,428.8
XS Rating Curve= 0 ,0
Exp/Cntr=0.3,0.1

Type RM Length L Ch R = 1 ,18863   ,300,300,300
XS GIS Cut Line= 3
2411529.07533921 660068.80398301     2411967.229      660094.232
2412377.48453373660138.770780847
#Sta/Elev= 30
       0 2539.66    41.4 2522.08     206 2458.13   270.1 2429.01   286.2 2425.24
   294.2 2421.51   318.2 2417.45  350.422401.776   355.7 2398.88   362.3  2397.7
   374.7 2398.95   398.3  2396.4   431.5 2397.38   442.4 2395.38   451.1 2396.97
  452.332397.467   462.5 2402.71   486.7 2409.39   498.8 2414.35   518.9 2425.28
     543 2441.04   569.7 2453.87   627.2 2476.29   667.7 2494.53     731 2519.21
   772.4  2537.5   792.5 2544.93   816.5 2552.14   824.7 2553.41   851.6 2566.48
#Mann= 5 ,-1 , 0
       0      .1       0  350.42     .06       0   431.5    .045       0
   451.1     .06       0  452.33      .1       0
#XS Ineff= 2 , 0
          374.56 2401.39
Permanent Ineff=
       F       F
Bank Sta=431.5,451.1
XS Rating Curve= 0 ,0
Exp/Cntr=0.3,0.1

Type RM Length L Ch R = 1 ,18563   ,300,300,300
XS GIS Cut Line= 3
2411575.09928697660406.582826307     2411986.619      660387.965
     2412395.217      660373.806
#Sta/Elev= 30
       0 2506.34    55.7 2482.66    71.2 2478.03   123.8 2457.96   203.9 2415.53
   219.9 2411.96   231.9 2405.22     239 2402.89  253.082401.083   263.9 2401.51
   295.9 2398.33     332 2383.74   363.3 2382.53     388 2384.16   405.4 2382.52
   420.1 2379.94   432.4 2381.89     444 2389.04   453.12391.986   480.1 2404.49
   512.1 2422.02   544.1  2443.3   628.2 2474.47   672.2  2492.7   712.2 2512.25
   724.3 2515.06   734.2 2521.27   768.3 2538.42   800.3 2551.65   820.8 2561.38
#Mann= 5 ,-1 , 0
       0      .1       0  253.08     .06       0   405.4    .045       0
   432.4     .06       0   453.1      .1       0
Bank Sta=405.4,432.4
XS Rating Curve= 0 ,0
Exp/Cntr=0.3,0.1

Type RM Length L Ch R = 1 ,18263   ,300,300,300
XS GIS Cut Line= 3
     2411593.113      660684.963     2412002.607      660687.178
     2412412.101      660689.393
#Sta/Elev= 30
       0 2487.45    45.6 2463.62    73.6 2451.08  181.342410.965   209.6 2400.33
   245.6 2384.11   253.6 2381.72   269.6 2381.08   337.5 2383.34   349.6 2379.71
  382.752373.554     4022369.378   409.6 2367.75     430 2367.95   437.6 2369.55
   457.6 2378.74   470.3    2381   485.6 2389.31   506.5 2403.14   549.6 2434.56
   561.6 2441.63   585.6 2452.48   601.6 2456.01   633.6 2470.59   673.6 2490.75
   725.6 2509.78   773.6 2531.58   789.6 2536.16   801.6  2543.4     819  2551.2
#Mann= 5 ,-1 , 0
       0      .1       0  181.34     .06       0  382.75      .1       0
     402    .045       0   437.6      .1       0
Bank Sta=402,437.6
XS Rating Curve= 0 ,0
Exp/Cntr=0.3,0.1

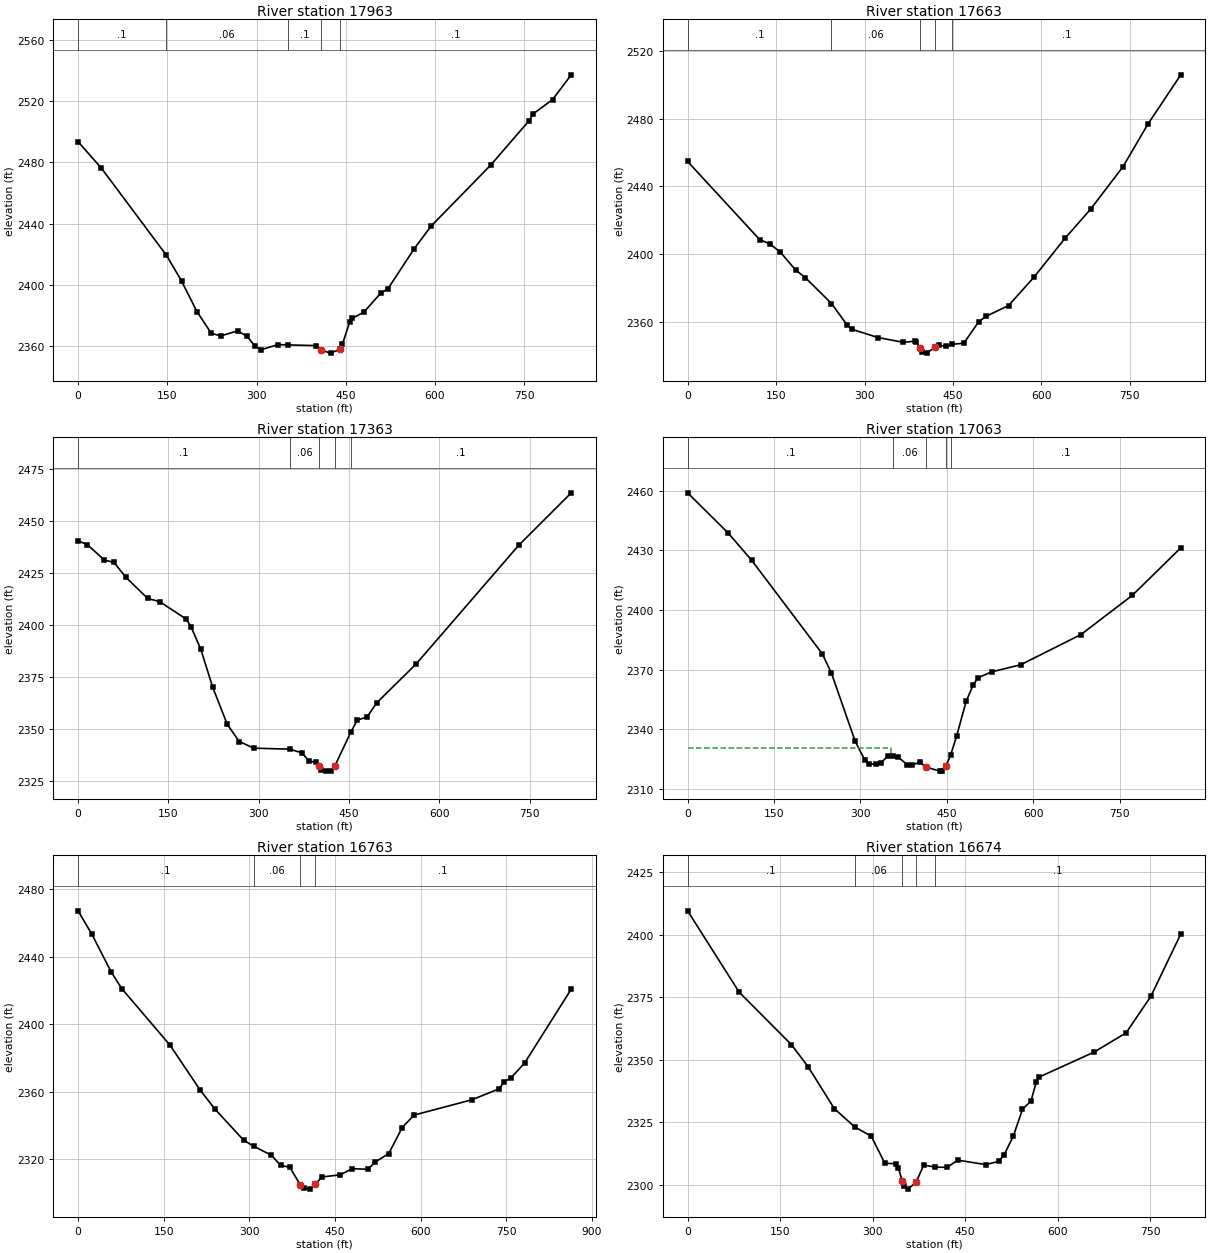
Type RM Length L Ch R = 1 ,17963   ,300,300,300
XS GIS Cut Line= 3
2411571.33786092660956.762695405     2411991.377      660986.241
     2412398.019      661020.221
#Sta/Elev= 30
       0 2493.41    38.9 2476.31  148.462419.434   173.9 2402.64   199.9 2382.61
     224 2368.49     240 2366.82   268.1 2370.06   284.1 2366.58   297.4 2360.14
   308.2 2357.88   336.2 2361.14  352.51 2360.94   400.4 2360.47   408.4 2357.59
   424.5 2355.58   439.6 2357.97   444.5 2361.53   456.6 2375.84   460.6 2378.19
   480.4 2382.29   508.7 2394.62   520.8 2397.46   564.9 2423.53     593 2438.18
   693.4 2478.06   757.6 2506.82   765.6 2511.71   797.7 2520.89   829.1 2537.01
#Mann= 5 ,-1 , 0
       0      .1       0  148.46     .06       0  352.51      .1       0
   408.4    .045       0   439.6      .1       0
Bank Sta=408.4,439.6
XS Rating Curve= 0 ,0
Exp/Cntr=0.3,0.1

Type RM Length L Ch R = 1 ,17663   ,300,300,300
XS GIS Cut Line= 3
     2411554.614      661429.271     2411926.216      661269.152
2412335.76920013661133.111887352
#Sta/Elev= 30
       0 2454.67   122.1 2408.57   139.5    2406   157.2 2401.21   183.1 2390.61
   199.8 2386.07  244.012370.832   270.2 2358.28   278.9 2355.62   322.5 2350.77
     366 2347.92   385.4 2348.64   387.8  2348.4   393.7 2344.74   397.6 2342.43
   405.2 2341.55   419.5 2344.94   425.8 2346.14   438.9 2345.59  448.042346.717
   468.4 2347.41   493.7 2360.13   506.3  2363.3   544.3 2369.65   587.2 2386.33
   640.2  2409.4   683.4 2426.53   738.2 2451.55   780.3 2476.57   836.2 2505.78
#Mann= 5 ,-1 , 0
       0      .1       0  244.01     .06       0   393.7    .045       0
   419.5     .06       0  448.04      .1       0
Bank Sta=393.7,419.5
XS Rating Curve= 0 ,0
Exp/Cntr=0.3,0.1

Type RM Length L Ch R = 1 ,17363   ,300,300,300
XS GIS Cut Line= 3
     2411563.233      661536.679     2411972.416      661552.599
     2412381.824      661563.101
#Sta/Elev= 30
       0 2440.45    15.5 2438.61    43.5 2431.26    59.6 2430.06    79.6 2422.88
   115.6 2412.75   135.6 2411.22   179.6 2402.82   187.7 2399.06   203.7 2388.38
   223.7 2369.97   247.7 2352.23   267.7 2343.98   291.7 2340.78  351.642340.293
   371.8 2338.49   383.8 2334.53   395.8 2333.95   399.8 2332.18   403.8 2330.47
   411.8 2329.74   419.8 2329.89  426.54  2332.3  452.862348.466   463.8 2354.29
   479.8 2355.75   495.9 2362.56   561.5 2381.28   731.9 2438.35     819 2463.53
#Mann= 5 ,-1 , 0
       0      .1       0  351.64     .06       0   399.8    .045       0
  426.54     .06       0  452.86      .1       0
Bank Sta=399.8,426.54
XS Rating Curve= 0 ,0
Exp/Cntr=0.3,0.1

Type RM Length L Ch R = 1 ,17063   ,300,300,300
XS GIS Cut Line= 3
     2411614.184      661926.107       2412035.6      661837.107
2412448.03388672661734.353112648
#Sta/Elev= 30
       0  2458.9    70.1  2438.8     111 2425.09   233.6 2378.08   249.6 2368.35
   290.8 2334.11   307.2 2324.86   315.4 2322.73   327.2 2322.49   335.8 2323.39
   348.1 2326.72  357.092326.842   364.4 2326.38   381.2 2322.31     389    2322
   402.7 2323.63   413.5 2321.11   438.1 2319.08   442.2 2319.34   448.3 2321.64
  456.582327.239   466.9 2336.74   483.4 2354.14   495.8  2362.5     504 2365.98
   527.5 2368.93   578.2 2372.54   682.6  2387.7     772 2407.45   855.8 2431.26
#Mann= 5 ,-1 , 0
       0      .1       0  357.09     .06       0   413.5    .045       0
   448.3     .06       0  456.58      .1       0
#XS Ineff= 2 , 0
          353.12 2330.51
Permanent Ineff=
       F       F
Bank Sta=413.5,448.3
XS Rating Curve= 0 ,0
Exp/Cntr=0.3,0.1

Type RM Length L Ch R = 1 ,16763   ,88.5,88.5,88.5
XS GIS Cut Line= 3
2411602.96547829 662171.99014726     2412003.674      662119.436
     2412459.849      662060.257
#Sta/Elev= 30
       0 2467.29      24 2453.49    57.8 2431.16    76.4 2421.19   161.3 2387.48
   213.6 2361.06   239.7 2349.68   290.2 2331.15  307.942327.554   338.7 2322.26
   354.8 2316.32   370.9 2315.09   389.5 2304.65   395.1 2302.57   407.1 2302.14
   415.3 2304.94   427.4 2309.35   459.7 2310.64   479.8 2314.24   508.1 2313.94
   520.2 2318.14   544.4 2323.26     568 2338.71   588.7 2346.08   689.6 2355.12
     738 2361.69   746.1 2365.74   758.2 2368.06   782.4 2376.98   864.1 2420.82
#Mann= 4 ,-1 , 0
       0      .1       0  307.94     .06       0   389.5    .045       0
   415.3      .1       0
Bank Sta=389.5,415.3
XS Rating Curve= 0 ,0
Exp/Cntr=0.3,0.1

Type RM Length L Ch R = 1 ,16674   ,22.6,22.6,22.6
XS GIS Cut Line= 3
2411679.31384945662354.2837836122412244.73137896662098.463080723
2412422.96081761662078.489091908
#Sta/Elev= 30
       0 2409.59    83.7 2377.06   168.4 2356.11   195.6 2347.23   237.9 2330.55
  271.012323.215   297.9 2319.51   319.9 2308.68   337.7 2308.49   341.8 2306.91
   347.9 2301.78   350.6  2299.7   357.6 2298.34   370.9 2301.22     383 2307.97
  402.072307.112   420.9 2307.07   438.4 2309.92   483.7 2308.14   504.3 2309.41
     513 2311.91   528.1 2319.38   543.2 2330.25     557 2333.59   565.7 2341.28
   570.1 2343.13   658.8 2353.05   711.2  2360.8   751.4 2375.41   799.9 2400.31
#Mann= 5 ,-1 , 0
       0      .1       0  271.01     .06       0   347.9    .045       0
   370.9     .06       0  402.07      .1       0
Bank Sta=347.9,370.9
XS Rating Curve= 0 ,0
Exp/Cntr(USF)=0,0
Exp/Cntr=0.5,0.3

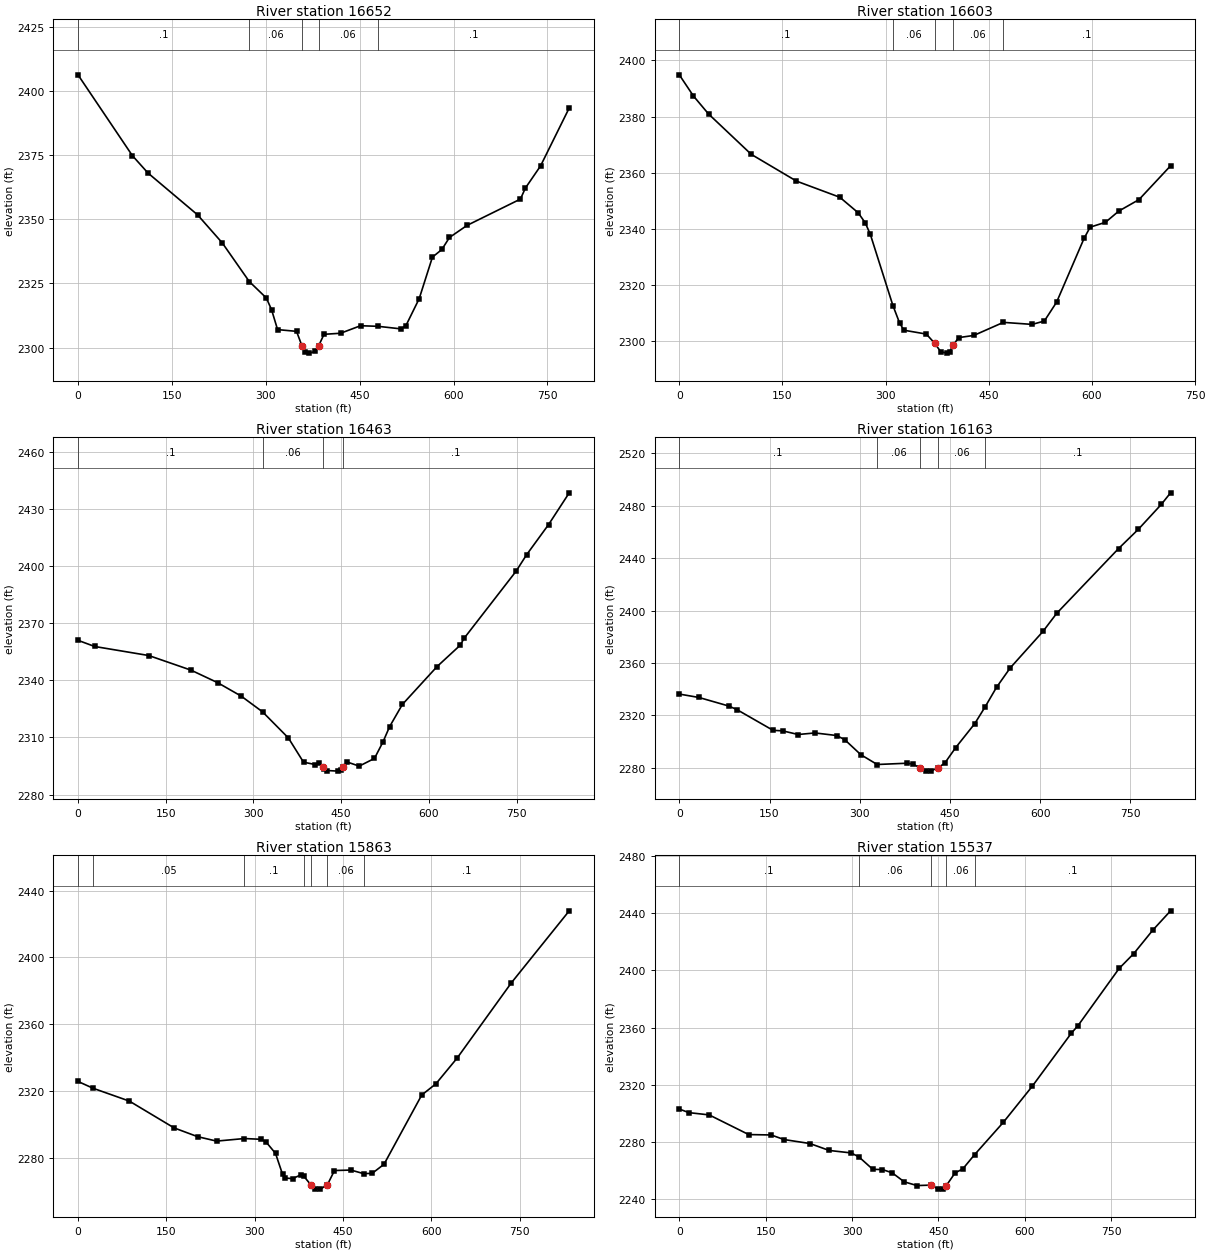
Type RM Length L Ch R = 1 ,16652   ,49.2,49.2,49.2
XS GIS Cut Line= 3
2411680.85031013 662378.86715446 2412255.4866037662117.668839198
2412408.36444116662102.304232418
#Sta/Elev= 30
       0 2406.25    86.9 2374.79   111.9    2368     191 2351.74   230.6 2340.78
  273.652325.764   300.9 2319.36   309.3 2314.78   318.9 2307.03   349.2 2306.35
     358 2300.61   362.4 2298.38   369.9 2297.87     379 2298.56   384.3  2300.6
   393.1  2305.2   419.5 2305.61   451.5 2308.54  479.512308.309   516.2 2307.31
     524  2308.6   545.2  2319.1   566.3 2335.25   581.4 2338.23   593.5  2342.9
   621.6 2347.61   706.9 2357.86   714.9 2362.17     739 2370.74   784.9 2393.36
#Mann= 5 ,-1 , 0
       0      .1       0  273.65     .06       0     358    .045       0
   384.3     .06       0  479.51      .1       0
#XS Ineff= 2 , 0
           350.2    2302   393.1            2302
Permanent Ineff=
       F       F
Bank Sta=358,384.3
XS Rating Curve= 0 ,0
Exp/Cntr(USF)=0,0
Exp/Cntr=0.5,0.3

Type RM Length L Ch R = 1 ,16603   ,139.8,139.8,139.8
XS GIS Cut Line= 2
 2411700.4746669662432.1262068332412344.08097314662122.273303433
#Sta/Elev= 30
       0 2394.86    20.6 2387.32    42.5 2380.94   104.6 2366.58   170.4 2357.05
   233.4 2351.31     260 2345.81   270.3 2342.25   277.8 2338.09  310.582312.802
   320.3  2306.6   326.6 2304.01   359.2 2302.64   371.2  2299.4   380.2 2296.36
   388.7 2295.86   393.2  2296.4   398.2 2298.78   406.5 2301.39   428.2 2302.15
  471.222306.802   513.1 2306.08   530.8 2307.28   548.6 2313.98   588.5 2336.65
   597.4 2340.67   619.6 2342.39   639.1  2346.4   668.4 2350.47   714.3 2362.49
#Mann= 5 ,-1 , 0
       0      .1       0  310.58     .06       0   371.2    .045       0
   398.2     .06       0  471.22      .1       0
Bank Sta=371.2,398.2
XS Rating Curve= 0 ,0
Exp/Cntr(USF)=0,0
Exp/Cntr=0.5,0.3

Type RM Length L Ch R = 1 ,16463   ,300,300,300
XS GIS Cut Line= 3
2411795.11586973662599.093200126     2412151.642      662355.794
     2412493.954      662133.259
#Sta/Elev= 30
       0 2360.98    28.6 2357.74     121    2353   193.3 2345.32   238.8 2338.75
   279.1 2331.69   315.62323.434   359.7 2309.75   385.6 2297.02   405.7 2295.79
   411.9 2296.65   418.8 2294.45   420.1 2293.47   425.7 2292.65   444.9 2292.33
   449.6 2292.81   452.8 2294.24   460.5 2297.08   480.8 2294.96   506.9    2299
   521.4 2307.62   532.8 2315.69   554.6 2327.32   613.8 2347.17   653.5 2358.41
     660 2361.98   748.9  2397.2     767 2405.89   804.6 2421.74   839.9 2438.39
#Mann= 4 ,-1 , 0
       0      .1       0   315.6     .06       0   418.8    .045       0
   452.8      .1       0
Bank Sta=418.8,452.8
XS Rating Curve= 0 ,0
Exp/Cntr=0.3,0.1

Type RM Length L Ch R = 1 ,16163   ,300,300,300
XS GIS Cut Line= 3
     2411929.533      662803.292     2412298.776      662616.089
 2412653.8393304662426.152895531
#Sta/Elev= 30
       0 2336.34    32.8 2333.73    82.1 2327.24    95.5 2324.57   155.9 2308.69
   171.8  2308.3   197.6 2305.51   225.6  2306.7   261.5 2304.74     275 2301.58
   301.8 2290.12     329 2282.64   379.1 2283.63   388.1 2282.99     400 2280.21
   409.5 2277.59   418.5 2277.66   430.5 2280.35   441.2 2283.59   459.3  2295.4
   491.1 2313.74   508.42326.538   527.4 2341.49     550 2356.19   604.5 2384.04
   627.6 2397.98   730.3 2447.28   763.3 2462.02   801.2 2480.87   816.7 2489.76
#Mann= 5 ,-1 , 0
       0      .1       0     329     .06       0     400    .045       0
   430.5     .06       0   508.4      .1       0
Bank Sta=400,430.5
XS Rating Curve= 0 ,0
Exp/Cntr=0.3,0.1

Type RM Length L Ch R = 1 ,15863   ,325.9,325.9,325.9
XS GIS Cut Line= 3
     2411951.617      662889.195     2412358.242      662903.277
2412784.93507119662920.663622037
#Sta/Elev= 30
       0 2325.82   25.852321.707    87.2 2314.07   163.2 2298.03   203.2 2292.78
   235.3 2290.14  282.442291.675   311.3 2291.21   319.3 2289.59   335.3 2282.81
   347.3 2270.23   351.3 2268.06   364.4  2267.7   379.4 2270.15  383.68 2268.99
   395.4 2263.95   395.4 2263.94   403.1 2261.63   411.4 2261.42   423.4 2264.04
   435.4 2272.55   463.4 2272.82  485.022270.664   499.4 2270.86   519.5 2276.29
   583.5 2317.69   607.5 2324.38   643.6 2339.78   735.6 2384.77   833.9 2427.85
#Mann= 7 ,-1 , 0
       0      .1       0   25.85     .05       0  282.44      .1       0
  383.68     .06       0   395.4    .045       0   423.4     .06       0
  485.02      .1       0
Bank Sta=395.4,423.4
XS Rating Curve= 0 ,0
Exp/Cntr=0.3,0.1

Type RM Length L Ch R = 1 ,15537   ,274.1,274.1,274.1
XS GIS Cut Line= 3
2412086.92153672663298.8347514112412513.96530339663160.915088701
2412899.91430339663039.738088701
#Sta/Elev= 30
       0 2303.14    16.6 2300.63    51.9 2299.04   120.6 2285.29   159.5 2285.02
     182 2281.81   226.8 2279.04   260.4 2274.19   298.3 2272.47  311.962269.694
   336.1    2261   352.9 2260.82   369.7 2258.59   390.7 2252.26   412.9 2249.65
     437 2249.96   449.6 2247.16     458  2247.5   463.8 2249.61   478.9 2258.44
   492.5 2261.32  512.822271.213   562.7 2293.78   613.1 2319.06   680.7    2356
   692.7 2361.52     764 2401.41   789.4 2411.78   822.7 2428.28   853.3 2441.67
#Mann= 5 ,-1 , 0
       0      .1       0  311.96     .06       0     437    .045       0
   463.8     .06       0  512.82      .1       0
Bank Sta=437,463.8
XS Rating Curve= 0 ,0
Exp/Cntr=0.3,0.1