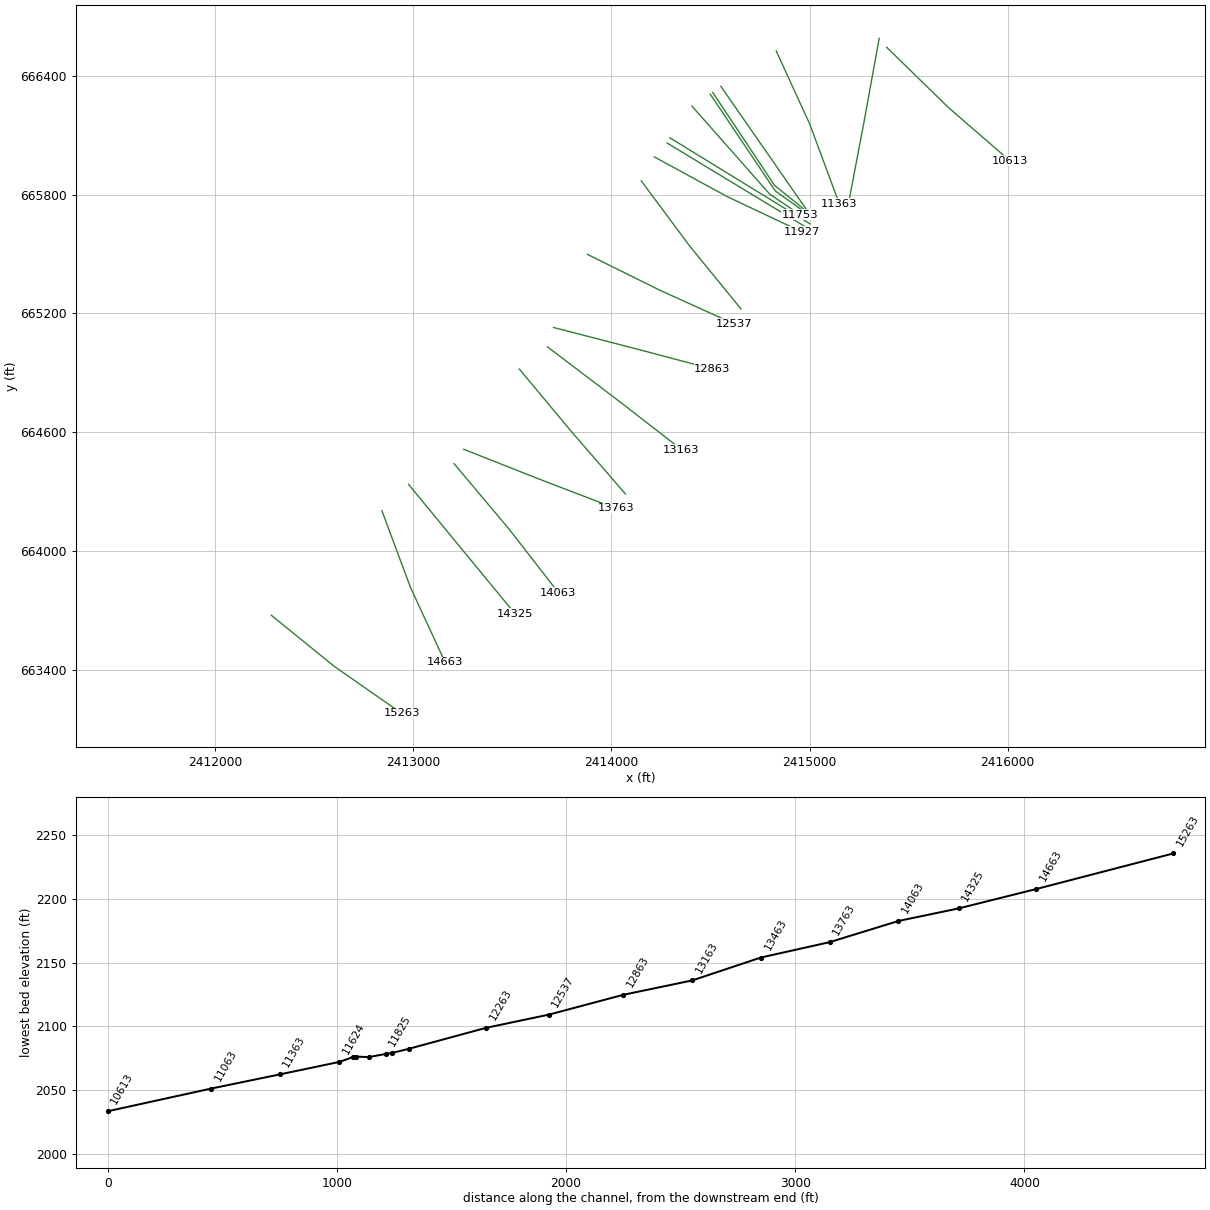
HEC-RAS study BRUSHRN.prj: BRUSHRN

--- BRUSHRN.g02 (geometry) --- (continued)

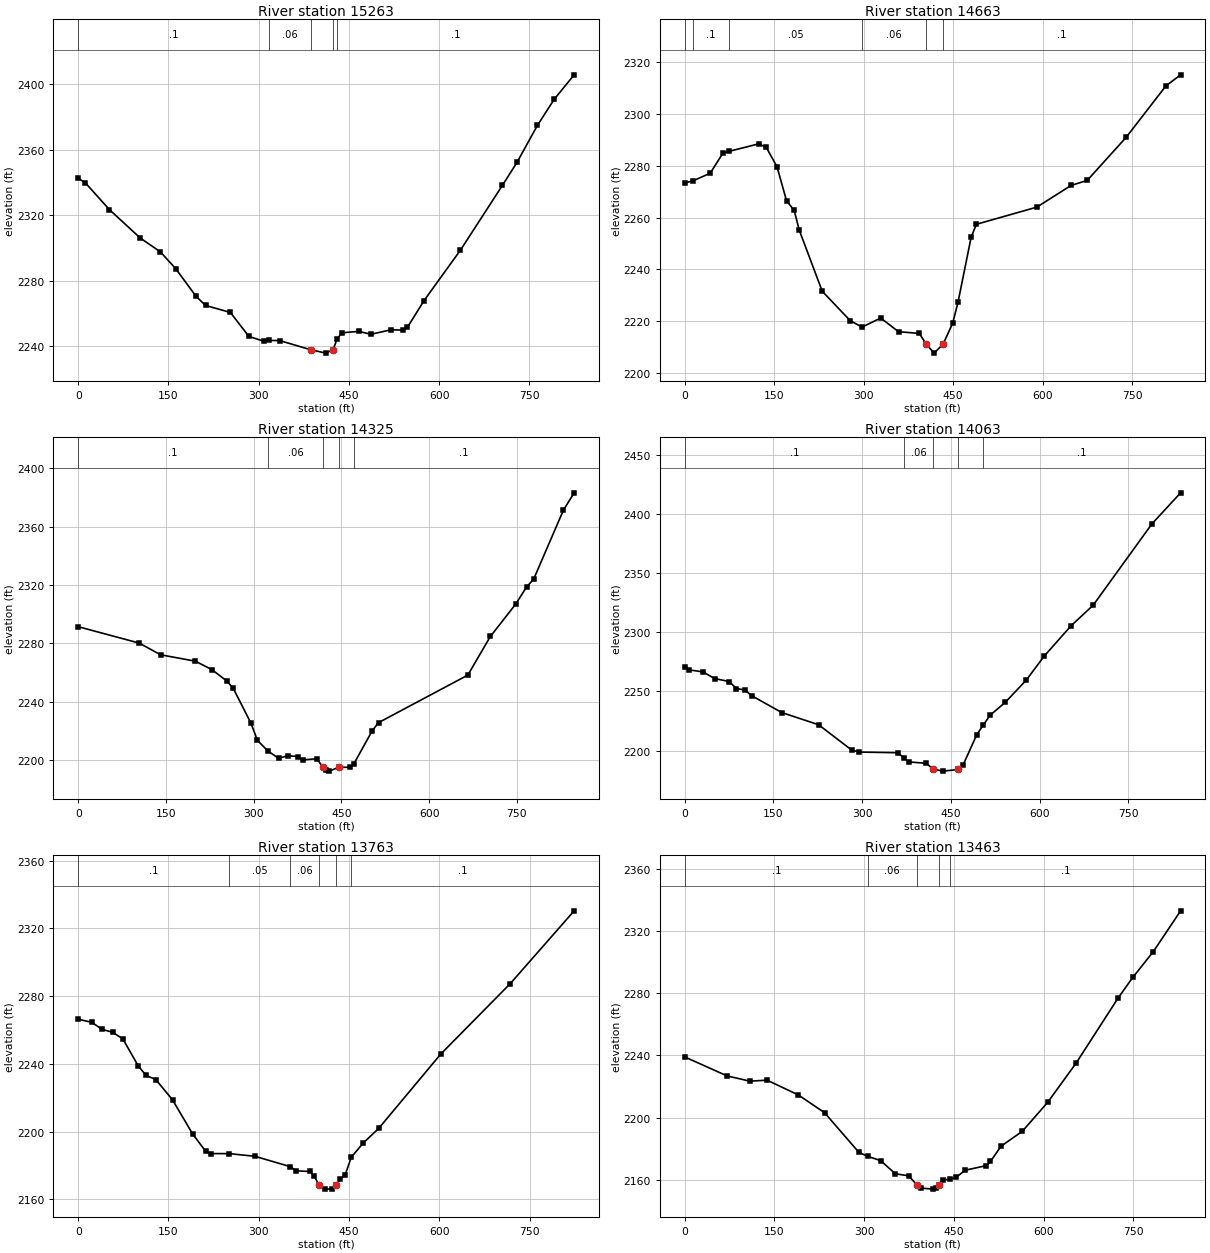
Type RM Length L Ch R = 1 ,15263   ,600,600,600
XS GIS Cut Line= 3
     2412282.453       663674.43     2412599.562      663416.806
2412940.70876526663178.725147892
#Sta/Elev= 30
       0 2342.51      12 2339.63    51.9 2323.31   103.4 2305.89   136.4  2297.6
     162 2287.29   195.9 2270.37   211.7 2264.79     253 2260.52   283.8 2245.85
   309.6 2242.81  316.932243.444   335.4 2243.28   386.6 2237.72   411.9 2235.66
   423.7 2237.83  430.612244.331   438.1 2248.05   466.1 2248.95   486.9 2247.18
   519.8  2249.9   539.3 2249.75   547.3 2251.38   575.1  2267.8   635.6  2298.6
   705.3 2338.13   729.5 2352.14   763.6 2374.81   791.4  2390.7   824.6 2405.66
#Mann= 5 ,-1 , 0
       0      .1       0  316.93     .06       0   386.6    .045       0
   423.7     .06       0  430.61      .1       0
Bank Sta=386.6,423.7
XS Rating Curve= 0 ,0
Exp/Cntr=0.3,0.1

Type RM Length L Ch R = 1 ,14663   ,337.8,337.8,337.8
XS GIS Cut Line= 3
     2412840.752      664202.959     2412985.309      663814.641
     2413160.564      663436.043
#Sta/Elev= 30
       0 2273.34      14 2274.18    42.8 2277.12    64.1 2284.87   73.762285.534
   123.8 2288.44   136.7 2287.15   154.8 2279.62   170.8 2266.48   183.6 2262.75
   192.1 2255.15   230.6 2231.55   277.5 2220.19  297.342217.697   328.7 2221.19
   358.6 2215.91   393.5 2215.26   404.7 2211.13   418.3 2207.64   433.3 2211.13
   449.3 2219.18   458.2 2227.22   480.2  2252.3     489 2257.39   590.4 2264.02
   647.7 2272.39   674.9 2274.34   740.3 2291.01   806.9 2310.86   831.5 2315.12
#Mann= 6 ,-1 , 0
       0     .05       0      14      .1       0   73.76     .05       0
  297.34     .06       0   404.7    .045       0   433.3      .1       0
Bank Sta=404.7,433.3
XS Rating Curve= 0 ,0
Exp/Cntr=0.3,0.1

Type RM Length L Ch R = 1 ,14325   ,262.2,262.2,262.2
XS GIS Cut Line= 2
2412975.45113373664335.6161193092413514.21921345663680.677251135
#Sta/Elev= 30
       0 2291.41   104.5 2280.15   140.8 2272.18   200.4 2267.76   228.8 2261.96
   254.7 2253.99   265.1 2249.19   295.6 2225.15   306.5 2213.49  324.722206.172
   342.8 2201.19   358.3 2203.07   375.1 2202.46   384.2 2200.13   408.2 2200.98
   417.8 2195.45   423.4 2192.92   429.1 2192.47   445.9 2195.14   464.8 2195.07
  471.272197.367     503 2220.29   513.7 2225.72   666.3 2258.26   704.8  2284.7
   748.2 2306.89     767 2318.77   778.7 2323.84   829.8 2371.29   848.1  2383.1
#Mann= 5 ,-1 , 0
       0      .1       0  324.72     .06       0   417.8    .045       0
   445.9     .06       0  471.27      .1       0
Bank Sta=417.8,445.9
XS Rating Curve= 0 ,0
Exp/Cntr=0.3,0.1

Type RM Length L Ch R = 1 ,14063   ,300,300,300
XS GIS Cut Line= 3
     2413205.088      664440.566     2413483.713      664109.046
     2413732.129      663788.745
#Sta/Elev= 30
       0 2270.75       8 2268.12    30.8 2266.51    50.6 2260.83    75.3 2258.35
    87.5 2252.41   101.5 2251.24   113.1  2246.4   164.2 2232.12   226.4 2221.83
   282.3 2200.45   294.8 2198.75   360.1 2198.19  371.172193.614   378.4 2190.44
   408.3 2189.25   420.2 2184.33   436.8 2182.64   462.4 2184.02     471 2188.16
   493.8 2213.42  504.742221.573   516.3 2229.83   542.1 2240.82   577.5 2259.57
   607.7 2279.75   653.4 2305.53   690.5 2322.76   790.1 2391.65   838.4 2417.75
#Mann= 5 ,-1 , 0
       0      .1       0  371.17     .06       0   420.2    .045       0
   462.4     .06       0  504.74      .1       0
Bank Sta=420.2,462.4
XS Rating Curve= 0 ,0
Exp/Cntr=0.3,0.1

Type RM Length L Ch R = 1 ,13763   ,300,300,300
XS GIS Cut Line= 3
     2413253.742      664513.189     2413637.198      664361.644
      2414021.77      664214.278
#Sta/Elev= 30
       0 2266.34    22.6 2264.52    39.8 2260.34      57 2258.68    74.2 2254.74
     100 2238.61   112.9 2233.14   128.9 2230.75   156.7 2218.76   190.3 2198.52
   211.8 2188.37   220.4    2187  250.612186.987   293.5 2185.42  352.282179.315
   362.4 2176.83   384.8 2176.44   392.5 2173.64   400.2 2168.31   409.7 2166.02
   422.5  2166.2  429.12 2168.28   435.4 2171.98   443.5 2174.29  453.86  2184.9
   473.9 2193.33   499.3 2201.84   602.5 2245.77   718.1  2287.4   824.2 2330.36
#Mann= 6 ,-1 , 0
       0      .1       0  250.61     .05       0  352.28     .06       0
   400.2    .045       0  429.12     .06       0  453.86      .1       0
Bank Sta=400.2,429.12
XS Rating Curve= 0 ,0
Exp/Cntr=0.3,0.1

Type RM Length L Ch R = 1 ,13463   ,300,300,300
XS GIS Cut Line= 3
     2413534.667      664918.644     2413795.343      664605.545
     2414071.072       664286.95
#Sta/Elev= 30
       0 2239.06    70.9 2226.84     109 2223.45   137.7  2224.1   190.2 2214.53
   233.9 2203.11   291.2  2177.6  306.16 2175.04   327.6 2172.28   352.1 2163.83
   374.4 2162.52   387.7 2156.83   395.2 2154.65   414.5 2153.96   420.2 2154.41
   424.8 2156.74   430.9 2159.92  443.792160.229   453.2 2161.46   469.1 2166.16
   504.3  2169.1     511 2171.75   528.7 2181.59   564.3 2191.19   606.7 2209.86
   654.3 2235.16   724.3 2276.96   748.8 2290.21   783.2 2306.86   828.8  2333.1
#Mann= 5 ,-1 , 0
       0      .1       0  306.16     .06       0   387.7    .045       0
   424.8     .06       0  443.79      .1       0
Bank Sta=387.7,424.8
XS Rating Curve= 0 ,0
Exp/Cntr=0.3,0.1

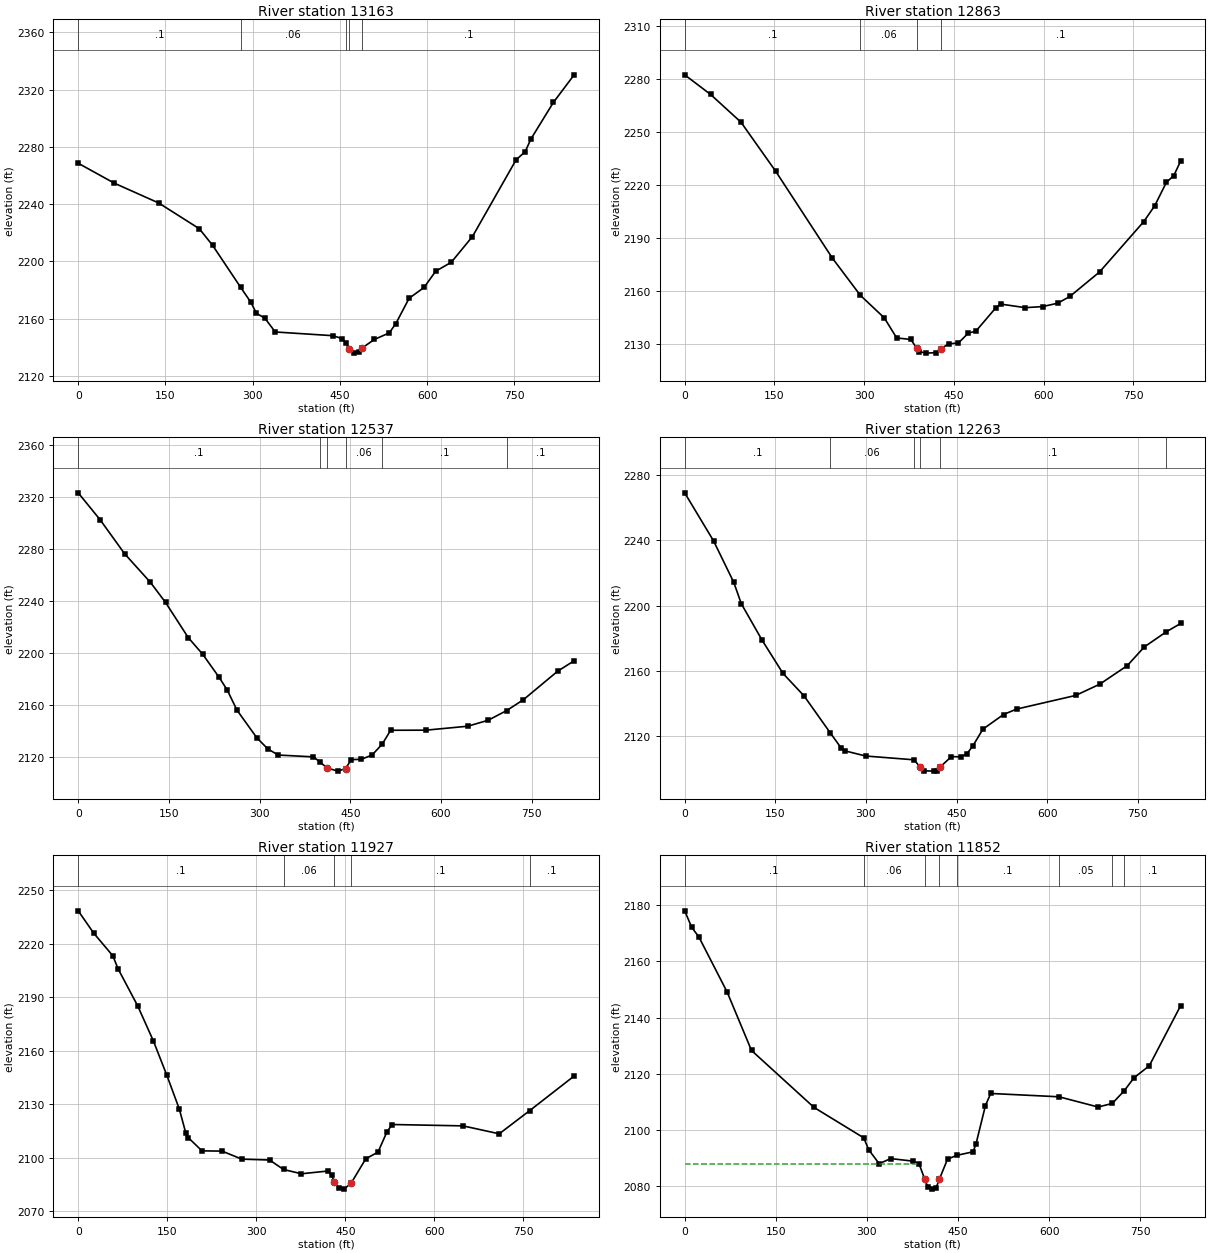
Type RM Length L Ch R = 1 ,13163   ,300,300,300
XS GIS Cut Line= 3
     2413677.121      665030.631     2414055.687      664742.833
2414353.65474242664511.738159659
#Sta/Elev= 30
       0 2268.62    62.3 2254.66   138.4 2240.86   208.1 2222.91   230.9 2211.36
  279.14 2182.01     297 2171.38   306.4 2163.72   320.7 2160.51   338.7 2150.75
   437.7 2148.16   454.3 2146.07  460.282143.262   466.3 2138.88   474.8 2135.97
   483.4 2136.88   488.5 2139.68     509  2145.5   534.7 2150.07   546.1 2156.65
   568.9  2174.3   594.6 2181.86   614.5 2193.17   641.4 2199.44   677.8 2217.44
   752.8 2271.03   768.5 2276.75   778.1 2285.45   816.9 2311.12   852.6  2330.4
#Mann= 5 ,-1 , 0
       0      .1       0  279.14     .06       0  460.28      .1       0
   466.3    .045       0   488.5      .1       0
Bank Sta=466.3,488.5
XS Rating Curve= 0 ,0
Exp/Cntr=0.3,0.1

Type RM Length L Ch R = 1 ,12863   ,325.7,325.7,325.7
XS GIS Cut Line= 3
     2413707.667      665128.517      2414102.03      665026.557
     2414509.794      664918.675
#Sta/Elev= 30
       0 2282.44    43.3 2271.32    94.1  2255.6   151.9  2227.9   246.9 2178.56
  293.732157.452   333.7  2144.7   354.4 2133.33   378.1 2132.45   387.9 2127.47
   391.5 2125.61   403.9 2124.71   420.5 2124.99   428.8 2127.33   441.2 2129.94
   457.7 2130.48   474.3  2136.1   486.7  2137.1   519.8 2150.27   528.1 2152.51
   569.4 2150.48   598.4 2151.09   623.6 2153.01   643.9 2156.82   693.6 2170.72
   767.6 2199.29   785.8 2208.23   805.3 2221.49   817.7 2225.32   829.1 2233.53
#Mann= 4 ,-1 , 0
       0      .1       0  293.73     .06       0   387.9    .045       0
   428.8      .1       0
Bank Sta=387.9,428.8
XS Rating Curve= 0 ,0
Exp/Cntr=0.3,0.1

Type RM Length L Ch R = 1 ,12537   ,274.3,274.3,274.3
XS GIS Cut Line= 3
2413878.06119131665498.2756085582414246.53019131665315.764608558
2414619.17119131665146.922608558
#Sta/Elev= 30
       0 2322.91    36.5 2302.06    76.6  2276.2   119.5 2254.09   144.4 2238.72
   182.1 2211.63   205.9 2198.91   232.9 2181.29   246.3 2171.57   262.7 2155.89
   295.6 2134.64     314 2126.02   331.1 2121.47   389.1 2120.07  399.852116.088
   411.4  2111.7     429 2109.12   442.4 2111.05   451.3 2117.94   468.5 2118.22
   486.1 2121.52  502.862129.877   516.8 2140.51   575.2 2140.59   644.2 2143.61
     678 2148.19  708.662155.631   736.4    2164   793.5 2186.06   820.3 2193.85
#Mann= 6 ,-1 , 0
       0      .1       0  399.85     .06       0   411.4    .045       0
   442.4     .06       0  502.86      .1       0  708.66      .1       0
Bank Sta=411.4,442.4
XS Rating Curve= 0 ,0
Exp/Cntr=0.3,0.1

Type RM Length L Ch R = 1 ,12263   ,336.3,336.3,336.3
XS GIS Cut Line= 3
     2414150.331      665869.548     2414393.187      665542.434
 2414654.2088842665221.999937277
#Sta/Elev= 30
       0 2268.92    47.7  2239.6    81.2 2214.21    93.7 2201.11     128 2178.88
   162.7 2158.49   197.6 2144.71  240.962122.126   259.5  2112.6   265.2 2111.14
   299.5 2107.98   379.52105.662   389.9 2101.15   396.8 2098.93     412 2098.74
   417.1 2098.97   422.4 2101.17   441.5 2107.63   456.5 2107.45   466.9 2109.27
   476.9 2114.17   493.5 2124.39   527.6 2133.36   549.2 2136.67     647 2145.02
   686.8 2151.89   732.3 2163.21   760.7 2174.71  797.182183.981   820.7 2189.02
#Mann= 6 ,-1 , 0
       0      .1       0  240.96     .06       0   379.5      .1       0
   389.9    .045       0   422.4      .1       0  797.18      .1       0
Bank Sta=389.9,422.4
XS Rating Curve= 0 ,0
Exp/Cntr=0.3,0.1

Type RM Length L Ch R = 1 ,11927   ,74.2,74.2,74.2
XS GIS Cut Line= 3
2414215.71624231665990.9233283132414585.13424231665789.416328313
2414960.04021819665612.189202868
#Sta/Elev= 30
       0 2238.47    26.2 2225.91    58.3 2213.25    67.2  2205.9   100.3 2185.07
   126.5 2165.57   149.3  2146.2   170.3 2127.27   181.1 2113.97   185.7 2111.11
   208.5 2103.79   242.3 2103.65   275.7 2099.14   322.4 2098.66  345.912093.339
     376 2090.94   420.8 2092.48   426.9 2090.18   431.4 2086.28   438.9 2082.92
   447.9 2082.32     460 2085.78   484.5 2099.37     505 2103.06     520 2114.35
   528.8 2118.58   648.2 2117.81   709.3 2113.36  760.752126.418   835.5 2145.79
#Mann= 5 ,-1 , 0
       0      .1       0  345.91     .06       0   431.4    .045       0
     460      .1       0  760.75      .1       0
Bank Sta=431.4,460
XS Rating Curve= 0 ,0
Exp/Cntr=0.5,0.3

Type RM Length L Ch R = 1 ,11852   ,27.3,27.3,27.3
XS GIS Cut Line= 2
2414280.66403734 666060.789266972414978.84713403665637.647996245
#Sta/Elev= 30
       0 2177.99    11.6 2172.11    23.3 2168.72    69.9 2149.11     110 2128.33
   212.9 2108.08  294.82 2097.25   302.9 2093.04   320.1 2088.08   339.2 2089.88
   376.6 2088.95     386 2087.92   395.3 2082.48     400 2079.89   407.7 2079.02
     414 2079.51   419.4 2082.64   432.7 2089.68  447.762091.026   474.7 2092.29
   479.5 2095.04   495.1 2108.74   503.8 2113.04  616.192111.858   680.6 2108.22
  703.872109.487  723.322113.934   739.7 2118.62   764.8 2122.88   816.4 2144.25
#Mann= 8 ,-1 , 0
       0      .1       0  294.82     .06       0   395.3    .045       0
   419.4     .06       0  447.76      .1       0  616.19     .05       0
  703.87      .1       0  723.32      .1       0
#XS Ineff= 2 , 0
             386    2088     431            2088
Permanent Ineff=
       F       F
Bank Sta=395.3,419.4
XS Rating Curve= 0 ,0
Exp/Cntr(USF)=0,0
Exp/Cntr=0.5,0.3

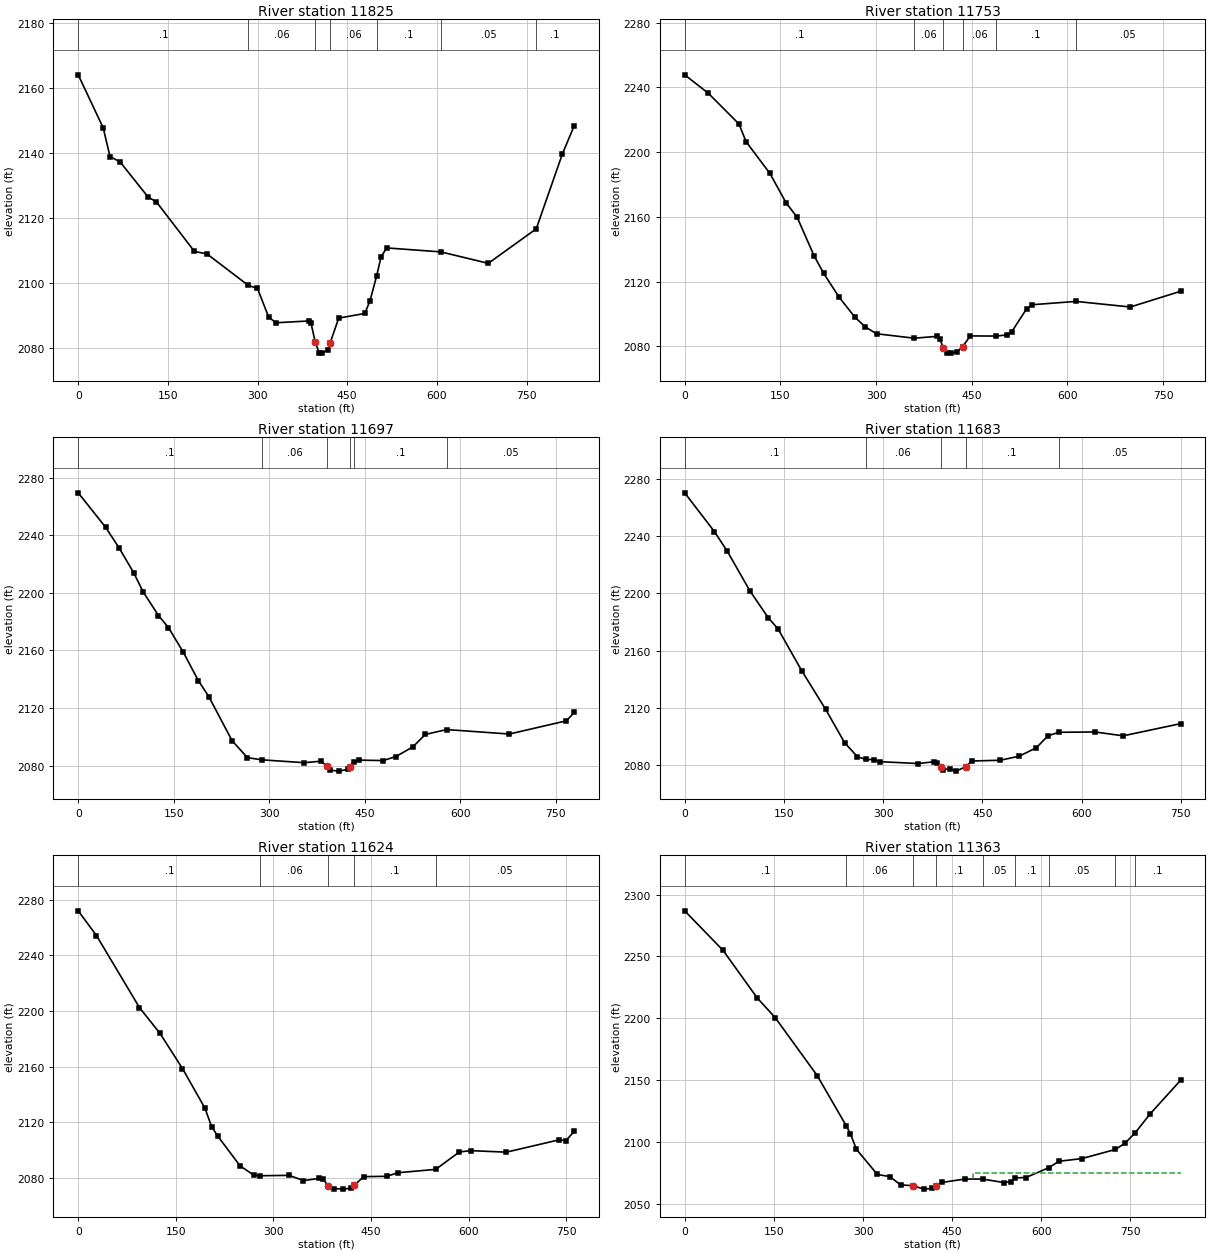
Type RM Length L Ch R = 1 ,11825   ,72.5,72.5,72.5
XS GIS Cut Line= 2
 2414295.1580663666086.733332873 2415002.0760663665652.620332873
#Sta/Elev= 30
       0 2164.13    41.8 2147.77    53.2  2138.9    69.9  2137.3   116.9 2126.43
   130.9 2124.91   194.4 2109.64   215.4 2108.88  284.552099.155   299.9 2098.23
   318.7 2089.32   331.1 2087.64   386.4  2088.2   389.3 2087.62   396.5 2081.64
   403.2  2078.3   407.9 2078.27   417.3 2079.16   421.3 2081.37   435.8 2089.08
   479.4  2090.5   488.2 2094.48  499.312102.137   506.5 2107.91   515.9 2110.73
  606.692109.501   685.9 2105.97  766.162116.604   809.9 2139.71   829.6 2148.39
#Mann= 7 ,-1 , 0
       0      .1       0  284.55     .06       0   396.5    .045       0
   421.3     .06       0  499.31      .1       0  606.69     .05       0
  766.16      .1       0
Bank Sta=396.5,421.3
XS Rating Curve= 0 ,0
Exp/Cntr=0.5,0.3

Type RM Length L Ch R = 1 ,11753   ,55.8,55.8,55.8
XS GIS Cut Line= 3
2414406.41910533666247.0175819512414799.32256243665802.073931862
2414951.54012693665699.294550702
#Sta/Elev= 30
       0 2247.76    36.8 2236.46    85.1 2217.38    96.2 2206.47   133.6 2186.82
     159 2168.66   176.3 2159.72   202.9 2135.87     218 2125.02   242.2 2110.28
     267 2097.94     283 2092.03   300.7 2087.78   359.92085.041   395.1 2086.15
   399.9 2084.59   405.4 2079.08   411.2 2075.99   416.9 2075.81   427.1 2076.73
   435.6 2079.86   447.7 2086.44  488.322086.351   504.8 2087.04   512.5 2088.93
   535.9 2103.22   544.4 2105.71  613.322107.768   698.5 2104.31   777.3 2114.04
#Mann= 6 ,-1 , 0
       0      .1       0   359.9     .06       0   405.4    .045       0
   435.6     .06       0  488.32      .1       0  613.32     .05       0
Bank Sta=405.4,435.6
XS Rating Curve= 0 ,0
Exp/Cntr(USF)=0,0
Exp/Cntr=0.5,0.3

Type RM Length L Ch R = 1 ,11697   ,13.5,13.5,13.5
XS GIS Cut Line= 3
2414498.70904024666307.5604390462414827.36936046665818.264103375
2414981.73623698665707.838105387
#Sta/Elev= 30
       0 2269.42    43.1 2245.47    63.9 2231.42      87 2214.08     102 2200.67
   126.1 2184.23   141.7 2175.91   165.1 2158.77   188.7 2139.07   205.2 2127.94
   241.7 2097.37   265.8 2085.55   288.22084.047   355.1 2082.05   381.5 2083.07
   391.1 2079.54   395.4 2076.89     409 2076.19   423.3 2077.35   427.1 2079.09
  433.562082.553   441.5 2083.84     479 2083.51   499.2 2086.34     526 2093.08
   545.3 2101.66  578.912105.035   677.4 2101.95   767.1 2111.13   779.2  2116.9
#Mann= 6 ,-1 , 0
       0      .1       0   288.2     .06       0   391.1    .045       0
   427.1     .06       0  433.56      .1       0  578.91     .05       0
#XS Ineff= 2 , 0
          380.54 2082.14   435.8          2081.5
Permanent Ineff=
       F       F
Bank Sta=391.1,427.1
XS Rating Curve= 0 ,0
Exp/Cntr(USF)=0,0
Exp/Cntr=0.5,0.3

Type RM Length L Ch R = 1 ,11683   ,59.3,59.3,59.3
XS GIS Cut Line= 4
2414511.04116681666316.3457269542414738.28040912665975.021834298
2414822.39508554665847.6191785282414967.70121577665729.819947922
#Sta/Elev= 30
       0 2270.09      45 2243.03    64.2  2229.5    98.9 2201.47   126.7 2182.72
   141.1  2175.2   176.8 2146.09   213.2 2118.94     242  2095.6   261.2 2085.96
  273.652084.091   286.4 2083.94   295.4  2082.5   353.1  2081.2   376.6 2082.42
     382 2081.63   387.4 2078.57     391 2076.88   400.6 2077.61   410.5 2075.91
   424.6 2078.94   434.2 2082.97   477.3  2083.5   505.8 2086.35   531.7 2092.22
   549.2 2100.57  565.512103.005   620.4 2103.23     663 2100.54   749.8 2109.04
#Mann= 5 ,-1 , 0
       0      .1       0  273.65     .06       0   387.4    .045       0
   424.6      .1       0  565.51     .05       0
Bank Sta=387.4,424.6
XS Rating Curve= 0 ,0
Exp/Cntr=0.5,0.3

Type RM Length L Ch R = 1 ,11624   ,261.1,261.1,261.1
XS GIS Cut Line= 2
2414552.13164571666347.194953462 2414986.6672572665721.411632724
#Sta/Elev= 30
       0 2271.91      28 2254.19    94.1 2202.43   125.7 2183.85   160.2 2158.63
   194.7 2130.19   204.9 2116.97   214.6 2109.97   248.7 2088.74   269.4  2082.2
  279.822081.651     324 2081.93   346.1  2078.2   370.5 2079.73   376.3 2079.08
   384.3 2074.44     393 2072.47   407.3 2072.04   419.2 2072.75     424 2074.83
   438.7 2081.02   474.5 2081.26   490.7  2083.8  549.232086.234   585.5 2098.71
   602.8 2099.68   657.8 2098.59   737.9 2107.35   749.4 2106.96   761.9 2113.49
#Mann= 5 ,-1 , 0
       0      .1       0  279.82     .06       0   384.3    .045       0
     424      .1       0  549.23     .05       0
Bank Sta=384.3,424
XS Rating Curve= 0 ,0
Exp/Cntr(USF)=0,0
Exp/Cntr=0.3,0.1

Type RM Length L Ch R = 1 ,11363   ,300,300,300
XS GIS Cut Line= 3
2414832.02499805666525.622719886     2415001.071      666156.666
     2415150.029      665754.836
#Sta/Elev= 30
       0 2286.84    64.6 2254.89   121.8 2216.68   152.6 2200.42     223 2153.83
  271.852113.297   278.7 2107.02     289 2094.33   324.2 2074.01   345.1 2072.33
   363.2 2065.66   384.3 2064.92   402.4  2062.2   416.3 2062.77   422.2  2065.1
   433.1 2067.63   471.7 2070.34  501.212070.318   537.2 2067.51   548.4 2068.24
  556.182071.263   574.1 2071.57  612.922079.554   629.5 2084.68     668 2086.83
  724.622094.214   740.5 2099.15  757.572107.434   783.1 2122.94   834.4 2150.07
#Mann= 9 ,-1 , 0
       0      .1       0  271.85     .06       0   384.3    .045       0
   422.2      .1       0  501.21     .05       0  556.18      .1       0
  612.92     .05       0  724.62      .1       0  757.57      .1       0
#XS Ineff= 2 , 0
                          485.64          2075.3
Permanent Ineff=
       F       F
Bank Sta=384.3,422.2
XS Rating Curve= 0 ,0
Exp/Cntr=0.3,0.1

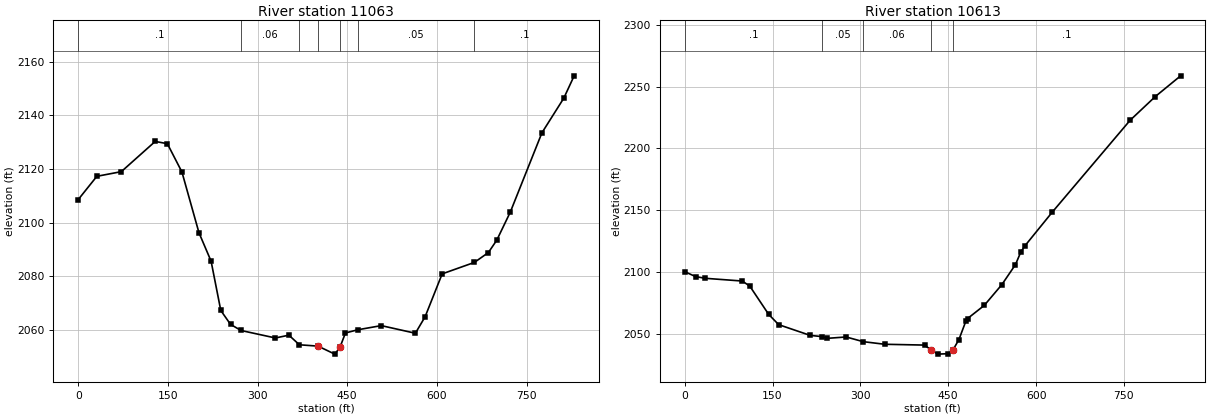
Type RM Length L Ch R = 1 ,11063   ,450,450,450
XS GIS Cut Line= 3
     2415351.834      666589.604     2415276.805       666176.02
 2415200.4548842665773.924033774
#Sta/Elev= 30
       0 2108.64    31.2 2117.32    72.1 2119.05   128.8 2130.31   149.1 2129.47
   173.5 2118.92     202 2096.29   222.3 2085.68   238.5 2067.33   254.8 2062.15
  272.412059.874   329.8 2057.09   352.4 2058.13  369.982054.552   401.2 2054.05
   429.2 2051.07   437.8 2053.58     447 2058.95  467.562060.141     507 2061.69
     564 2058.85   580.3    2065   608.8 2080.97  662.742085.239   686.1 2088.91
   700.2 2093.54   722.8 2103.99   775.7 2133.53   812.3 2146.44   829.6 2154.75
#Mann= 7 ,-1 , 0
       0      .1       0  272.41     .06       0  369.98      .1       0
   401.2    .045       0   437.8      .1       0  467.56     .05       0
  662.74      .1       0
Bank Sta=401.2,437.8
XS Rating Curve= 0 ,0
Exp/Cntr=0.3,0.1

Type RM Length L Ch R = 1 ,10613   ,450,450,450
XS GIS Cut Line= 3
2415389.44274135666544.579960506     2415702.598      666238.945
2416011.80687817665970.846073585
#Sta/Elev= 30
       0 2100.13    18.6 2096.12    35.4 2094.72    98.3 2092.52   111.2 2088.39
   143.5 2065.46   160.5 2057.19   214.2 2048.51   234.52047.493   242.9 2046.09
   275.7 2047.21  304.872043.416   341.6  2041.3   409.8 2040.64     421 2036.55
   432.1 2033.32   449.1 2033.66   457.6 2036.29   468.2 2045.05   480.1 2060.01
   483.1 2062.17   511.5 2072.77   541.5 2089.57   564.8 2105.82   573.8 2115.87
   580.7 2120.88   627.7 2148.35   760.7 2222.78   803.5 2241.89   846.8 2258.71
#Mann= 5 ,-1 , 0
       0      .1       0   234.5     .05       0  304.87     .06       0
     421    .045       0   457.6      .1       0
Bank Sta=421,457.6
XS Rating Curve= 0 ,0
Exp/Cntr=0.3,0.1