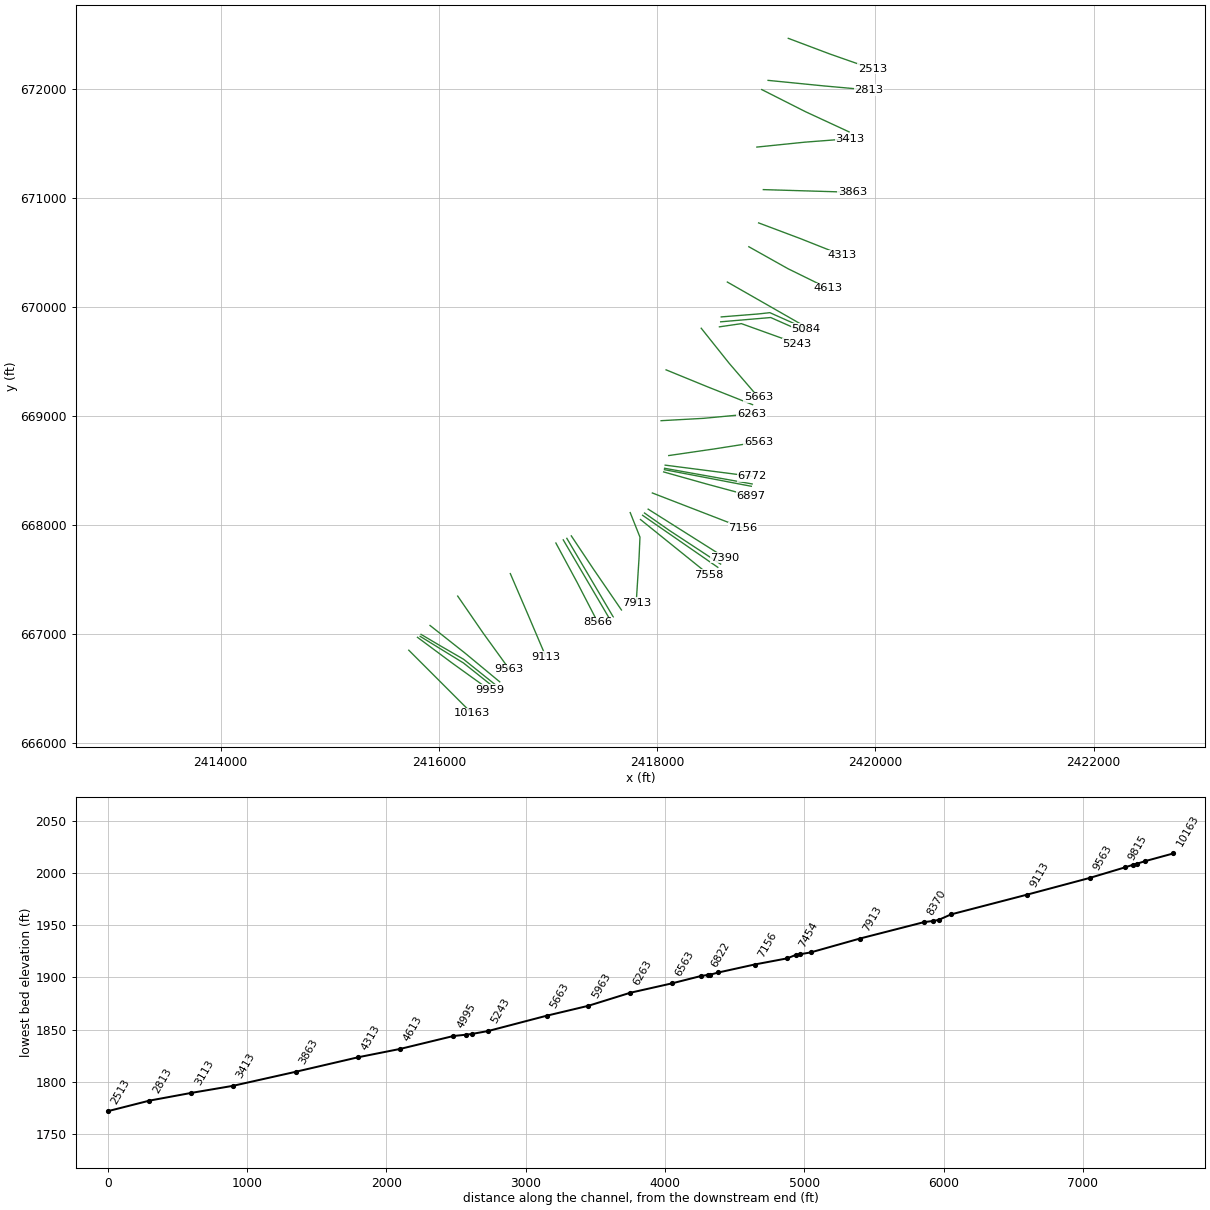
HEC-RAS study BRUSHRN.prj: BRUSHRN

--- BRUSHRN.g02 (geometry) --- (continued)

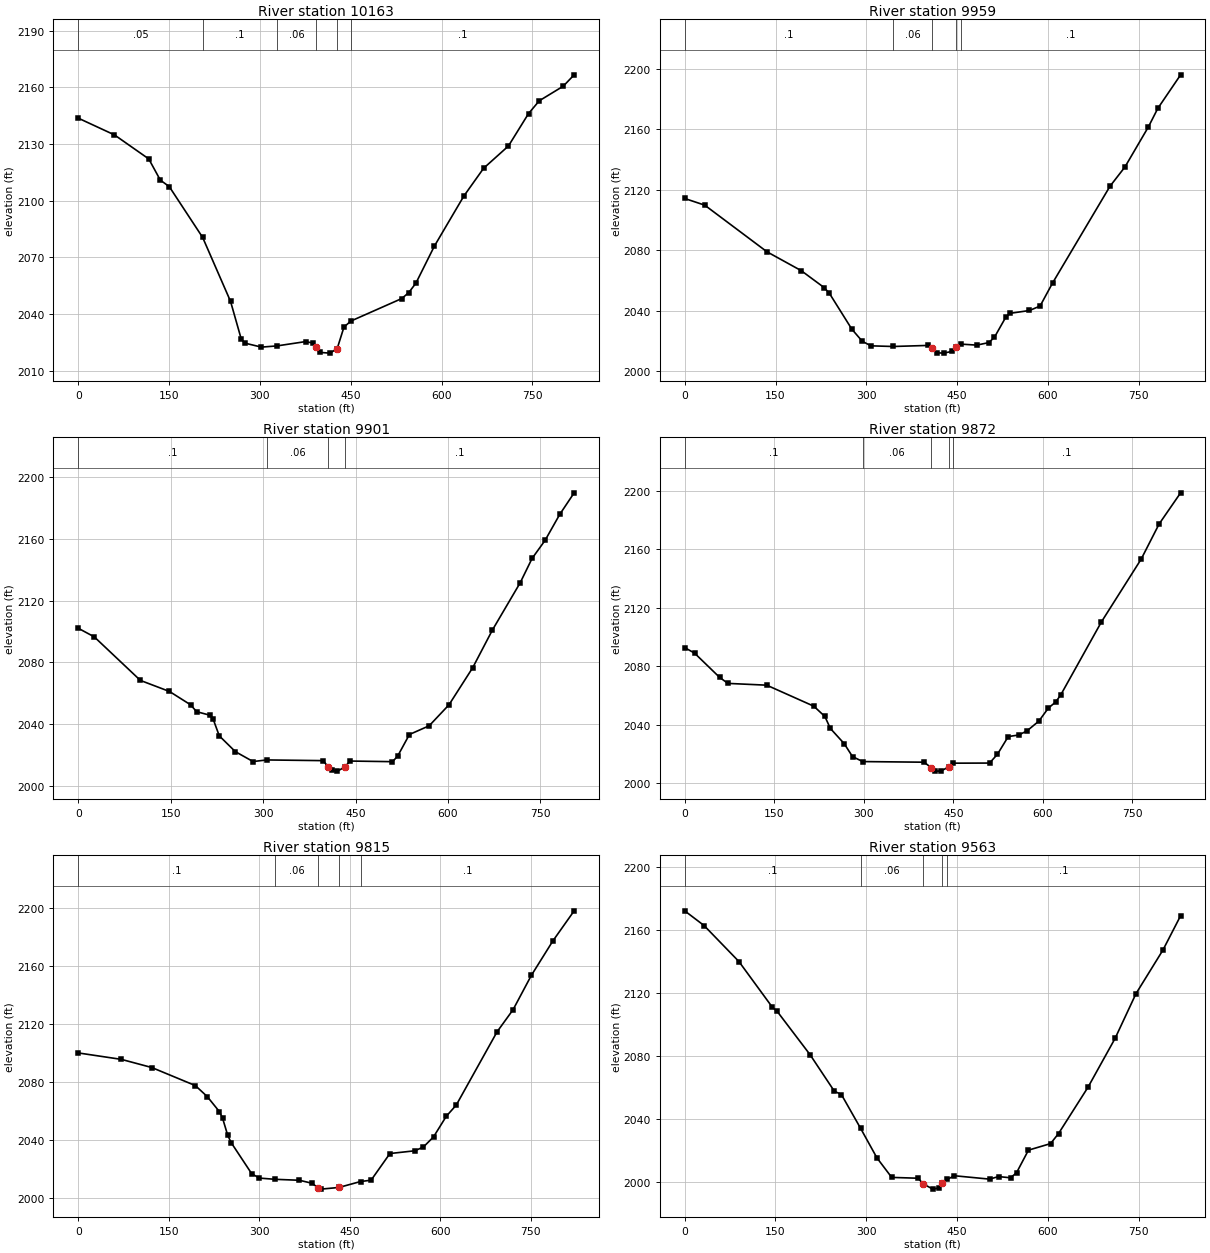
Type RM Length L Ch R = 1 ,10163   ,203.9,203.9,203.9
XS GIS Cut Line= 3
     2415724.407       666852.36     2416013.938      666562.771
      2416303.47      666273.182
#Sta/Elev= 30
       0 2143.66    59.9 2134.77   116.5 2122.06   135.6 2110.84   150.4 2107.39
  205.512080.491   251.6 2046.61   269.2 2026.72   274.9 2024.57   302.5 2022.43
  327.96 2023.06   375.4 2025.35   387.4 2024.61   392.4 2022.24   398.7 2019.64
   415.6 2019.25   427.6 2021.57   438.9 2033.07   450.42036.249   534.4 2048.16
   545.8 2051.28   557.7  2056.3   588.2 2075.91   636.9 2102.43   669.5 2117.12
   710.5 2128.91   743.7 2146.09   761.4 2152.84     801 2160.57     819 2166.58
#Mann= 6 ,-1 , 0
       0     .05       0  205.51      .1       0  327.96     .06       0
   392.4    .045       0   427.6     .06       0   450.4      .1       0
Bank Sta=392.4,427.6
XS Rating Curve= 0 ,0
Exp/Cntr=0.3,0.1

Type RM Length L Ch R = 1 ,9959    ,57.6,57.6,57.6
XS GIS Cut Line= 3
2415804.16004287666970.6328071192416132.98604287666726.480807119
2416465.40004287666487.351807119
#Sta/Elev= 30
       0 2114.17    33.1 2109.75     136 2078.85   192.5 2066.38   230.4 2055.15
     239 2051.36   276.1 2027.62   293.3 2019.63   307.6 2016.62  344.082016.183
   402.2 2016.89   408.9  2015.4   416.3 2012.01   427.7 2011.79   441.3 2012.93
   447.8 2015.63  455.582017.776   482.2 2017.09   502.2 2018.75   511.6 2022.33
     530 2035.38   536.6 2038.09   569.4 2040.01   586.9 2042.96   607.5 2058.19
   702.4 2122.28   727.1 2135.04   765.9 2161.63   781.3 2173.79     819 2196.02
#Mann= 5 ,-1 , 0
       0      .1       0  344.08     .06       0   408.9    .045       0
   447.8     .06       0  455.58      .1       0
Bank Sta=408.9,447.8
XS Rating Curve= 0 ,0
Exp/Cntr=0.5,0.3

Type RM Length L Ch R = 1 ,9901    ,29.3,29.3,29.3
XS GIS Cut Line= 3
 2415828.5929645666979.5858244262416225.88080785666735.100997746
2416490.38809879666524.338216125
#Sta/Elev= 30
       0 2102.02      26 2096.44   100.9 2068.18   148.1 2061.01   182.3 2052.38
   192.1 2047.91   214.3 2045.56   218.6 2043.47   228.9 2032.22     255 2021.99
   283.7 2015.57  305.922016.617   397.5 2016.16   405.3 2012.27   411.1 2009.83
   420.5 2009.36   432.4 2011.94   441.1  2015.9   509.9 2015.49   518.2 2019.01
   537.4 2033.11   569.5 2038.77   601.6 2052.37   640.1 2076.43   672.2 2100.95
   717.2 2131.55   736.4 2147.26   757.6 2159.04   781.3 2175.82   804.7 2189.82
#Mann= 4 ,-1 , 0
       0      .1       0  305.92     .06       0   405.3    .045       0
   432.4      .1       0
#XS Ineff= 2 , 0
           398.2    2014   441.1            2014
Permanent Ineff=
       F       F
Bank Sta=405.3,432.4
XS Rating Curve= 0 ,0
Exp/Cntr(USF)=0,0
Exp/Cntr=0.5,0.3

Type RM Length L Ch R = 1 ,9872    ,56.9,56.9,56.9
XS GIS Cut Line= 4
2415836.45207339 666997.589073392416002.81804852666899.133731863
 2416227.0274956 666769.008790492416522.23862365666532.417218751
#Sta/Elev= 30
       0 2092.84    16.6 2089.03    58.4  2072.5    72.4 2068.33   137.5 2067.11
   216.4 2052.72   234.9 2045.68   244.1 2037.49   267.2 2027.12   281.2 2018.24
  298.222014.828   401.2  2014.4   412.9 2010.69   419.8 2008.36   429.1 2008.29
     443 2011.34  449.172013.732   510.8 2013.81     524 2019.83   542.1 2031.93
   559.8 2033.03   573.4  2035.8   593.3 2042.48   609.4 2051.48   621.7 2055.63
   630.3 2060.63   698.2 2110.41   764.9 2153.44   794.9 2177.45   830.9 2198.75
#Mann= 5 ,-1 , 0
       0      .1       0  298.22     .06       0   412.9    .045       0
     443     .06       0  449.17      .1       0
Bank Sta=412.9,443
XS Rating Curve= 0 ,0
Exp/Cntr=0.5,0.3

Type RM Length L Ch R = 1 ,9815    ,252.4,252.4,252.4
XS GIS Cut Line= 3
2415919.12689625667079.2287190732416239.90889625666825.659719073
2416557.87089625666562.235719073
#Sta/Elev= 30
       0 2099.86    71.5 2095.41   121.9 2089.78   194.1 2077.32   213.7 2069.78
   234.1 2059.27   239.2 2054.83   247.7 2043.04   253.4 2037.97   287.6 2016.41
   300.3 2013.46  326.012012.619   366.6 2011.95   387.3  2009.9   397.2 2006.88
   402.3 2005.84     432 2006.99  467.842011.091   485.3    2012   516.5 2030.41
   557.8 2032.31     572 2034.92   588.8 2041.91     610 2056.18   626.4 2063.83
   694.1 2114.46   720.5 2129.65   750.9 2153.42   786.6 2177.22   821.8 2197.95
#Mann= 5 ,-1 , 0
       0      .1       0  326.01     .06       0   397.2    .045       0
     432     .06       0  467.84      .1       0
Bank Sta=397.2,432
XS Rating Curve= 0 ,0
Exp/Cntr=0.3,0.1

Type RM Length L Ch R = 1 ,9563    ,450,450,450
XS GIS Cut Line= 3
     2416172.645      667348.736     2416404.575      667011.332
     2416644.635      666679.083
#Sta/Elev= 30
       0 2172.14      32 2162.82    89.6    2140   144.9 2110.98   152.7 2108.45
   207.1 2080.96   247.3 2057.76   258.9 2055.69  290.772034.151   317.7 2015.47
     342 2003.14   385.7 2002.62     394 1999.04     410 1995.71     420 1996.47
   425.6 1999.31  433.892001.908   445.7 2004.19   503.7 2002.05   518.5 2003.67
   538.3 2002.89   548.2 2006.08   567.9 2020.42   604.4 2024.56   617.6 2030.93
   666.3 2060.31     711 2091.24   745.5 2119.58     790 2147.22   819.3 2169.04
#Mann= 5 ,-1 , 0
       0      .1       0  290.77     .06       0     394    .045       0
   425.6     .06       0  433.89      .1       0
Bank Sta=394,425.6
XS Rating Curve= 0 ,0
Exp/Cntr=0.3,0.1

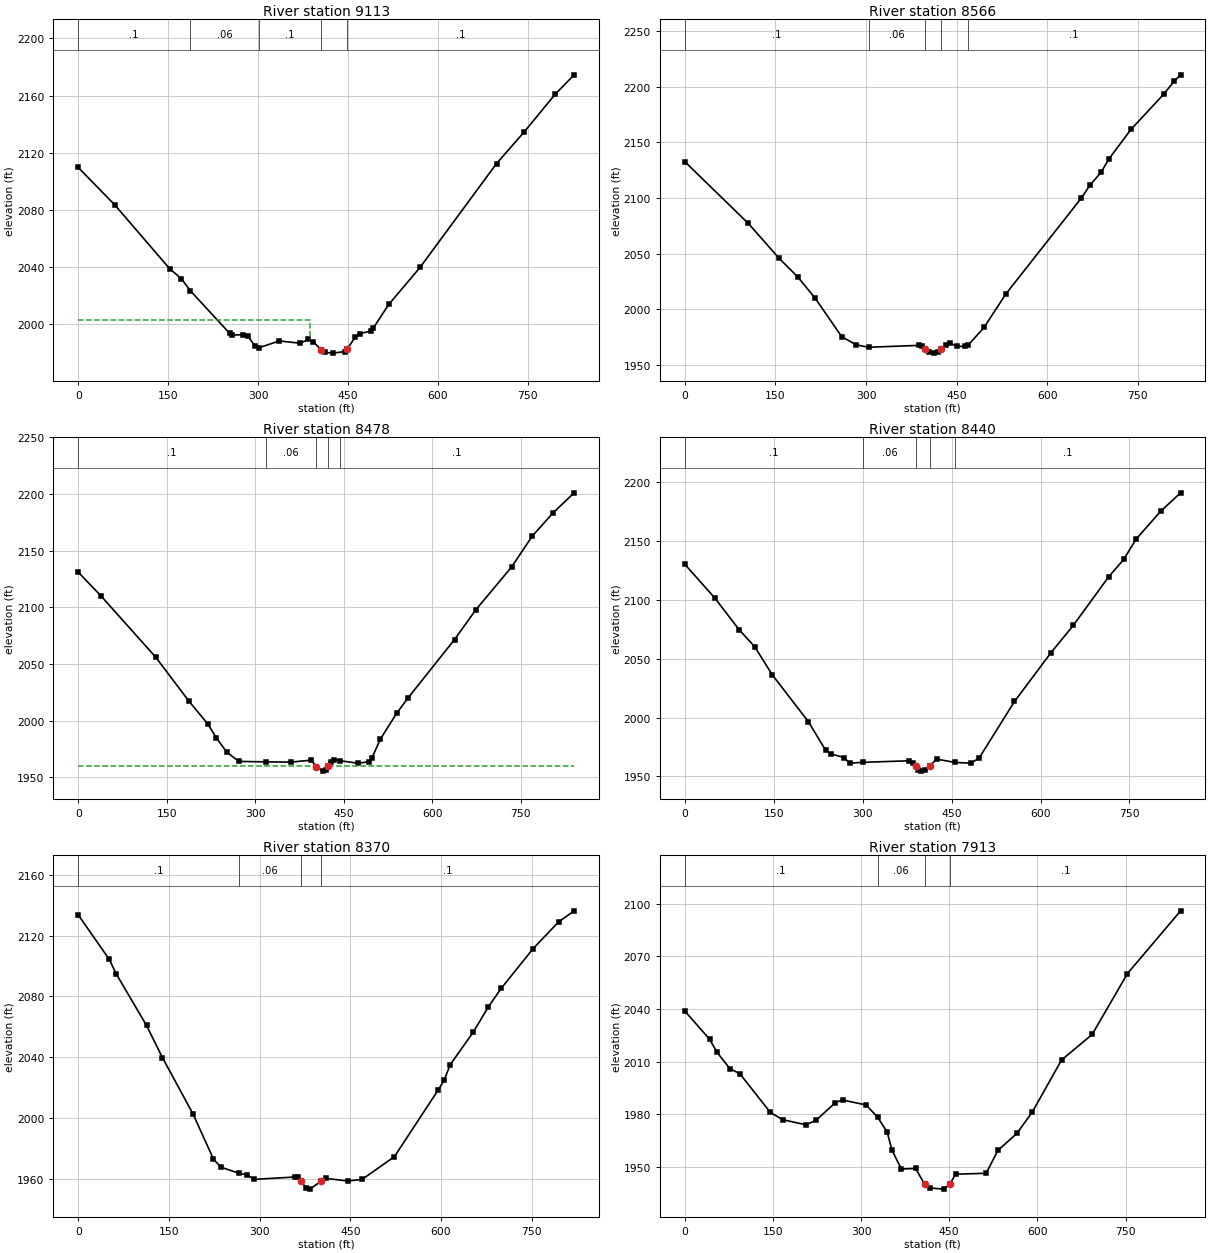
Type RM Length L Ch R = 1 ,9113    ,546.9,546.9,546.9
XS GIS Cut Line= 3
      2416654.76       667554.94     2416820.516      667169.583
     2416980.061      666794.357
#Sta/Elev= 30
       0 2109.64    60.9 2083.45   152.9 2038.57   172.1 2031.78  186.882023.359
   252.7 1993.47     257 1992.28   274.4 1992.51   283.2  1991.3   295.4 1984.37
  302.031983.456   335.3 1988.15   370.2 1986.57   383.7 1989.23   391.9 1987.69
     405 1982.01   411.1 1980.19   425.2 1979.63   444.2 1980.71   448.5 1982.23
   461.5 1990.63   470.2 1993.32   487.6 1995.02     492 1997.02     518 2013.76
   570.2 2039.64   697.7 2112.36   744.1 2134.61   795.3 2160.77   827.2 2174.49
#Mann= 5 ,-1 , 0
       0      .1       0  186.88     .06       0  302.03      .1       0
     405    .045       0   448.5      .1       0
#XS Ineff= 2 , 0
          387.06 2003.07
Permanent Ineff=
       F       F
Bank Sta=405,448.5
XS Rating Curve= 0 ,0
Exp/Cntr=0.3,0.1

Type RM Length L Ch R = 1 ,8566    ,88.3,88.3,88.3
XS GIS Cut Line= 3
2417072.21551223667835.4827914552417266.44451223667475.428791455
2417455.39251223667109.914791455
#Sta/Elev= 30
       0 2132.84   105.2 2077.28   155.8 2046.11     187 2029.17     216 2009.91
   259.7 1975.51   283.4 1968.15  304.171965.882     387 1967.57     392 1967.28
   397.9 1964.21   403.8 1961.27   412.7 1960.61   418.7 1961.19   424.6 1964.26
   432.2 1968.07   439.4 1969.41   450.2 1966.82   463.7 1966.59  468.491967.469
   495.3 1983.66   531.4 2013.79   656.1 2099.86   670.9 2111.83   688.8 2123.01
   702.4 2135.48   738.4 2161.69   792.4 2193.28   810.4  2205.3   820.6 2210.81
#Mann= 5 ,-1 , 0
       0      .1       0  304.17     .06       0   397.9    .045       0
   424.6     .06       0  468.49      .1       0
Bank Sta=397.9,424.6
XS Rating Curve= 0 ,0
Exp/Cntr=0.5,0.3

Type RM Length L Ch R = 1 ,8478    ,37.4,37.4,37.4
XS GIS Cut Line= 2
2417139.79164695667864.3030813782417564.82992322667139.513293467
#Sta/Elev= 30
       0 2131.07    38.3 2110.24   131.5 2055.84   187.1 2017.44   219.6 1996.92
   234.1 1984.66   251.6  1972.1   272.1 1963.92  317.361963.529   359.8 1963.29
   394.9 1965.02   403.6  1959.2   414.3 1955.34     419 1956.35   423.6 1959.52
   428.2 1963.82   432.8 1965.52  443.261964.549   474.6 1962.25   493.2 1963.78
   497.8 1967.22   511.7  1983.4   539.5 2006.45   559.3 2020.31   637.5 2071.53
     674 2098.06   734.3  2135.7   769.3  2162.9   803.8 2183.05   840.2  2201.1
#Mann= 5 ,-1 , 0
       0      .1       0  317.36     .06       0   403.6    .045       0
   423.6     .06       0  443.26      .1       0
#XS Ineff= 2 , 0
           403.6    1960   423.6            1960
Permanent Ineff=
       F       F
Bank Sta=403.6,423.6
XS Rating Curve= 0 ,0
Exp/Cntr(USF)=0,0
Exp/Cntr=0.5,0.3

Type RM Length L Ch R = 1 ,8440    ,70.3,70.3,70.3
XS GIS Cut Line= 2
2417172.57696853667878.353933486 2417597.6152448667158.247762945
#Sta/Elev= 30
       0 2130.42    50.5 2101.79    91.7 2074.73     118 2060.23     148  2036.1
   208.6 1996.44   237.8 1972.03   246.5 1969.07   268.8 1965.93   278.1 1961.17
  300.991961.909   377.7 1963.17   384.9 1961.66   389.9 1958.35   394.2  1955.3
   398.8  1954.4   405.6 1955.21   412.8 1958.59   424.7 1964.61  456.271961.756
   482.4 1961.17   496.4 1965.46   556.1 2013.61   617.1 2054.77   655.5 2078.48
   714.7 2119.51   740.2 2134.38   761.1 2151.66   802.9 2175.56   836.2 2191.05
#Mann= 5 ,-1 , 0
       0      .1       0  300.99     .06       0   389.9    .045       0
   412.8     .06       0  456.27      .1       0
Bank Sta=389.9,412.8
XS Rating Curve= 0 ,0
Exp/Cntr(USF)=0,0
Exp/Cntr=0.5,0.3

Type RM Length L Ch R = 1 ,8370    ,457.1,457.1,457.1
XS GIS Cut Line= 3
2417213.50868156667900.9455947152417416.42057145667596.628206498
2417673.08584561667221.582782883
#Sta/Elev= 30
       0 2133.66    51.4 2104.35    62.9 2094.79     113 2060.83   139.2 2039.76
     190 2002.48   223.6 1972.95     236 1967.55  265.761963.585   279.3 1962.48
   290.8 1959.53   358.2 1961.09   362.9 1960.92   368.7 1958.44     377 1953.81
   383.1 1953.11   401.8 1958.35     409 1960.22   445.4 1958.47   469.4 1959.47
     523 1974.51   595.7  2018.6   605.4 2024.98   615.1 2034.98   653.6 2056.62
   678.1 2072.94   699.6  2085.3   752.3 2111.42   794.4 2128.99   820.2 2136.32
#Mann= 4 ,-1 , 0
       0      .1       0  265.76     .06       0   368.7    .045       0
   401.8      .1       0
Bank Sta=368.7,401.8
XS Rating Curve= 0 ,0
Exp/Cntr=0.3,0.1

Type RM Length L Ch R = 1 ,7913    ,354.6,354.6,354.6
XS GIS Cut Line= 4
2417753.44735345668114.2657901082417842.93445627667889.198448656
     2417834.258      667696.308     2417808.484      667288.675
#Sta/Elev= 30
       0 2038.92    42.4 2022.76    55.3 2015.24    76.8 2006.08      94 2003.09
   145.7 1981.12   166.8 1976.94   205.9 1974.13   223.2 1976.53   256.5 1986.73
   268.5 1988.18   308.6 1985.37  328.541978.262   344.6 1969.83   352.6 1959.64
   368.6 1948.87   392.7 1949.23     4081940.383   416.7 1938.12   440.7 1937.44
   451.2 1940.23   460.8 1945.93   512.9 1946.47   532.9 1959.49     565 1969.11
   591.4 1981.33   641.1 2010.93   693.2  2025.5   753.3 2060.19   843.7 2095.88
#Mann= 4 ,-1 , 0
       0      .1       0  328.54     .06       0     408    .045       0
   451.2      .1       0
Bank Sta=408,451.2
XS Rating Curve= 0 ,0
Exp/Cntr=0.3,0.1

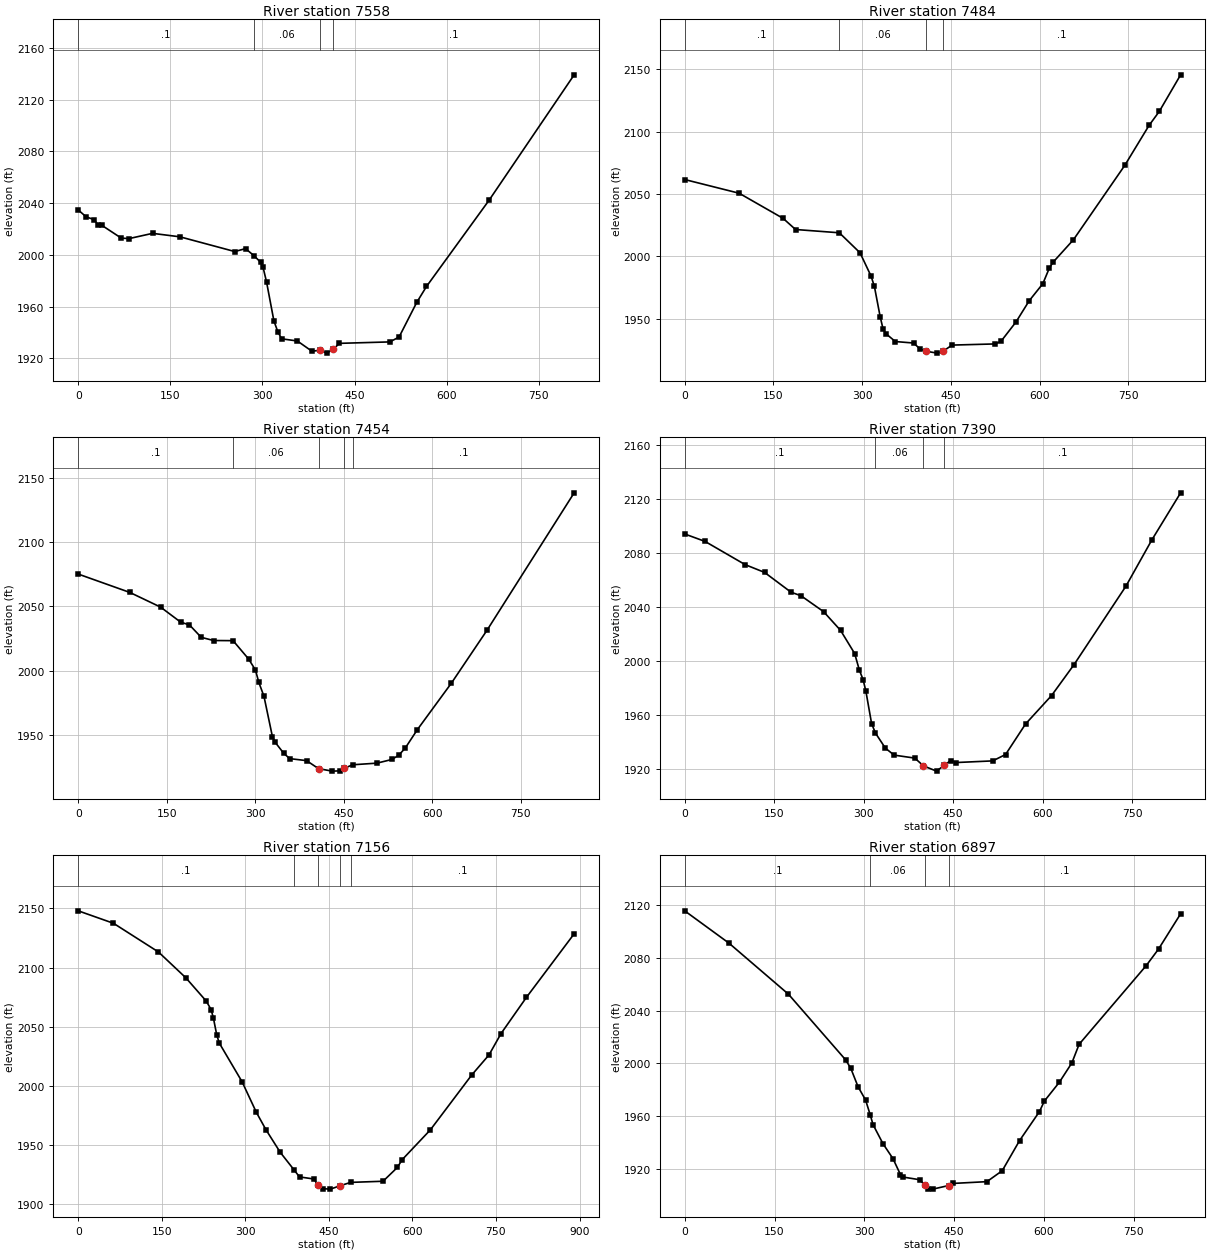
Type RM Length L Ch R = 1 ,7558    ,74.4,74.4,74.4
XS GIS Cut Line= 2
2417847.56667592 668050.929410172418476.34230776667543.927829934
#Sta/Elev= 30
       0 2034.76    12.8 2029.42    25.6 2027.27    31.9 2023.46    38.3 2022.89
    70.2 2012.93    82.9 2012.59   121.1 2016.63   165.7 2013.95     255 2002.57
   272.5 2004.83  286.631999.219     297 1994.32     301 1990.43   306.7 1979.13
   318.7    1949   325.1 1940.55   331.4 1935.11   356.9 1933.45   380.6 1925.54
   394.11926.272   404.9 1924.06   415.2 1926.99   425.4 1931.62   507.6 1932.73
   522.6 1936.53   551.3 1963.23   567.2 1975.56   669.2 2042.27   807.7 2139.15
#Mann= 4 ,-1 , 0
       0      .1       0  286.63     .06       0   394.1    .045       0
   415.2      .1       0
Bank Sta=394.1,415.2
XS Rating Curve= 0 ,0
Exp/Cntr(USF)=0,0
Exp/Cntr=0.5,0.3

Type RM Length L Ch R = 1 ,7484    ,29.5,29.5,29.5
XS GIS Cut Line= 2
2417867.05189778668089.5636860772418556.38498097 667612.49264555
#Sta/Elev= 30
       0 2061.62    92.1 2050.62   166.4 2030.45   187.4 2021.53  261.42  2018.9
   296.4 2002.85   315.1  1984.1   320.7 1975.82   330.4 1951.69   335.2    1942
   340.1    1938   356.1 1931.66   386.9 1930.47   398.4 1925.47   408.2 1923.84
   427.2 1922.37   437.4  1924.1     452 1928.82     525 1929.75   534.7 1931.84
     560 1947.34   582.4 1964.41   605.4 1978.06   616.2 1990.38   622.3 1995.08
   657.2 2013.37   743.9 2072.96   784.9 2104.99   802.3  2116.3   838.3  2145.6
#Mann= 4 ,-1 , 0
       0      .1       0  261.42     .06       0   408.2    .045       0
   437.4      .1       0
#XS Ineff= 2 , 0
           408.2    1923   437.4            1923
Permanent Ineff=
       F       F
Bank Sta=408.2,437.4
XS Rating Curve= 0 ,0
Exp/Cntr(USF)=0,0
Exp/Cntr=0.5,0.3

Type RM Length L Ch R = 1 ,7454    ,63.9,63.9,63.9
XS GIS Cut Line= 3
2417884.43060005668110.5658913482418111.05721806667951.650975618
2418582.00720867667642.358939653
#Sta/Elev= 30
       0  2075.1    87.6 2060.78   139.6 2049.38   173.6 2037.69   188.5 2035.52
   208.4 2025.89   229.3 2023.41  262.362023.296   288.7 2009.01   300.2 2000.53
     306 1990.81   314.7 1980.01   329.1 1948.43   333.8 1944.17   348.2 1935.67
   358.3 1931.55   386.9 1929.98   407.1 1923.76   430.2 1921.82   443.9 1922.02
   450.4 1923.93  464.871926.758   506.1 1928.03   531.3 1930.87   542.9 1934.14
     554 1939.72   574.6 1954.11   632.4 1990.37   692.8 2031.56   840.2 2138.28
#Mann= 5 ,-1 , 0
       0      .1       0  262.36     .06       0   407.1    .045       0
   450.4     .06       0  464.87      .1       0
Bank Sta=407.1,450.4
XS Rating Curve= 0 ,0
Exp/Cntr=0.5,0.3

Type RM Length L Ch R = 1 ,7390    ,234.2,234.2,234.2
XS GIS Cut Line= 2
2417917.95103694668146.0328628652418620.49364235667702.260117116
#Sta/Elev= 30
       0 2094.02    34.1 2088.51   101.4 2071.29   133.8 2065.57   178.2 2050.89
   194.9 2048.27   232.8 2036.47   261.2 2022.62   284.8 2005.49   292.8 1993.07
     299 1986.09   303.7 1977.41   313.2 1953.58  319.681946.556   336.3 1935.39
     351 1930.23   385.6 1928.03   400.1 1922.26     422 1918.38   434.9 1922.67
   445.7 1926.25   455.2 1924.75   516.1 1925.96   537.7 1930.69   571.2 1953.32
   614.7 1974.33   652.4 1997.25   739.4 2055.38   782.8 2089.63     831 2124.49
#Mann= 4 ,-1 , 0
       0      .1       0  319.68     .06       0   400.1    .045       0
   434.9      .1       0
Bank Sta=400.1,434.9
XS Rating Curve= 0 ,0
Exp/Cntr(USF)=0,0
Exp/Cntr=0.3,0.1

Type RM Length L Ch R = 1 ,7156    ,259.3,259.3,259.3
XS GIS Cut Line= 2
 2417956.3406332668294.3330361862418786.73507078667973.097276968
#Sta/Elev= 30
       0 2147.97    63.3 2137.43   144.1 2113.13   193.2 2091.31   229.9 2071.57
   238.5 2064.47   242.8 2057.05   248.8 2042.76   253.4 2035.96   294.2 2003.32
   319.9 1977.39   337.1 1962.72   362.8 1943.56  387.651928.668   397.3 1922.81
   422.9 1921.06   431.3 1915.55     440 1912.82   452.8 1912.47   470.1 1915.32
  489.161918.177   547.3 1919.14     573 1930.82   581.6 1937.38   632.3 1962.65
   706.5 2009.05   737.5 2026.03   759.1  2044.1   804.6 2074.67   890.4 2128.52
#Mann= 5 ,-1 , 0
       0      .1       0  387.65     .06       0   431.3    .045       0
   470.1     .06       0  489.16      .1       0
Bank Sta=431.3,470.1
XS Rating Curve= 0 ,0
Exp/Cntr(USF)=0,0
Exp/Cntr=0.3,0.1

Type RM Length L Ch R = 1 ,6897    ,57.1,57.1,57.1
XS GIS Cut Line= 3
2418059.95475554668487.3783207212418455.22775554668376.134320721
2418858.39176519668267.287229049
#Sta/Elev= 30
       0  2115.5      74 2091.02   173.3 2052.38   268.6 2002.77   277.2 1996.48
   289.6 1982.27   302.1 1972.28  309.881960.975   314.6  1953.6   331.2 1939.17
   347.8 1927.94   360.3 1915.85   364.4 1913.97   393.5 1911.85   400.5 1907.61
     406 1904.98   414.3 1904.81   440.6 1907.51   447.4 1909.11   504.7 1910.47
   530.3 1918.75   559.3 1941.59   592.4 1963.48   600.7 1971.49   625.6 1985.67
   646.6 2000.36   658.7 2014.47   770.6 2073.95   791.3 2086.54   828.2 2113.24
#Mann= 4 ,-1 , 0
       0      .1       0  309.88     .06       0   400.5    .045       0
   440.6      .1       0
Bank Sta=400.5,440.6
XS Rating Curve= 0 ,0
Exp/Cntr=0.5,0.3

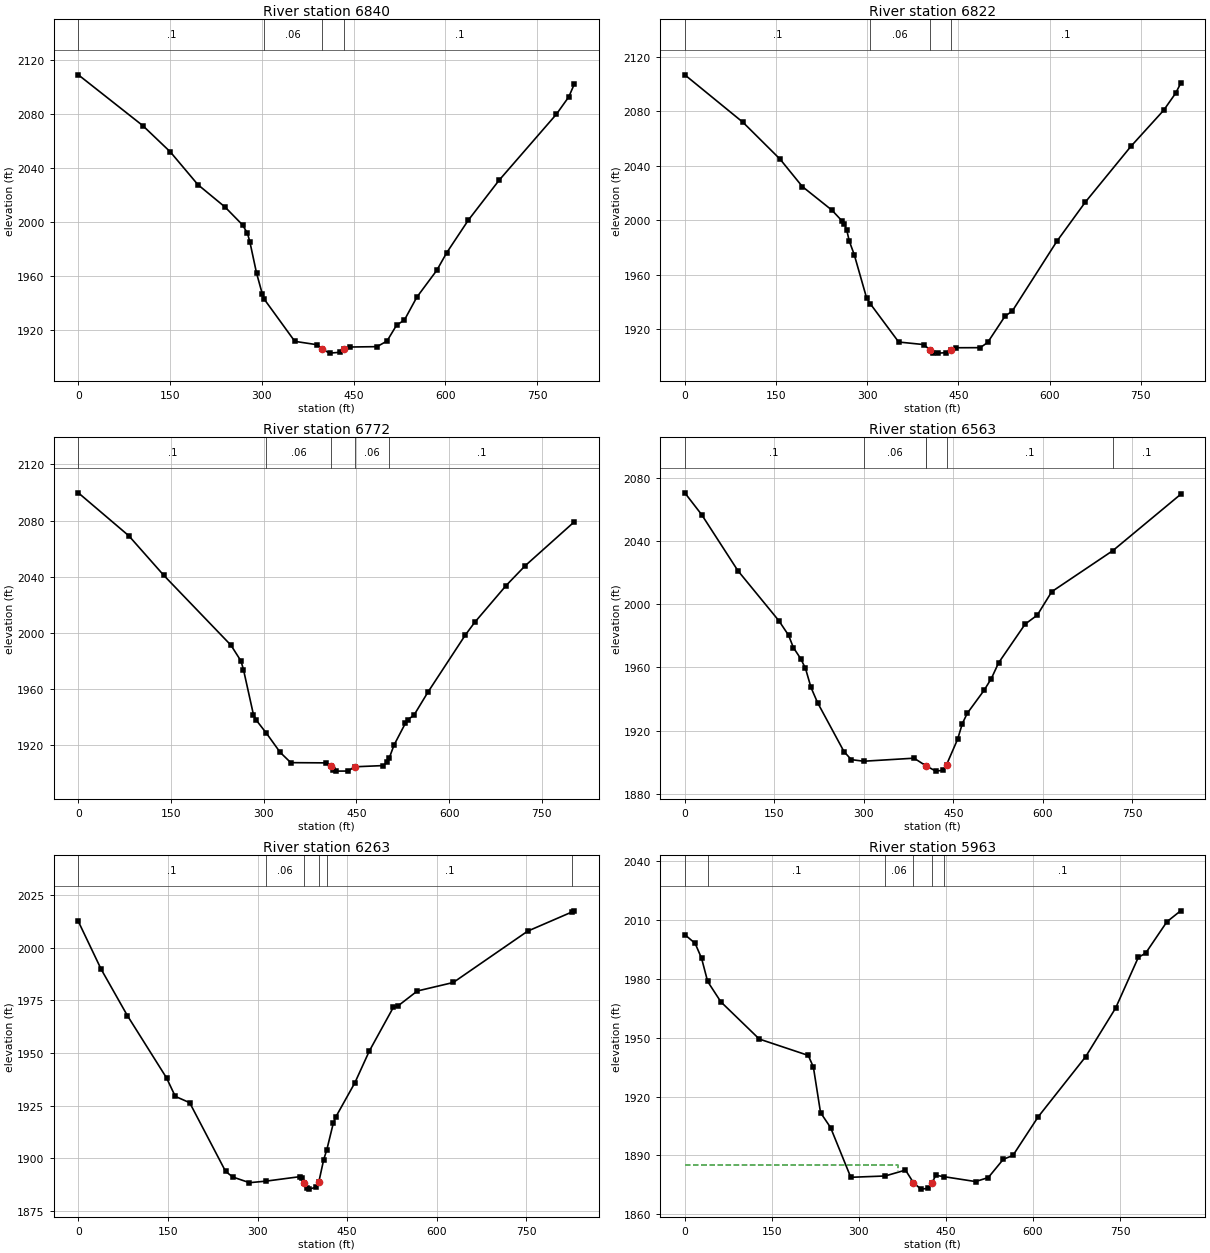
Type RM Length L Ch R = 1 ,6840    ,17.7,17.7,17.7
XS GIS Cut Line= 2
 2418067.1523154668508.081664268 2418863.3672682668355.864099762
#Sta/Elev= 30
       0 2109.31   105.5 2071.56   150.3 2052.15   195.5 2027.79   239.9 2011.17
   268.4 1997.95   276.5 1991.72   280.6    1985   291.3 1962.27   300.9 1946.45
  304.211942.622   353.9 1911.52   390.4 1909.01   398.7 1905.65   410.9 1902.78
   427.2 1903.38   434.9 1905.82   443.5 1907.31   488.3 1907.59   504.6 1911.74
   520.3 1923.54   533.1 1927.34   553.4  1944.3     586 1964.22   602.3 1977.33
   637.4 2001.35   687.8 2031.03   781.5 2080.03   801.9    2093   810.6 2102.21
#Mann= 4 ,-1 , 0
       0      .1       0  304.21     .06       0   398.7    .045       0
   434.9      .1       0
#XS Ineff= 2 , 0
           398.7    1904   434.9            1904
Permanent Ineff=
       F       F
Bank Sta=398.7,434.9
XS Rating Curve= 0 ,0
Exp/Cntr(USF)=0,0
Exp/Cntr=0.5,0.3

Type RM Length L Ch R = 1 ,6822    ,50.3,50.3,50.3
XS GIS Cut Line= 2
2418068.44716485668520.9414566232418871.17104608 668377.12873716
#Sta/Elev= 30
       0 2106.76    95.8 2071.86   156.8 2044.81   193.3 2024.76   242.1 2007.39
   258.8 1999.41   262.4 1997.41   266.5 1992.53   270.5 1984.77   278.7 1974.76
     299 1943.01  304.911938.818   351.8 1910.65   393.2 1908.77   403.5 1904.69
   408.7 1902.69   416.8  1902.5     429 1902.81   437.1 1904.84   445.3 1906.45
   485.9 1906.51   498.1 1910.31   526.6 1929.57   538.7 1933.41   611.9 1984.55
   658.7  2013.3   733.8  2054.3   787.5 2080.68   807.3 2093.26   815.5 2100.42
#Mann= 4 ,-1 , 0
       0      .1       0  304.91     .06       0   403.5    .045       0
   437.1      .1       0
Bank Sta=403.5,437.1
XS Rating Curve= 0 ,0
Exp/Cntr(USF)=0,0
Exp/Cntr=0.5,0.3

Type RM Length L Ch R = 1 ,6772    ,208.9,208.9,208.9
XS GIS Cut Line= 2
2418073.73045917668549.7053137152418869.46534118668447.274601846
#Sta/Elev= 30
       0 2099.76    81.7 2069.14   138.1 2041.04     247 1991.14   263.2 1979.89
   267.2 1973.82   283.3 1941.78   287.4 1938.03  304.421928.403   326.6  1914.8
   343.8 1907.47   400.3 1907.31   408.4 1904.73   412.4 1902.16   416.4 1901.43
   436.6 1901.49   446.9 1904.51     493 1905.38   500.1 1907.73  503.161910.817
   510.8 1919.98   529.3 1935.61   533.4 1938.21     543 1941.23   565.6 1957.65
   626.1 1998.36   641.3 2007.41   692.2  2033.7   722.9 2047.73   802.3 2079.01
#Mann= 5 ,-1 , 0
       0      .1       0  304.42     .06       0   408.4    .045       0
   446.9     .06       0  503.16      .1       0
Bank Sta=408.4,446.9
XS Rating Curve= 0 ,0
Exp/Cntr(USF)=0,0
Exp/Cntr=0.3,0.1

Type RM Length L Ch R = 1 ,6563    ,300,300,300
XS GIS Cut Line= 3
      2418106.71668637.572874555     2418525.249      668698.614
     2418928.072      668761.803
#Sta/Elev= 30
       0 2070.41    28.3 2056.57      89 2021.12   157.7 1989.45   173.9 1980.26
   181.9  1972.5   194.1 1965.54   202.2 1959.33   211.4  1947.3   222.4 1937.69
   266.8 1906.64     279 1901.61  299.651900.602   384.1 1902.53  403.791897.768
   404.3  1897.7   420.4 1894.34   432.6 1894.86   438.5 1898.38   456.9 1914.35
     465 1924.39   473.1 1930.86   501.3 1945.41   513.6 1952.92   525.7 1962.84
   570.2 1987.35   590.5 1993.02   614.8 2007.87  717.232033.864   830.7 2069.44
#Mann= 6 ,-1 , 0
       0      .1       0  299.65     .06       0  403.79      .1       0
   404.3    .045       0   438.5      .1       0  717.23      .1       0
Bank Sta=404.3,438.5
XS Rating Curve= 0 ,0
Exp/Cntr=0.3,0.1

Type RM Length L Ch R = 1 ,6263    ,300,300,300
XS GIS Cut Line= 3
2418036.66400965668957.265265365     2418427.489      668979.087
     2418864.198      669020.282
#Sta/Elev= 30
       0 2012.61    38.1 1989.92    82.2 1967.77   147.7 1938.18   162.3  1929.4
   186.4 1926.39   246.5 1893.73   258.5 1891.05   286.5 1888.34  314.091889.077
   370.7  1891.2   374.7 1890.48   378.1 1887.99   382.7  1885.7   386.7 1885.28
   398.7 1886.28   402.7  1888.8   410.8 1899.33  416.011904.022   426.8 1916.58
   430.9 1919.54     463 1935.88   487.1 1950.93   527.3  1971.7   535.3 1972.45
   567.5 1979.52   627.7 1983.56   752.3 2007.99  826.532017.113   830.1 2017.65
#Mann= 6 ,-1 , 0
       0      .1       0  314.09     .06       0   378.1    .045       0
   402.7     .06       0  416.01      .1       0  826.53      .1       0
Bank Sta=378.1,402.7
XS Rating Curve= 0 ,0
Exp/Cntr=0.3,0.1

Type RM Length L Ch R = 1 ,5963    ,300,300,300
XS GIS Cut Line= 3
2418082.31832517669423.554556324     2418459.793      669268.927
     2418874.835      669104.345
#Sta/Elev= 30
       0 2002.65    17.8 1998.19    28.9 1990.59   39.391978.739    62.2 1968.33
   128.4 1949.36   212.8 1941.01   221.6 1935.01   233.9 1911.82   251.2  1904.2
     286 1878.82  345.261879.486   380.3  1882.5   393.8 1876.15   406.8 1872.78
   419.7 1873.17  426.11 1876.08   432.6 1879.84  447.121879.108   501.1 1876.64
     523 1878.69   548.8    1888   565.4 1889.96     609  1909.7   690.8 1940.38
   742.4 1965.19   781.5 1991.05   794.1 1993.18   830.8 2009.23   854.4  2014.8
#Mann= 6 ,-1 , 0
       0     .05       0   39.39      .1       0  345.26     .06       0
   393.8    .045       0  426.11     .06       0  447.12      .1       0
#XS Ineff= 2 , 0
          366.69 1884.85
Permanent Ineff=
       F       F
Bank Sta=393.8,426.11
XS Rating Curve= 0 ,0
Exp/Cntr=0.3,0.1

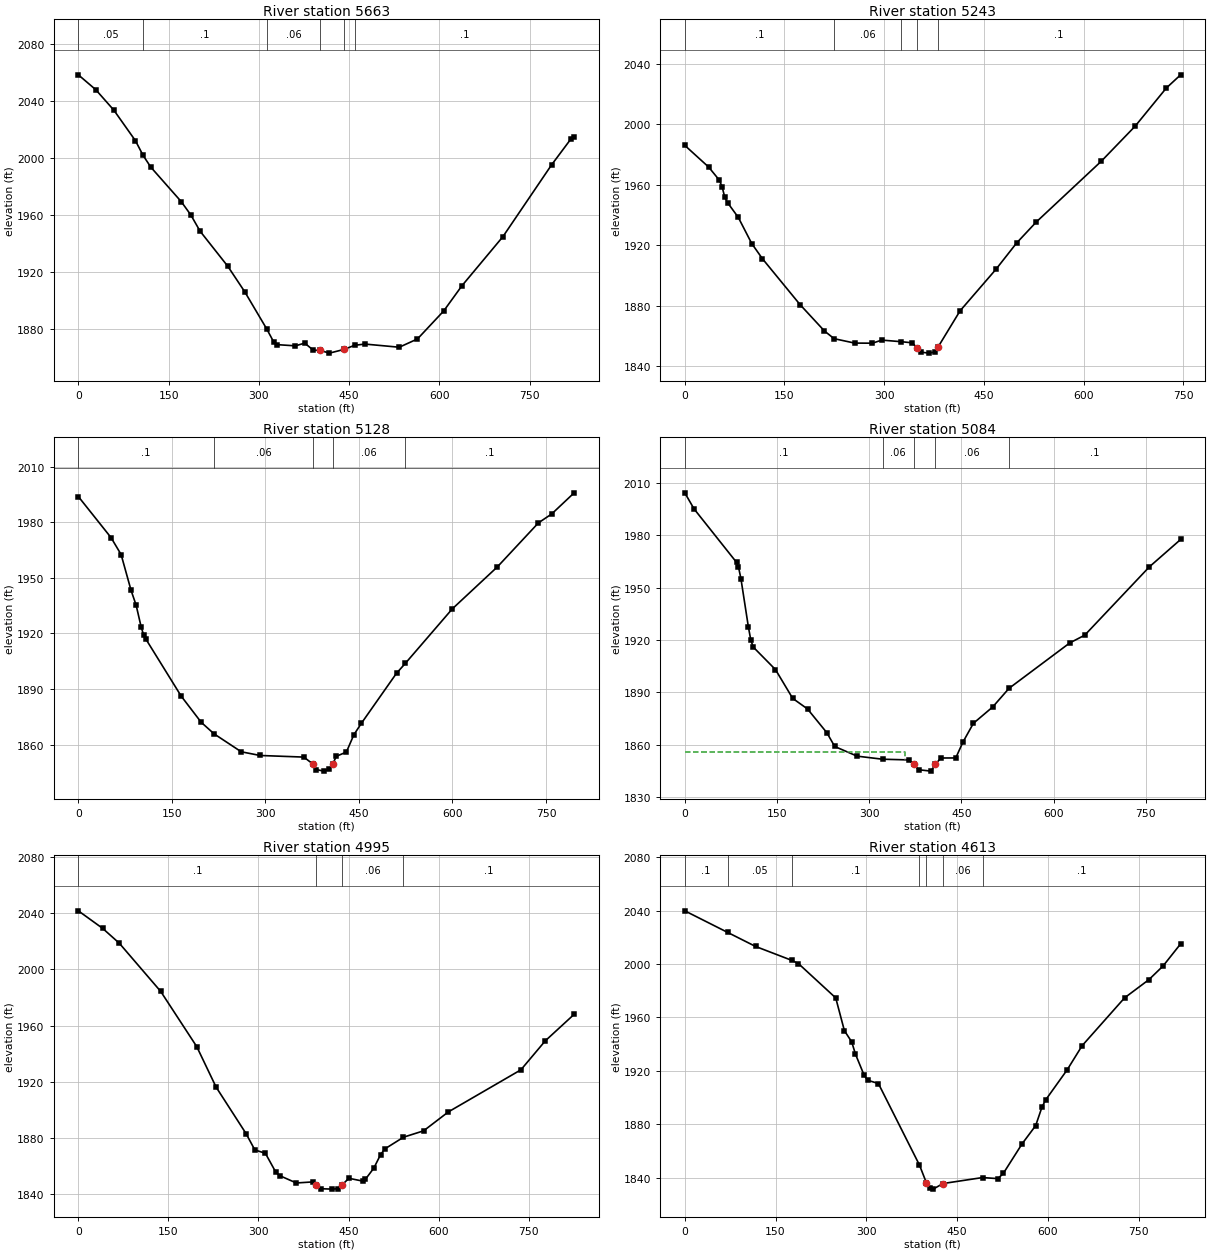
Type RM Length L Ch R = 1 ,5663    ,419.5,419.5,419.5
XS GIS Cut Line= 3
2418404.27316356669805.082674827     2418661.249      669482.493
     2418929.418      669170.573
#Sta/Elev= 30
       0 2058.61    28.9  2048.2    59.1 2033.75    94.9 2012.35  107.512002.112
   120.4  1993.8   170.9 1969.63   186.9 1960.24   202.2 1948.88   248.3 1924.22
   276.6 1906.22     3131880.193     325 1870.74   330.1 1869.18   360.8 1868.33
   376.1 1870.26   390.4 1865.28   401.7 1865.12   417.2 1863.22   441.6 1865.84
  458.951868.718   476.1 1869.58   533.2 1867.36   563.5 1873.19   607.1 1892.85
   637.3  1910.5   705.4 1944.98   786.4 1995.47   818.1 2013.41   823.8 2015.09
#Mann= 6 ,-1 , 0
       0     .05       0  107.51      .1       0     313     .06       0
   401.7    .045       0   441.6     .06       0  458.95      .1       0
Bank Sta=401.7,441.6
XS Rating Curve= 0 ,0
Exp/Cntr=0.3,0.1

Type RM Length L Ch R = 1 ,5243    ,115.8,115.8,115.8
XS GIS Cut Line= 3
2418571.12673008669818.0901836272418772.52227696669847.362792186
2419283.03657023669663.530810436
#Sta/Elev= 30
       0 1985.92      36 1971.55    52.2 1962.79    56.2 1958.38    60.2 1951.55
    64.3 1948.08    80.5 1938.29   100.7 1921.03   116.8 1910.97   173.4 1880.63
   210.1 1863.19  224.661858.093   255.6 1855.17   282.4  1855.1   296.3 1857.15
   325.71856.083   341.9 1855.37   349.4 1852.22   354.7 1849.21   367.4 1848.53
   375.9 1849.25   380.7 1852.28   414.2 1876.49   468.2 1903.96   499.4 1921.41
     529  1935.3   626.8 1975.48   677.8 1998.69   724.5 2023.82   746.1 2032.59
#Mann= 5 ,-1 , 0
       0      .1       0  224.66     .06       0   325.7      .1       0
   349.4    .045       0   380.7      .1       0
Bank Sta=349.4,380.7
XS Rating Curve= 0 ,0
Exp/Cntr(USF)=0,0
Exp/Cntr=0.5,0.3

Type RM Length L Ch R = 1 ,5128    ,44,44,44
XS GIS Cut Line= 3
2418582.40716748669864.1194965062419040.92098769669903.370565921
2419347.26469078669767.744715946
#Sta/Elev= 30
       0 1993.84    52.5 1971.67    68.6 1962.56    84.6 1943.19    92.7 1935.25
   100.7 1923.59   104.7 1919.16   108.7 1916.74   164.9 1886.22   197.1 1872.06
   217.71865.843   261.3 1856.17   291.5 1854.18   361.7 1853.31   376.4 1849.51
   381.7 1846.57   393.8 1845.74   401.8 1846.68   407.7 1849.39   413.8 1853.74
   429.9 1856.03   441.9 1865.36   453.9 1871.51   510.3 1898.53   524.51903.885
   599.7 1933.23   672.2 1955.95     738 1979.67   759.1 1984.42   795.2 1995.84
#Mann= 5 ,-1 , 0
       0      .1       0   217.7     .06       0   376.4    .045       0
   407.7     .06       0   524.5      .1       0
#XS Ineff= 2 , 0
           360.8    1853   413.8            1853
Permanent Ineff=
       F       F
Bank Sta=376.4,407.7
XS Rating Curve= 0 ,0
Exp/Cntr(USF)=0,0
Exp/Cntr=0.5,0.3

Type RM Length L Ch R = 1 ,5084    ,88.3,88.3,88.3
XS GIS Cut Line= 4
 2418587.7496313669909.1444123242418927.03766479 669936.07568056
2419033.04185962669948.0417374862419361.07621438669801.309742734
#Sta/Elev= 30
       0 2004.29      15 1995.11    84.2 1964.46    87.3 1961.88    91.3 1955.13
   103.3 1927.77   107.3 1920.08   111.3 1916.01   147.5 1903.09   175.5 1886.62
   199.6 1880.56   231.2 1866.89   243.8 1859.09   280.3 1853.55   321.61851.799
   364.1  1851.4   372.3 1848.82   380.3 1845.77   400.4 1844.98   407.7 1848.96
   416.5 1852.49   440.7 1852.53   452.2 1861.49   469.4 1872.37   500.7 1881.68
  527.421892.407   626.2 1918.39   650.5 1922.82   755.6 1961.93   806.4 1977.59
#Mann= 5 ,-1 , 0
       0      .1       0   321.6     .06       0   372.3    .045       0
   407.7     .06       0  527.42      .1       0
#XS Ineff= 2 , 0
          357.48 1855.95
Permanent Ineff=
       F       F
Bank Sta=372.3,407.7
XS Rating Curve= 0 ,0
Exp/Cntr(USF)=0,0
Exp/Cntr=0.5,0.3

Type RM Length L Ch R = 1 ,4995    ,382.4,382.4,382.4
XS GIS Cut Line= 2
2418643.65736051 670228.86281458 2419360.3406639 669818.88981458
#Sta/Elev= 30
       0 2041.54    40.4  2029.1    68.1 2018.58   137.2 1984.26   197.2 1945.04
   229.5 1916.22   279.3 1883.25   293.9 1871.66   311.5 1869.24   329.1 1855.63
   335.3 1853.37     363 1848.15   390.6 1848.91   396.5 1847.04   404.5 1844.06
   422.9 1843.78   432.1 1844.13     439 1846.71   450.6 1851.49   473.6 1849.48
   478.2 1850.85     492 1858.65   503.4 1868.34   510.5 1872.38   541.51880.679
     575 1885.21   616.2 1898.66     737 1928.56   777.7 1949.19   825.7    1968
#Mann= 4 ,-1 , 0
       0      .1       0   396.5    .045       0     439     .06       0
   541.5      .1       0
Bank Sta=396.5,439
XS Rating Curve= 0 ,0
Exp/Cntr=0.3,0.1

Type RM Length L Ch R = 1 ,4613    ,300,300,300
XS GIS Cut Line= 3
     2418840.741       670552.54     2419198.446      670351.668
     2419565.823      670171.069
#Sta/Elev= 30
       0 2039.89   70.622023.761     117  2013.2  176.382002.854   187.8 2000.38
   249.5 1974.63   263.8 1950.11   275.9 1941.69   282.1 1932.51   296.5 1916.63
   302.3 1912.94     320 1910.49   387.91849.395   399.3 1836.18   405.2 1831.87
   410.6 1831.36   426.7 1835.54  492.151840.025   517.6 1839.23   526.5 1843.14
   557.7 1865.41     580 1878.95   590.3 1892.69   596.3 1898.08   632.2 1920.85
   656.8 1938.85     727  1974.7   767.2 1988.33   790.6 1998.57   819.6 2015.14
#Mann= 7 ,-1 , 0
       0      .1       0   70.62     .05       0  176.38      .1       0
   387.9     .06       0   399.3    .045       0   426.7     .06       0
  492.15      .1       0
Bank Sta=399.3,426.7
XS Rating Curve= 0 ,0
Exp/Cntr=0.3,0.1

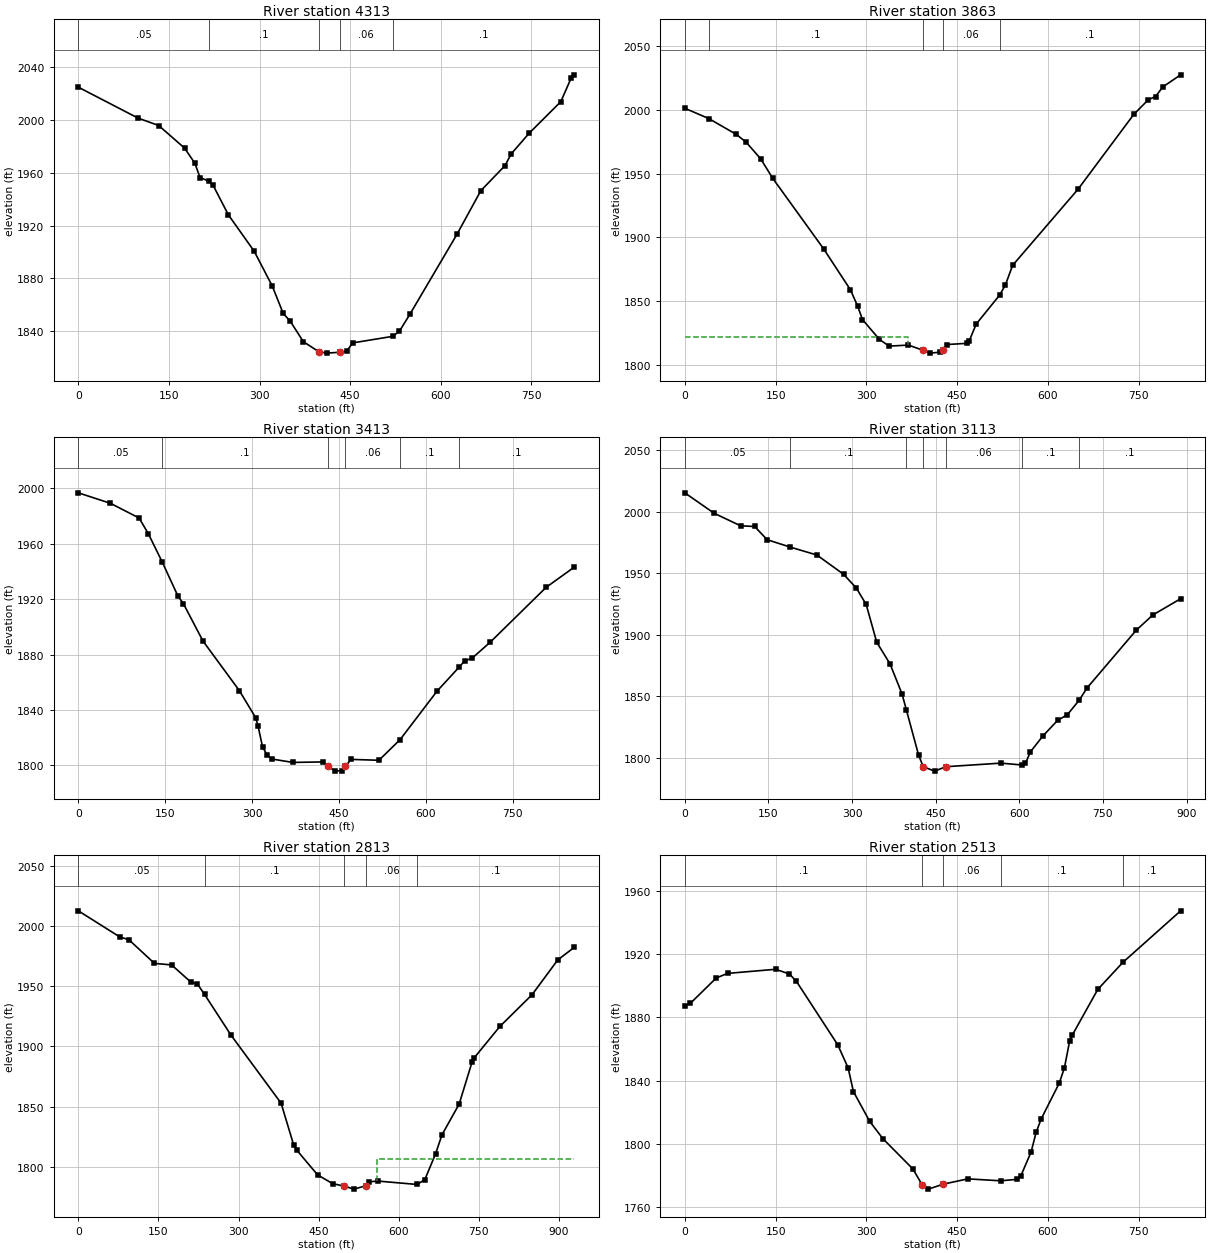
Type RM Length L Ch R = 1 ,4313    ,450,450,450
XS GIS Cut Line= 3
     2418930.246      670771.262     2419313.079      670627.174
     2419695.682      670475.218
#Sta/Elev= 30
       0 2024.79    98.8 2001.39     133 1995.77   175.8 1978.67   192.9  1967.2
   201.4 1956.39  215.871953.632   222.8 1950.72   248.4 1928.09   291.2 1900.46
   321.1  1874.1   339.1 1853.46     351 1847.42   372.4  1832.1   397.7 1824.54
   410.8 1823.39   432.4 1824.03   444.4 1824.98   453.9 1831.12  520.251836.089
   531.4 1839.93   548.6 1852.65   626.6 1913.27   666.2 1946.39   706.3 1965.43
   716.4 1974.23   746.5 1990.06   798.7 2013.88   815.4 2031.39   820.7 2034.15
#Mann= 5 ,-1 , 0
       0     .05       0  215.87      .1       0   397.7    .045       0
   432.4     .06       0  520.25      .1       0
Bank Sta=397.7,432.4
XS Rating Curve= 0 ,0
Exp/Cntr=0.3,0.1

Type RM Length L Ch R = 1 ,3863    ,450,450,450
XS GIS Cut Line= 3
     2418973.514      671076.479     2419382.831      671064.251
     2419792.149      671052.024
#Sta/Elev= 30
       0 2001.17   39.591993.123    85.3 1980.65   101.3  1974.6   125.3 1961.63
   145.3 1946.28   229.3 1891.08   273.4 1859.14   285.4 1846.35   293.4  1835.7
   321.4 1820.18   337.4 1814.86   369.4 1815.68   393.4 1811.64   405.4 1809.38
   421.4 1810.13   426.3 1811.98   433.4 1816.12   465.4 1817.04   469.4 1818.52
   481.4 1832.17  520.131854.884   529.5 1862.72   541.5 1878.14   649.5 1937.74
   741.6 1996.35   765.6 2007.86   777.6 2010.39   789.6 2017.91     819 2027.37
#Mann= 5 ,-1 , 0
       0     .05       0   39.59      .1       0   393.4    .045       0
   426.3     .06       0  520.13      .1       0
#XS Ineff= 2 , 0
          369.21 1822.18
Permanent Ineff=
       F       F
Bank Sta=393.4,426.3
XS Rating Curve= 0 ,0
Exp/Cntr=0.3,0.1

Type RM Length L Ch R = 1 ,3413    ,300,300,300
XS GIS Cut Line= 3
2418914.28392233671466.525579417     2419355.446      671511.823
     2419766.879       671543.35
#Sta/Elev= 30
       0 1996.78    55.5 1989.21     105 1978.58   121.1 1967.06  144.98 1946.71
   172.1 1922.17   181.4 1916.78   215.2 1889.81   277.9 1854.08   306.1  1834.5
   310.1  1828.8   318.1 1813.34   326.2 1807.31   334.2 1804.62   370.4 1802.18
   422.7 1802.53   430.3 1799.45   443.5 1795.89   454.8 1796.29   461.1 1799.33
   470.9 1804.36     519 1803.72  555.661818.669   619.3 1853.61  657.831871.109
   667.4 1875.63   679.5 1877.27   711.6 1889.12   807.8 1928.58   856.1 1943.09
#Mann= 6 ,-1 , 0
       0     .05       0  144.98      .1       0   430.3    .045       0
   461.1     .06       0  555.66      .1       0  657.83      .1       0
Bank Sta=430.3,461.1
XS Rating Curve= 0 ,0
Exp/Cntr=0.3,0.1

Type RM Length L Ch R = 1 ,3113    ,300,300,300
XS GIS Cut Line= 3
 2418959.0860389671993.917964252     2419359.332      671791.223
2419759.19139083671605.905708086
#Sta/Elev= 30
       0 2015.38    52.6 1998.77   100.2 1988.55   125.2 1988.02   147.8 1977.25
  189.071971.257   236.9 1964.81   284.8 1949.16   307.7 1937.96   325.4 1924.57
   344.3 1893.86   368.1 1876.31   389.7 1851.79  397.521838.717   419.3 1802.24
   427.6 1792.73     448 1789.07   468.5 1792.68     567 1795.57  604.331794.081
   611.1 1795.36   619.9 1804.71     642 1817.48   668.6  1830.3   686.1 1834.89
  707.481846.749   721.3 1856.57   809.5 1903.51   839.5 1916.04   889.4 1929.26
#Mann= 7 ,-1 , 0
       0     .05       0  189.07      .1       0  397.52     .06       0
   427.6    .045       0   468.5     .06       0  604.33      .1       0
  707.48      .1       0
Bank Sta=427.6,468.5
XS Rating Curve= 0 ,0
Exp/Cntr=0.3,0.1

Type RM Length L Ch R = 1 ,2813    ,300,300,300
XS GIS Cut Line= 3
2419016.93263778672078.348045821      2419534.55      672026.849
     2419941.268      671990.409
#Sta/Elev= 30
       0 2012.42    78.2 1990.61    94.3 1988.61   142.5 1968.84   174.7 1967.56
   210.8  1953.3   222.9 1951.83  236.35 1943.11   286.3 1909.08   379.7 1852.93
   403.3 1818.18   408.8 1814.11     448  1793.5   476.2 1786.23   498.1 1784.11
   516.3 1781.66   538.7 1784.51   544.5 1787.67   560.5 1788.36  634.441785.522
   648.9 1789.57     669 1810.98     681 1826.74   713.1 1852.14   737.2  1886.9
   741.2 1890.47   789.4 1916.54   849.7 1942.88   897.9 1971.77   928.5 1982.06
#Mann= 5 ,-1 , 0
       0     .05       0  236.35      .1       0   498.1    .045       0
   538.7     .06       0  634.44      .1       0
#XS Ineff= 2 , 0
                          558.52         1806.98
Permanent Ineff=
       F       F
Bank Sta=498.1,538.7
XS Rating Curve= 0 ,0
Exp/Cntr=0.3,0.1

Type RM Length L Ch R = 1 ,2513    ,300,300,300
XS GIS Cut Line= 3
     2419202.155      672463.829     2419585.313      672319.396
     2419971.866      672183.836
#Sta/Elev= 30
       0 1887.39     9.2 1888.88    51.9 1904.91    70.7 1907.82   150.1 1910.41
   172.8 1907.44   184.4 1902.78   252.7 1862.66   269.9 1848.02   278.5 1833.16
   305.4 1814.31   327.2 1803.37   376.8 1784.21   392.4 1773.99   402.5 1771.46
   426.7 1774.58   467.5 1777.94  521.92 1776.72   549.1 1777.66   555.4 1780.06
   572.1 1794.99   580.5 1807.48     589 1816.02   618.7 1838.52   627.2 1848.25
   635.7 1864.96   639.9 1868.66   682.3 1897.72  723.68 1914.77   819.1 1947.36
#Mann= 5 ,-1 , 0
       0      .1       0   392.4    .045       0   426.7     .06       0
  521.92      .1       0  723.68      .1       0
Bank Sta=392.4,426.7
XS Rating Curve= 0 ,0
Exp/Cntr=0.3,0.1