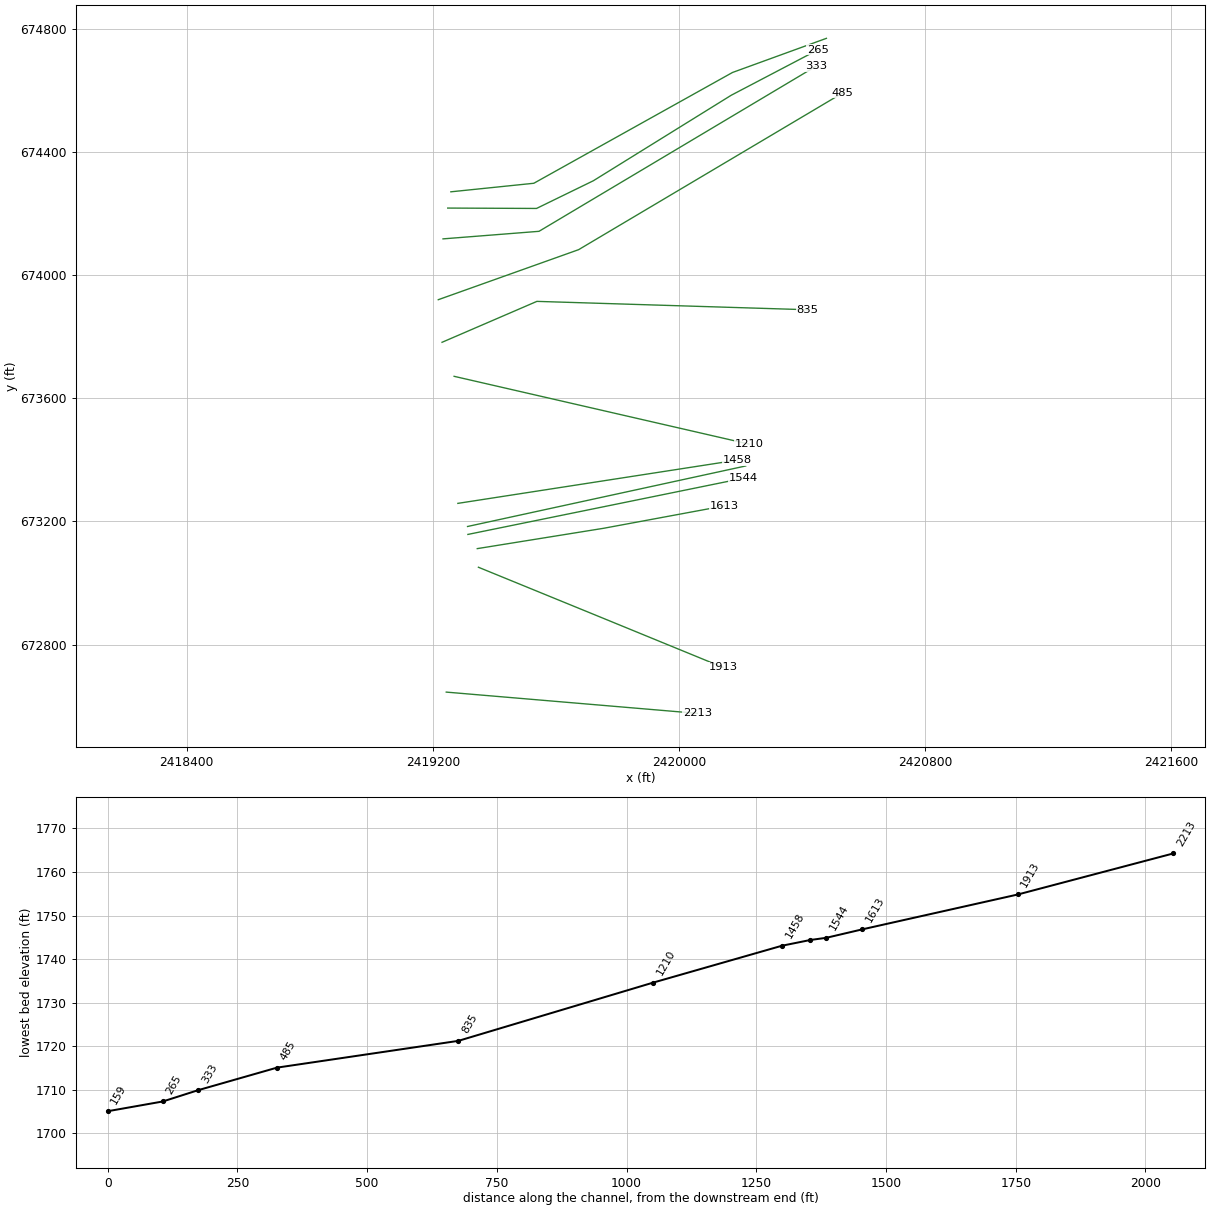
HEC-RAS study BRUSHRN.prj: BRUSHRN

--- BRUSHRN.g02 (geometry) --- (continued)

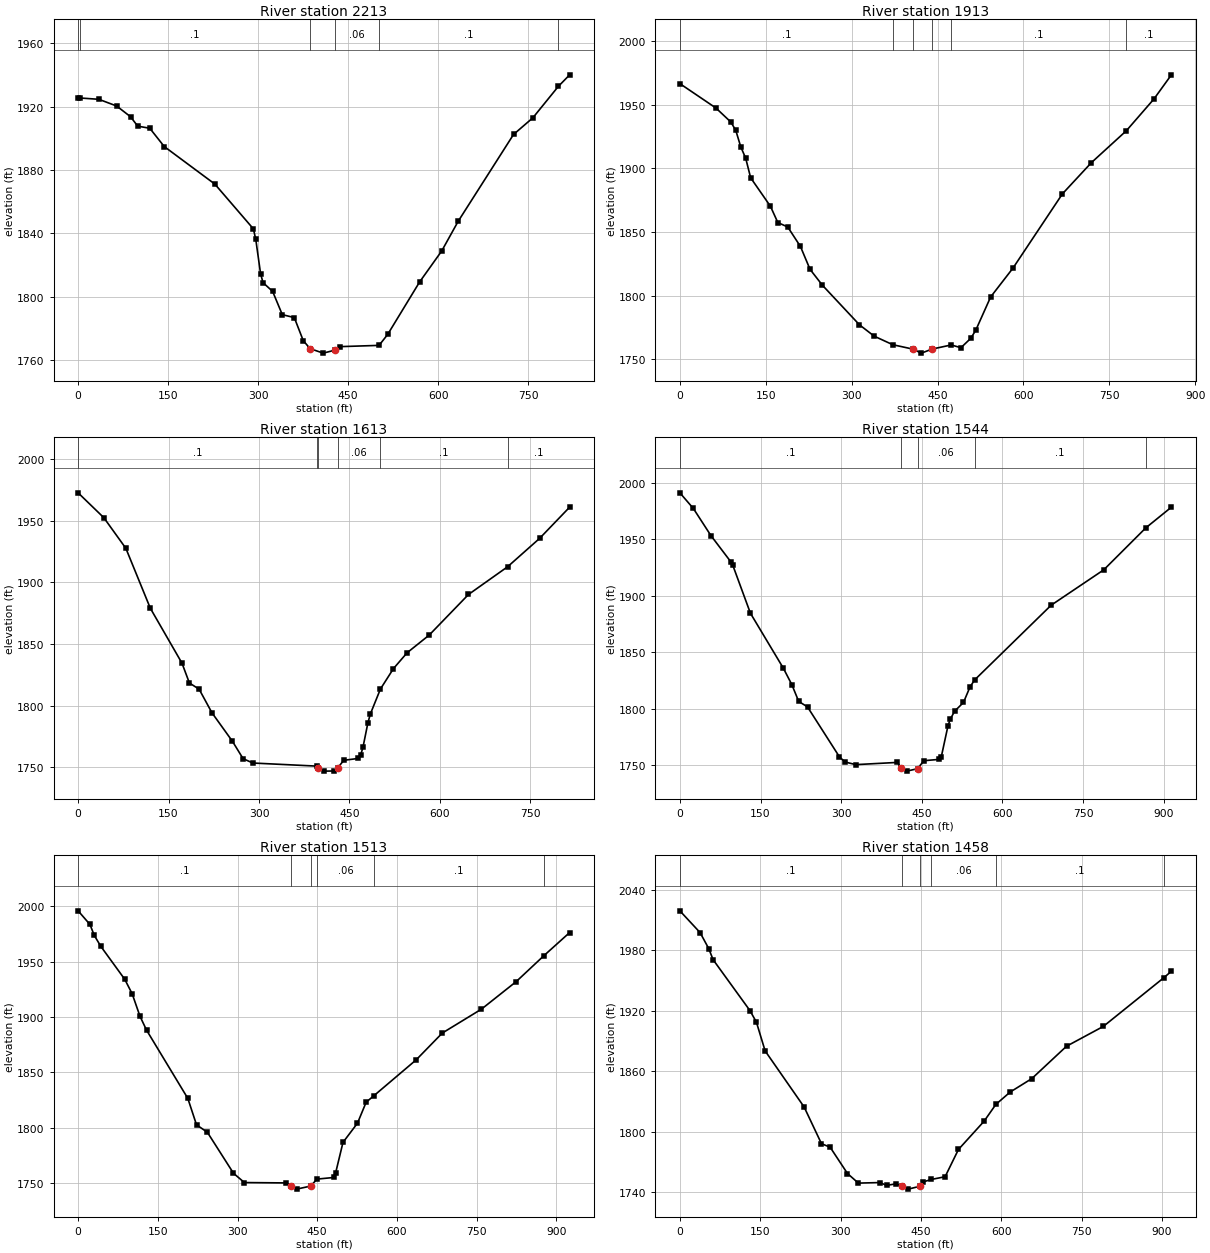
Type RM Length L Ch R = 1 ,2213    ,300,300,300
XS GIS Cut Line= 3
      2419243.79      672645.383     2419651.829      672610.817
     2420059.867       672576.25
#Sta/Elev= 30
       0 1925.73    3.411925.526    34.6 1924.69    64.3 1920.44    87.3 1913.69
    99.3 1907.73   119.4  1906.4   143.5 1894.84   227.8 1871.11     292 1842.81
     296 1836.17     304  1814.5   308.1 1808.81   324.1 1803.26   340.2 1788.57
   360.2 1786.72   375.1 1772.17   386.5 1767.08   408.4 1764.25   428.5 1766.19
   436.5 1768.35  501.441769.148   515.8 1776.07     569 1809.24   605.8 1828.81
   633.2 1847.55   725.5 1902.48   757.7    1913  800.25  1932.9     819 1940.17
#Mann= 6 ,-1 , 0
       0      .1       0    3.41      .1       0   386.5    .045       0
   428.5     .06       0  501.44      .1       0  800.25      .1       0
Bank Sta=386.5,428.5
XS Rating Curve= 0 ,0
Exp/Cntr=0.3,0.1

Type RM Length L Ch R = 1 ,1913    ,300,300,300
XS GIS Cut Line= 3
2419348.32923474 673051.11399119     2419740.775      672890.676
2420142.81931278672725.903791064
#Sta/Elev= 30
       0 1966.51    63.1 1947.32      89 1936.36    97.7 1929.75   106.3 1916.92
     115 1907.87   123.6 1892.57   158.2 1870.16   171.1 1857.38   188.4 1853.91
   210.6 1838.59   227.3 1820.67   248.9 1808.18   313.7 1777.05   339.4 1768.14
  371.981761.414   406.9 1757.99   421.8 1754.82   440.7 1758.03  473.931761.234
   490.9 1759.08   508.1 1766.45   516.9 1772.91   542.8 1798.95   581.8 1821.61
   668.2 1879.95   718.7 1904.43  779.811929.512   828.1 1954.51   858.5 1973.43
#Mann= 6 ,-1 , 0
       0      .1       0  371.98     .06       0   406.9    .045       0
   440.7     .06       0  473.93      .1       0  779.81      .1       0
Bank Sta=406.9,440.7
XS Rating Curve= 0 ,0
Exp/Cntr=0.3,0.1

Type RM Length L Ch R = 1 ,1613    ,69,69,69
XS GIS Cut Line= 3
     2419344.579      673111.622     2419754.838      673177.656
2420147.67753639673250.555920933
#Sta/Elev= 30
       0 1972.66    42.7 1952.45    79.2 1927.59   119.7 1879.03   172.3 1834.36
   184.5 1818.36   200.7 1813.28   221.9 1794.18     256 1770.94   273.6  1756.9
   289.8 1753.39  395.941750.872   398.1 1749.55   407.3 1746.81   423.6 1746.91
   430.2 1749.26   440.5 1755.59   464.3 1757.09   468.3 1759.52   472.4 1766.23
   480.5 1785.92   484.6 1793.17  501.281813.403   522.9 1830.01   545.6 1842.88
   582.2 1857.22   647.3 1890.15  712.291912.694   765.3  1935.7   815.1 1961.04
#Mann= 6 ,-1 , 0
       0      .1       0  395.94     .06       0   398.1    .045       0
   430.2     .06       0  501.28      .1       0  712.29      .1       0
Bank Sta=398.1,430.2
XS Rating Curve= 0 ,0
Exp/Cntr=0.5,0.3

Type RM Length L Ch R = 1 ,1544    ,31.2,31.2,31.2
XS GIS Cut Line= 2
2419314.17269042673157.7837618132420209.91451232673340.444839222
#Sta/Elev= 30
       0 1991.22    25.1 1977.36    57.7 1953.41    94.5 1930.33    98.6 1926.91
   131.2 1884.66   192.5 1835.95   208.3  1821.4     221  1806.6   237.4 1801.72
   296.7 1757.59     307 1752.99   327.2 1750.63   404.7  1752.6  411.79  1747.4
   421.9 1744.88   442.2 1747.05   453.7 1754.11   482.3 1755.27   486.3 1757.72
   498.6 1784.85   502.7 1790.62   510.9 1797.84   527.5 1805.69   539.5 1819.26
  548.011825.506   690.5 1891.73   788.5  1923.1   866.61960.205   914.2 1978.53
#Mann= 5 ,-1 , 0
       0      .1       0  411.79    .045       0   442.2     .06       0
  548.01      .1       0   866.6      .1       0
#XS Ineff= 2 , 0
           404.5    1750   452.4            1750
Permanent Ineff=
       F       F
Bank Sta=411.79,442.2
XS Rating Curve= 0 ,0
Exp/Cntr(USF)=0,0
Exp/Cntr=0.5,0.3

Type RM Length L Ch R = 1 ,1513    ,54.3,54.3,54.3
XS GIS Cut Line= 2
2419313.00178607673183.5436573452420216.93993838673380.255586862
#Sta/Elev= 30
       0 1995.81    22.3 1983.47    30.4  1973.6    42.7 1963.72    87.8 1933.92
   101.8 1920.76   116.4 1900.58   128.7 1888.09   206.5 1826.31   222.8  1802.5
   243.3  1795.7   292.4 1758.72   312.9  1750.3   390.9 1749.98     401 1747.44
   411.1 1744.37   437.4 1747.09  449.731753.424   480.7 1754.88   484.8  1759.3
   498.5  1786.6   525.8 1803.98   542.1 1822.91  556.471828.673   636.3  1861.2
   685.4 1885.38   759.1 1906.98   824.6 1931.91  876.671955.304   925.1 1976.19
#Mann= 6 ,-1 , 0
       0      .1       0     401    .045       0   437.4      .1       0
  449.73     .06       0  556.47      .1       0  876.67      .1       0
Bank Sta=401,437.4
XS Rating Curve= 0 ,0
Exp/Cntr(USF)=0,0
Exp/Cntr=0.5,0.3

Type RM Length L Ch R = 1 ,1458    ,248.4,248.4,248.4
XS GIS Cut Line= 2
2419281.51616831673258.7040070822420188.21765486673399.072019644
#Sta/Elev= 30
       0    2019    37.7 1997.44    53.9 1981.55      62 1970.58   130.8  1920.1
   142.9 1908.58   159.1 1880.15     232 1824.45   264.3 1788.13   280.5 1784.61
   312.9 1758.52   333.2 1749.03   373.6 1749.56   385.8 1746.75   404.3  1748.4
   414.1  1745.7   426.2 1743.06  448.27 1745.92   454.6 1750.27  469.361752.643
   495.1 1755.35     520 1782.39   567.9 1810.42   589.81827.036   616.5  1839.3
     657 1852.66   721.7 1884.73   790.5 1904.41   903.11952.548   917.5  1959.1
#Mann= 6 ,-1 , 0
       0      .1       0   414.1    .045       0  448.27      .1       0
  469.36     .06       0   589.8      .1       0   903.1      .1       0
Bank Sta=414.1,448.27
XS Rating Curve= 0 ,0
Exp/Cntr(USF)=0,0
Exp/Cntr=0.3,0.1

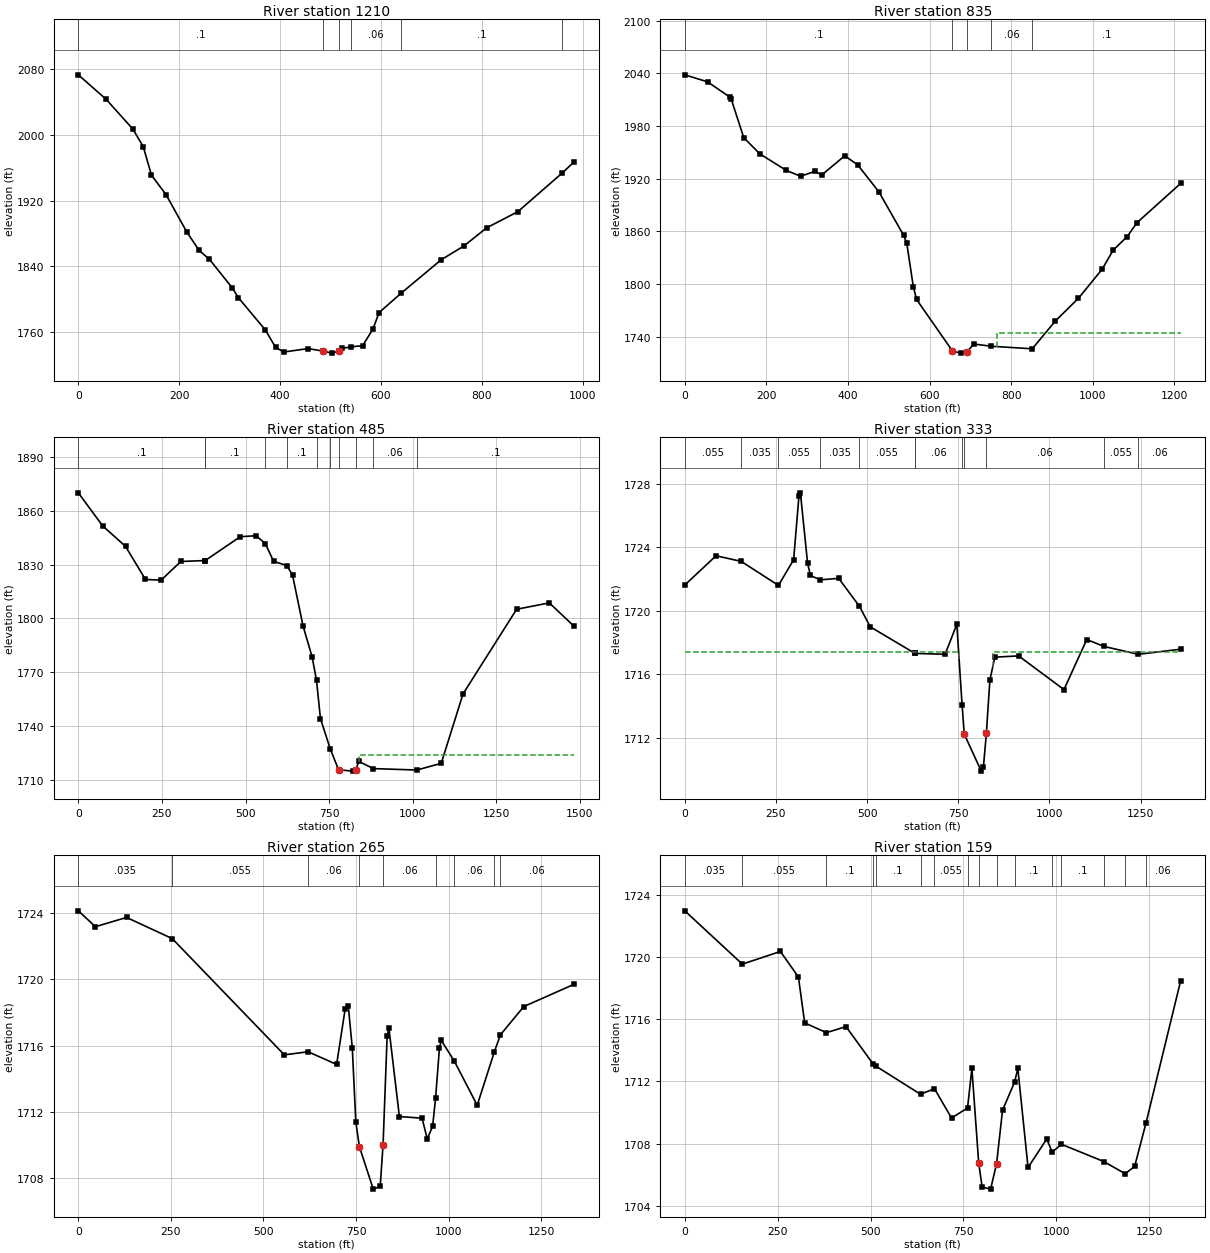
Type RM Length L Ch R = 1 ,1210    ,375.2,375.2,375.2
XS GIS Cut Line= 2
2419269.29652564673671.5677472332420227.71597187673451.241437754
#Sta/Elev= 30
       0 2073.06    55.2 2043.25   108.2 2007.05   128.7 1985.79   145.1 1950.94
   173.9 1927.42   214.9 1882.16   239.5 1859.54   260.1 1848.59   305.2  1814.1
   317.5 1801.96   370.9 1762.77   391.4 1741.46   407.8 1735.97   455.6  1740.1
     486 1737.05   502.2 1734.59  517.42    1737   522.7  1740.3  540.871742.284
   563.8 1743.55   584.3 1763.91   596.6 1783.95   640.41807.551   719.7 1848.15
   764.9 1864.94     810 1887.06   871.6 1906.56  959.581953.578   983.4 1967.27
#Mann= 6 ,-1 , 0
       0      .1       0     486    .045       0  517.42      .1       0
  540.87     .06       0   640.4      .1       0  959.58      .1       0
Bank Sta=486,517.42
XS Rating Curve= 0 ,0
Exp/Cntr(USF)=0,0
Exp/Cntr=0.3,0.1

Type RM Length L Ch R = 1 ,835     ,349.3,349.3,349.3
XS GIS Cut Line= 3
2419230.08737996673782.1282215982419538.36287471673915.109807567
2420417.85472736673887.909028619
#Sta/Elev= 30
       0 2038.21    55.9  2030.2   109.6 2013.13     114 2010.28   144.5 1966.73
   183.7 1948.26     249  1929.3   283.9 1922.71   318.7  1928.2   336.1 1924.27
   392.1 1945.98   424.2 1935.51   476.2 1904.69   536.2 1855.63   544.2 1846.43
   560.2 1797.06   568.2 1782.35   656.3 1723.65   676.3 1721.23   692.3 1722.86
   708.3 1731.62  751.661729.059  851.811726.172   908.4 1757.78   965.2 1783.79
  1023.4 1816.91  1050.3 1838.58  1084.5  1853.9  1108.5 1869.77  1215.6 1914.49
#Mann= 5 ,-1 , 0
       0      .1       0   656.3    .045       0   692.3      .1       0
  751.66     .06       0  851.81      .1       0
#XS Ineff= 2 , 0
                          764.51         1743.81
Permanent Ineff=
       F       F
Bank Sta=656.3,692.3
XS Rating Curve= 0 ,0
Exp/Cntr(USF)=0,0
Exp/Cntr=0.3,0.1

Type RM Length L Ch R = 1 ,485     ,151.9,151.9,151.9
XS GIS Cut Line= 3
2419217.81714541673920.5261460212419673.89260603674083.126962417
2420532.50423407674592.741716242
#Sta/Elev= 30
       0 1869.88    73.2  1851.4   141.1 1840.11   200.6 1821.73   247.3 1821.29
   306.7  1831.7  379.351832.218  379.471832.221   484.2 1845.48   531.7 1846.02
  558.971841.688   583.9 1831.79  623.531829.406   640.5 1824.14   671.8 1795.95
   699.2 1778.55  712.231765.604     724 1744.33  752.991727.624   778.2 1715.84
   820.1 1715.09   829.4 1715.82   838.7 1720.49  882.451716.497 1011.911715.701
  1085.2 1719.41  1150.4 1758.04  1310.7 1805.13  1408.5 1808.67  1482.7  1795.6
#Mann= 11 ,-1 , 0
       0      .1       0  379.35    .055       0  379.47      .1       0
  558.97    .055       0  623.53      .1       0  712.23    .035       0
  752.99      .1       0   778.2    .045       0   829.4      .1       0
  882.45     .06       0 1011.91      .1       0
#XS Ineff= 2 , 0
                          839.58         1724.07
Permanent Ineff=
       F       F
Bank Sta=778.2,829.4
XS Rating Curve= 0 ,0
Exp/Cntr(USF)=0,0
Exp/Cntr=0.5,0.3

Type RM Length L Ch R = 1 ,333     ,68.3,68.3,68.3
XS GIS Cut Line= 3
 2419233.3038817674118.2114349582419545.26647512674142.766350965
2420444.36724498674678.666629185
#Sta/Elev= 30
       0 1721.63    85.7 1723.47  154.561723.118  256.791721.606   298.4 1723.22
   312.9  1727.2     317 1727.43   336.6 1723.02   344.4 1722.23  371.381721.955
     422 1722.05  479.031720.286   508.5    1719   630.71717.333  631.951717.326
   713.8 1717.27   745.9 1719.16  760.36 1714.08   766.3 1712.25   812.9 1709.92
   818.8 1710.17   826.9 1712.29   836.6 1715.66   850.2 1717.09   915.4 1717.17
  1039.7 1715.05  1102.2  1718.2 1149.341717.765 1243.651717.271  1359.6 1717.59
#Mann= 12 ,-1 , 0
       0    .055       0  154.56    .035       0  256.79    .055       0
  371.38    .035       0  479.03    .055       0   630.7    .035       0
  631.95     .06       0  760.36      .1       0   766.3    .045       0
   826.9     .06       0 1149.34    .055       0 1243.65     .06       0
#XS Ineff= 2 , 0
           752.4  1717.4   844.4          1717.4
Permanent Ineff=
       F       F
Bank Sta=766.3,826.9
XS Rating Curve= 0 ,0
Exp/Cntr(USF)=0,0
Exp/Cntr=0.5,0.3

Type RM Length L Ch R = 1 ,265     ,106.3,106.3,106.3
XS GIS Cut Line= 5
2419248.53075949674218.2983092022419537.17881264674217.090018173
2419721.91911824674307.1404147282420170.03529419674585.031184479
2420451.35765279674732.391850646
#Sta/Elev= 30
       0 1724.15    46.2 1723.19   130.2 1723.75  253.561722.471   556.3 1715.44
  620.521715.627   697.5 1714.86   720.5  1718.2     729 1718.39   739.9 1715.85
   749.3 1711.39     759 1709.89   796.4 1707.32   815.2 1707.49   822.9 1709.98
     834 1716.61   838.7 1717.06     867 1711.71   928.2 1711.61   942.3 1710.36
   956.7 1711.11  964.861712.848   975.2 1715.85   979.9 1716.32 1015.391715.061
  1077.2 1712.39 1123.521715.625 1139.861716.653  1202.9 1718.36    1339 1719.71
#Mann= 9 ,-1 , 0
       0    .035       0  253.56    .055       0  620.52     .06       0
     759    .045       0   822.9     .06       0  964.86      .1       0
 1015.39     .06       0 1123.52      .1       0 1139.86     .06       0
Bank Sta=759,822.9
XS Rating Curve= 0 ,0
Exp/Cntr(USF)=0,0
Exp/Cntr=0.5,0.3

Type RM Length L Ch R = 1 ,159     ,,,
XS GIS Cut Line= 4
2419258.70530192  674271.14902842419528.38470473674298.910143394
2420174.07539991674658.9838235942420479.15973668674769.888487956
#Sta/Elev= 30
       0 1722.96   154.91719.535   257.4 1720.35   305.9 1718.71   322.8 1715.76
  381.321715.133   434.1 1715.52  507.97 1713.09  513.751712.995  634.621711.175
  672.251711.532   718.1 1709.65  761.271710.291     773 1712.83   791.3 1706.76
   800.5 1705.22   823.4 1705.08  839.43 1706.71   855.5 1710.15  887.931711.957
   896.7 1712.83   924.2 1706.47   974.5  1708.3  989.26 1707.46 1014.151707.961
 1127.911706.855  1185.8 1706.07  1211.2 1706.54 1241.671709.317    1335 1718.46
#Mann= 16 ,-1 , 0
       0    .035       0   154.9    .055       0  381.32      .1       0
  507.97    .055       0  513.75      .1       0  634.62     .06       0
  672.25    .055       0  761.27     .06       0   791.3    .045       0
  839.43    .035       0  887.93      .1       0  989.26    .035       0
 1014.15      .1       0 1127.91     .06       0  1185.8      .1       0
 1241.67     .06       0
Bank Sta=791.3,839.43
XS Rating Curve= 0 ,0
Exp/Cntr(USF)=0,0
Exp/Cntr=0.3,0.1
LCMann Table=0